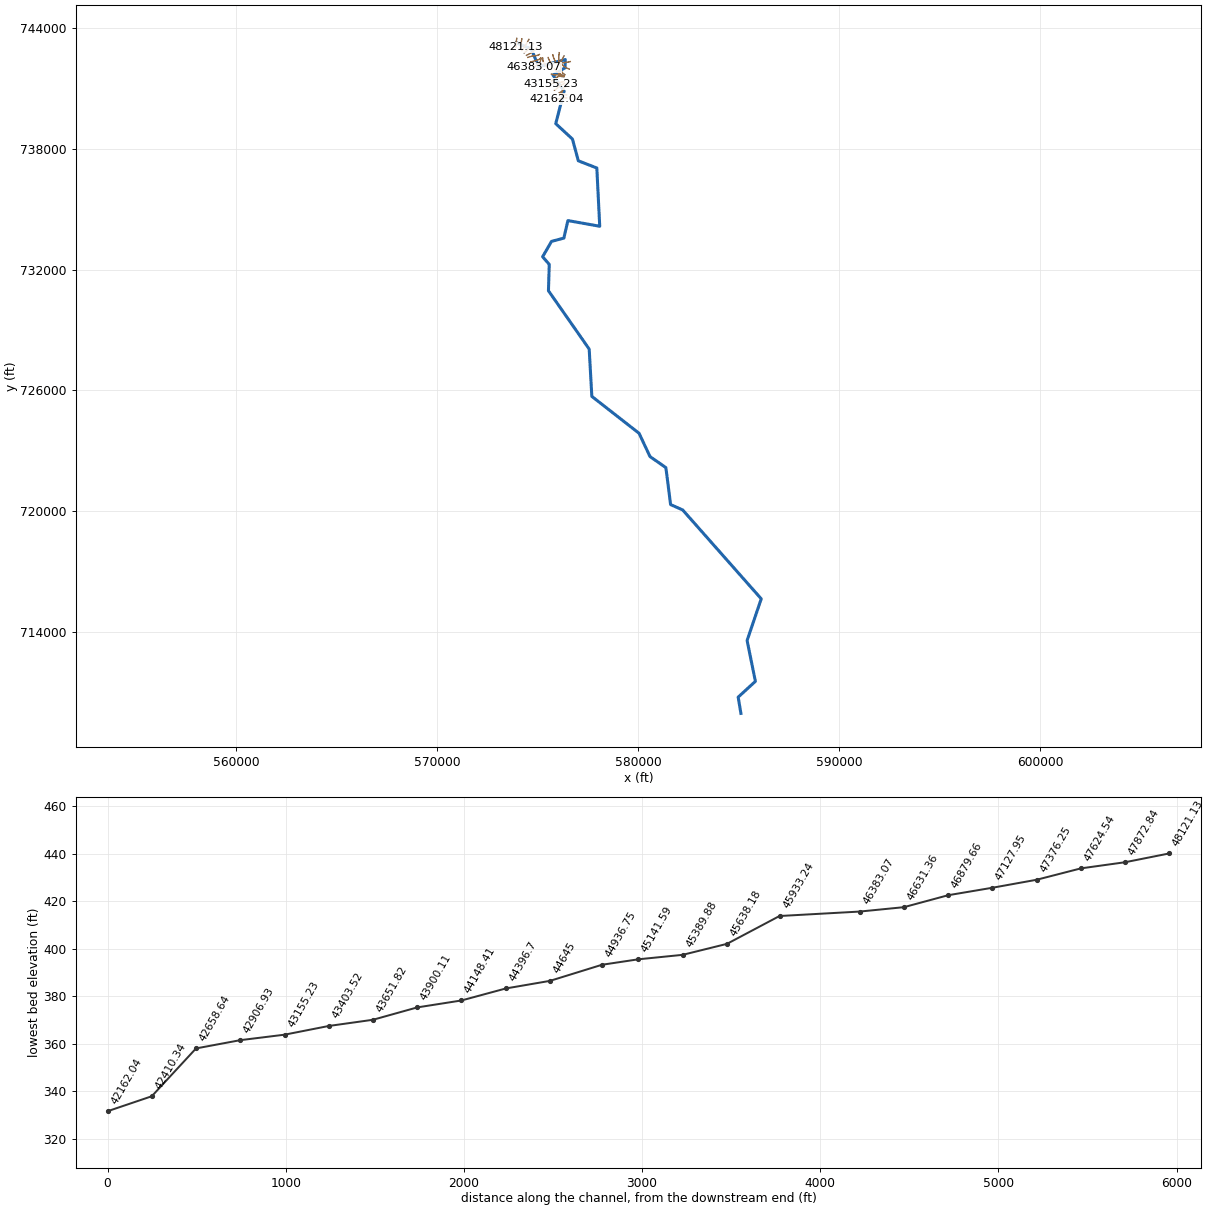
--- 2300_ras.prj (project) ---

Proj Title=2300
Current Plan=p01
Default Exp/Contr=0.3,0.1
English Units
Geom File=g01
Flow File=f01
Plan File=p01
Y Axis Title=Elevation
X Axis Title(PF)=Main Channel Distance
X Axis Title(XS)=Station
BEGIN DESCRIPTION:
RFD model 2300 exported to HEC-RAS
END DESCRIPTION:

--- 2300_ras.p01 (plan) ---

Plan Title=Plan 01
Program Version=4.10
Short Identifier=Plan 01
Geom File=g01
Flow File=f01
Subcritical Flow
Calc Critical at every XS
Secant Critical Depth

--- 2300_ras.f01 (steady flow) ---

Flow Title=Flow 01
Program Version=5.01
Number of Profiles= 6
Profile Names=10yr,25yr,50yr,100yr,100plus,500yr
River Rch & RM=2300,147,48121.13
  1954.8 3247.55 4502.73 5685.21 8300.4110536.52
River Rch & RM=2300,147,47872.84
 1959.99 3256.74    4516 5702.56 8325.7410566.56
River Rch & RM=2300,147,47624.54
 1965.55 3266.59 4530.21 5721.11 8352.8310598.58
River Rch & RM=2300,147,47376.25
 1986.82 3304.53 4585.23 5793.29  8458.210724.27
River Rch & RM=2300,147,47127.95
 1990.11 3310.44 4593.84 5804.62 8474.7510744.16
River Rch & RM=2300,147,46879.66
 1991.24 3312.49 4596.82 5808.56  8480.510751.12
River Rch & RM=2300,147,46631.36
 2005.27 3337.75 4633.67 5857.13 8551.41 10836.5
River Rch & RM=2300,147,46383.07
 2011.75 3349.45 4650.74 5879.65 8584.2910876.11
River Rch & RM=2300,147,45933.24
 2014.97 3355.27 4659.25 5890.88 8600.68 10895.9
River Rch & RM=2300,147,45638.18
 2020.11 3364.58 4672.85 5908.83  8626.910927.53
River Rch & RM=2300,147,45389.88
  2048.1 3414.48 4745.21 6003.75 8765.4711092.03
River Rch & RM=2300,147,45141.59
 2059.02 3434.02 4773.59 6041.03 8819.9111156.77
River Rch & RM=2300,147,44936.75
 2060.78 3437.19 4778.23 6047.16 8828.8611167.55
River Rch & RM=2300,147,   44645
 2072.41 3458.14 4808.79 6087.45 8887.6711237.99
River Rch & RM=2300,147, 44396.7
 2075.11 3463.04 4815.95  6096.9 8901.4711254.59
River Rch & RM=2300,147,44148.41
 2079.57  3471.1 4827.73 6112.47 8924.2111281.93
River Rch & RM=2300,147,43900.11
  2082.6 3476.58 4835.75 6123.05 8939.6511300.46
River Rch & RM=2300,147,43651.82
 2083.56 3478.32 4838.28 6126.39 8944.5311306.31
River Rch & RM=2300,147,43403.52
 2088.64 3487.51 4851.72 6144.15 8970.4611337.48
River Rch & RM=2300,147,43155.23
 2090.87 3491.63 4857.82  6152.3 8982.3511352.08
River Rch & RM=2300,147,42906.93
  2100.9 3510.12 4885.15 6188.72 9035.5311417.22
River Rch & RM=2300,147,42658.64
 2102.39 3512.86 4889.21 6194.14 9043.4411426.93
River Rch & RM=2300,147,42410.34
 2106.84 3521.09 4901.38 6210.39 9067.1611456.03
River Rch & RM=2300,147,42162.04
 2109.81 3526.57  4909.5 6221.22 9082.9811475.42
River Rch & RM=2300,147,41913.75
 2112.18 3530.96 4915.99 6229.88 9095.6211490.92
River Rch & RM=2300,147,41665.45
 2118.03 3541.81 4932.09 6251.41 9127.0511529.64
River Rch & RM=2300,147,41417.16
  2119.7 3544.96 4936.81 6257.76 9136.3311541.25
River Rch & RM=2300,147,41168.86
 2120.67 3546.79 4939.56 6261.47 9141.7411548.01
River Rch & RM=2300,147,40920.57
 2169.15 3636.66 5072.81  6439.6 9401.8111867.24
River Rch & RM=2300,147,40672.27
 2169.84 3637.96 5074.76 6442.22 9405.6511872.02
River Rch & RM=2300,147,40423.98
 2171.49 3641.08 5079.44 6448.53 9414.8511883.49
River Rch & RM=2300,147,40175.68
 2180.43 3657.96 5104.72 6482.62 9464.6211945.56
River Rch & RM=2300,147,39927.39
 2186.99 3670.45 5123.53 6508.07 9501.7811992.27
River Rch & RM=2300,147,39679.09
  2321.9  3914.7 5481.09    698110192.2512812.91
River Rch & RM=2300,147, 39430.8
 2325.94 3922.33 5492.52 6996.4210214.7712840.74
River Rch & RM=2300,147, 39182.5
 2328.29 3926.82 5499.28 7005.5810228.1512857.42
River Rch & RM=2300,147,38934.21
 2331.89 3933.72 5509.72 7019.7710248.8612883.36
River Rch & RM=2300,147,38685.91
 2342.19 3953.46 5539.54 7060.2610307.9812957.36
River Rch & RM=2300,147,38437.61
 2343.48 3955.92 5543.27 7065.3210315.36 12966.6
River Rch & RM=2300,147,38189.32
 2347.72 3964.05 5555.55    708210339.7112997.07
River Rch & RM=2300,147,37941.02
 2348.88 3966.27  5558.9 7086.5510346.3613005.38
River Rch & RM=2300,147,37692.73
 2428.29  4114.5 5779.81  7383.210779.4713532.64
River Rch & RM=2300,147,37444.43
 2431.19 4120.07 5788.24 7394.6610796.2113553.53
River Rch & RM=2300,147,37196.14
 2435.48 4128.22 5800.51 7411.2710820.4613583.47
River Rch & RM=2300,147,36947.84
 2449.71  4155.2 5841.07 7466.1510900.5713682.19
River Rch & RM=2300,147,36699.55
 2463.48 4181.91 5881.73 7521.71 10981.713784.24
River Rch & RM=2300,147,36451.25
 2465.19 4185.23 5886.78  7528.610991.7613796.87
River Rch & RM=2300,147,36202.96
 2467.63 4189.96 5893.98 7538.4411006.1213814.89
River Rch & RM=2300,147,35954.66
 2469.71 4193.98  5900.1  7546.811018.33 13830.2
River Rch & RM=2300,147,35706.37
 2499.76 4251.71 5987.55 7665.8411192.1314046.59
River Rch & RM=2300,147,35458.07
 2505.27 4262.36 6003.73 7687.9111224.3514086.85
River Rch & RM=2300,147,35209.78
 2513.09 4277.55 6026.88 7719.5811270.5814144.92
River Rch & RM=2300,147, 34935.8
 2514.47 4280.28 6031.08 7725.3511279.0114155.63
River Rch & RM=2300,147,34464.89
  2527.2 4305.17 6069.14 7777.5711355.2514251.88
River Rch & RM=2300,147, 33968.3
 2560.35 4370.37 6169.18 7915.1711556.1414506.43
River Rch & RM=2300,147,   33720
 2570.57 4390.56 6200.24 7957.9811618.65 14585.9
River Rch & RM=2300,147,33515.48
 2571.37 4392.15 6202.67 7961.3211623.5314592.07
River Rch & RM=2300,147,32973.61
 2587.06 4423.43 6251.02 8028.2311721.2214717.08
River Rch & RM=2300,147,32478.53
 2591.16 4431.59 6263.63 8045.6611746.6714749.59
River Rch & RM=2300,147,32230.23
 2594.31 4437.83 6273.23 8058.91   1176614774.17
River Rch & RM=2300,147,31981.94
  2596.8 4442.74 6280.78 8069.3211781.2114793.47
River Rch & RM=2300,147,31733.64
 2599.69  4448.4 6289.45 8081.2411798.6114815.39
River Rch & RM=2300,147,31485.35
 2600.84 4450.66 6292.92 8086.0111805.5714824.15
River Rch & RM=2300,147,31237.05
 2604.91  4458.7 6305.28 8103.0411830.4414855.69
River Rch & RM=2300,147,30988.76
 2606.42 4461.64 6309.79 8109.2311839.4814867.07
River Rch & RM=2300,147,30740.46
 2611.04 4470.69 6323.65 8128.2811867.2914902.07
River Rch & RM=2300,147,30492.16
 2615.04 4478.48 6335.53 8144.5611891.06 14931.8
River Rch & RM=2300,147,30243.87
 2617.44 4483.19 6342.77 8154.5211905.5914950.14
River Rch & RM=2300,147,29747.28
  2630.1 4508.24 6381.34 8207.7311983.2915048.72
River Rch & RM=2300,147,29498.98
 2632.92 4513.71 6389.69 8219.1912000.0115069.62
River Rch & RM=2300,147,29250.69
 2637.42 4522.44 6402.99 8237.3812026.58 15102.7
River Rch & RM=2300,147,29002.39
 2638.13 4523.82 6405.09 8240.2512030.7715107.92
River Rch & RM=2300,147, 28754.1
 3495.57 6079.61 8690.0211272.6716458.1120135.69
River Rch & RM=2300,147, 28505.8
 3496.47 6081.34 8692.6411276.2616463.3420141.91
River Rch & RM=2300,147,28257.51
 3499.16 6086.52 8700.5111287.0116479.0420160.55
River Rch & RM=2300,147,28009.21
 3543.26 6167.69 8820.8211447.95   1671420426.27
River Rch & RM=2300,147,27760.92
 3550.42  6181.6 8842.0711477.1216756.5920477.25
River Rch & RM=2300,147,27512.62
 3551.53 6183.74 8845.3311481.5716763.0920484.97
River Rch & RM=2300,147,27264.33
 3553.95 6188.42 8852.4611491.3316777.3420501.94
River Rch & RM=2300,147,27016.03
 3557.16  6194.6 8861.8711504.2216796.1620524.32
River Rch & RM=2300,147,26767.73
 3615.14 6301.66 9020.8511717.2517107.1820876.37
River Rch & RM=2300,147,26519.44
 3616.46 6304.21 9024.7411722.5617114.9520885.56
River Rch & RM=2300,147,26271.14
 3618.78 6308.68 9031.5411731.8717128.5320901.65
River Rch & RM=2300,147,26022.85
 3636.64 6343.67 9085.26 11805.917236.6121031.67
River Rch & RM=2300,147,25774.55
 3641.04 6352.15 9098.1711823.56 17262.421062.21
River Rch & RM=2300,147,25526.26
 3642.02 6354.03 9101.0611827.5217268.1821069.09
River Rch & RM=2300,147,25277.96
  3802.5 6656.86 9556.59 12444.718169.2622108.74
River Rch & RM=2300,147,25029.67
 3804.42 6660.65 9562.4312452.7918181.0722122.97
River Rch & RM=2300,147,24781.37
 3813.67 6678.73 9590.1912491.03 18236.922189.58
River Rch & RM=2300,147,24443.92
 3815.68 6682.71 9596.3312499.5418249.3222204.54
River Rch & RM=2300,147,24380.07
  3817.2  6685.7 9600.9512505.9218258.6422215.75
River Rch & RM=2300,147,24272.56
 3863.09  6772.9 9732.6912685.0818520.2222518.48
River Rch & RM=2300,147,24027.42
 3865.97 6778.62 9741.5312697.33 18538.122540.05
River Rch & RM=2300,147,23782.29
 3868.06 6782.76 9747.93 12706.218551.0522555.66
River Rch & RM=2300,147,23537.15
 3953.71 6954.6710015.6313079.4219095.9523219.23
River Rch & RM=2300,147,23292.02
  3954.4 6956.0410017.7513082.3519100.2423224.38
River Rch & RM=2300,147,23046.88
 3971.07 6989.7810070.5313156.2319208.0923356.48
River Rch & RM=2300,147,22801.75
 3971.64 6990.9210072.3113158.7119211.7223360.88
River Rch & RM=2300,147,22556.61
 3977.53 7002.8610091.01 13184.919249.9623407.77
River Rch & RM=2300,147,22311.48
  4000.7 7048.0310160.2713280.2819389.2123572.35
River Rch & RM=2300,147,22066.34
 4004.97 7056.6610173.7513299.1319416.7423605.94
River Rch & RM=2300,147,21821.21
 4019.38 7086.0510219.9513364.0319511.4823722.63
River Rch & RM=2300,147,21576.07
 4038.48 7123.2810277.0213442.6319626.23   23858
River Rch & RM=2300,147,21330.94
 4041.05 7128.4810285.1713454.0319642.8823878.35
River Rch & RM=2300,147, 21085.8
 4045.19 7136.9310298.4413472.6619670.0823911.78
River Rch & RM=2300,147,20840.67
 4055.05 7156.3810328.4913514.2919730.8723984.37
River Rch & RM=2300,147,20595.53
 4062.72 7171.54 10351.913546.7419778.2424040.93
River Rch & RM=2300,147, 20350.4
 4066.05 7178.1910362.2313561.1319799.2424066.29
River Rch & RM=2300,147,19860.13
 4069.35 7184.9410372.8513576.0519821.0324093.09
River Rch & RM=2300,147,   19615
 4081.47 7209.7710411.9713631.1119901.4224192.22
River Rch & RM=2300,147,19124.73
 4083.02 7212.9810417.0413638.2819911.8824205.24
River Rch & RM=2300,147,18879.59
 4096.15  7239.7   1045913697.1819997.8824310.69
River Rch & RM=2300,147,18634.46
 4096.92  7241.310461.5313700.7620003.1124317.18
River Rch & RM=2300,147,18389.32
 4115.49 7280.8110524.9613791.3820135.4124485.08
River Rch & RM=2300,147,18144.19
 4116.47 7282.9310528.4213796.3520142.6724494.43
River Rch & RM=2300,147,17899.05
 4141.05 7334.4210610.46 13912.920312.8324707.76
River Rch & RM=2300,147,17653.92
 4142.02 7336.5410613.9113917.8620320.0724717.09
River Rch & RM=2300,147,17408.78
 4148.74 7351.2410637.84 13952.420370.5124782.29
River Rch & RM=2300,147,17163.65
 4151.65 7357.5710648.1313967.2320392.1624810.22
River Rch & RM=2300,147,16918.51
 4152.09 7358.5410649.69 13969.520395.4724814.52
River Rch & RM=2300,147,16673.38
 4183.04 7426.0710759.5214127.95 20626.825113.04
River Rch & RM=2300,147,16428.24
 4270.72 7612.2111058.3614555.0821250.4225901.22
River Rch & RM=2300,147,16183.11
 4271.27 7613.4511060.3914558.0421254.7325906.85
River Rch & RM=2300,147,15937.97
 4274.86 7621.6411074.0214578.0221283.9225945.55
River Rch & RM=2300,147,15692.84
 4275.84 7623.8911077.7414583.4821291.88 25956.1
River Rch & RM=2300,147, 15447.7
 4277.22 7627.08 11083.114591.3921303.4325971.57
River Rch & RM=2300,147,14957.43
 4280.24 7634.0911094.8114608.6621328.6526005.32
River Rch & RM=2300,147,14173.11
 4284.85 7644.8811112.9614635.4921367.82   26058
River Rch & RM=2300,147,14047.45
 4285.16  7645.611114.1714637.2821370.4326061.52
River Rch & RM=2300,147,13480.31
 4306.99 7695.1511196.3114757.5921546.0826293.54
River Rch & RM=2300,147,12496.44
  4319.1 7724.4311246.2114832.1221654.8926442.42
River Rch & RM=2300,147,11758.55
 4620.95 8331.89 12196.1 16162.823597.6928774.54
River Rch & RM=2300,147,11266.62
 4622.39 8335.5312202.4416172.4323611.7528794.12
River Rch & RM=2300,147,11095.14
 4623.02 8337.1512205.2816176.7423618.04 28802.9
River Rch & RM=2300,147, 10104.1
 4638.77 8377.12 12274.916282.4623772.3929017.96
River Rch & RM=2300,147,8976.276
 7918.6414254.0220852.0127594.8240288.4345378.85
River Rch & RM=2300,147,7301.259
 7936.8214305.3220944.8727739.25 40499.345662.01
River Rch & RM=2300,147,6140.321
 7948.3614339.9521008.8327840.0140646.4145863.53
River Rch & RM=2300,147,5797.654
  7950.914347.9421023.8127863.8440681.2145911.88
River Rch & RM=2300,147,4864.383
 7951.9214351.1821029.8927873.5340695.3645931.56
River Rch & RM=2300,147,4452.013
 7952.4114352.7521032.8527878.2340702.2145941.11
River Rch & RM=2300,147,4227.747
 7954.3614358.9421044.4827896.7540729.2645978.77
River Rch & RM=2300,147,3405.791
 7956.4314365.6121057.0627916.8440758.5946019.77
River Rch & RM=2300,147,2189.437
 7959.7114376.1821077.0427948.7440805.16 46084.9
River Rch & RM=2300,147,199.6259
 7999.7814505.5121321.4528339.4741375.6346883.79
Boundary for River Rch & Prof#=2300,147,1
Up Type= 0
Dn Type= 2
Boundary for River Rch & Prof#=2300,147,2
Up Type= 0
Dn Type= 2
Boundary for River Rch & Prof#=2300,147,2
Up Type= 0
Dn Type= 2
Boundary for River Rch & Prof#=2300,147,2
Up Type= 0
Dn Type= 2
Boundary for River Rch & Prof#=2300,147,2
Up Type= 0
Dn Type= 2
Boundary for River Rch & Prof#=2300,147,2
Up Type= 0
Dn Type= 2

--- 2300_ras.g01 (geometry) ---

Geom Title=2300
Program Version=4.10

River Reach=2300,147
Reach XY= 30
573942.614999295743286.164916573574689.008697659742968.498089631
575054.745710196742092.058924463576376.723281979 742449.50384639
576364.699255645742037.779032876575764.601428805741674.605017485
576318.532811223740877.812015127575902.866142868739262.095953196
576733.706231175738494.504906095577024.779325871737415.617224468
577944.867760239 737057.05891351578089.524632214 734160.61772383
576507.364810945734444.405054281576306.337555288733573.540340283
575692.754183679 733409.16008919575250.349221615732645.279232805
575580.281477837732264.717554291575540.122076305730956.154678918
577565.357697995728056.245143321577696.600922076 725703.95366538
580046.681633324723867.920211878580588.424539865722711.780117166
581377.771079571722162.817132196581612.399533181720326.349498748
   582213.512813720058.176205075586118.444156766715640.370529117
585415.316625148713568.410730354585827.677310941711538.155054285
584971.661644966710753.536313507585107.191199841709946.141165403

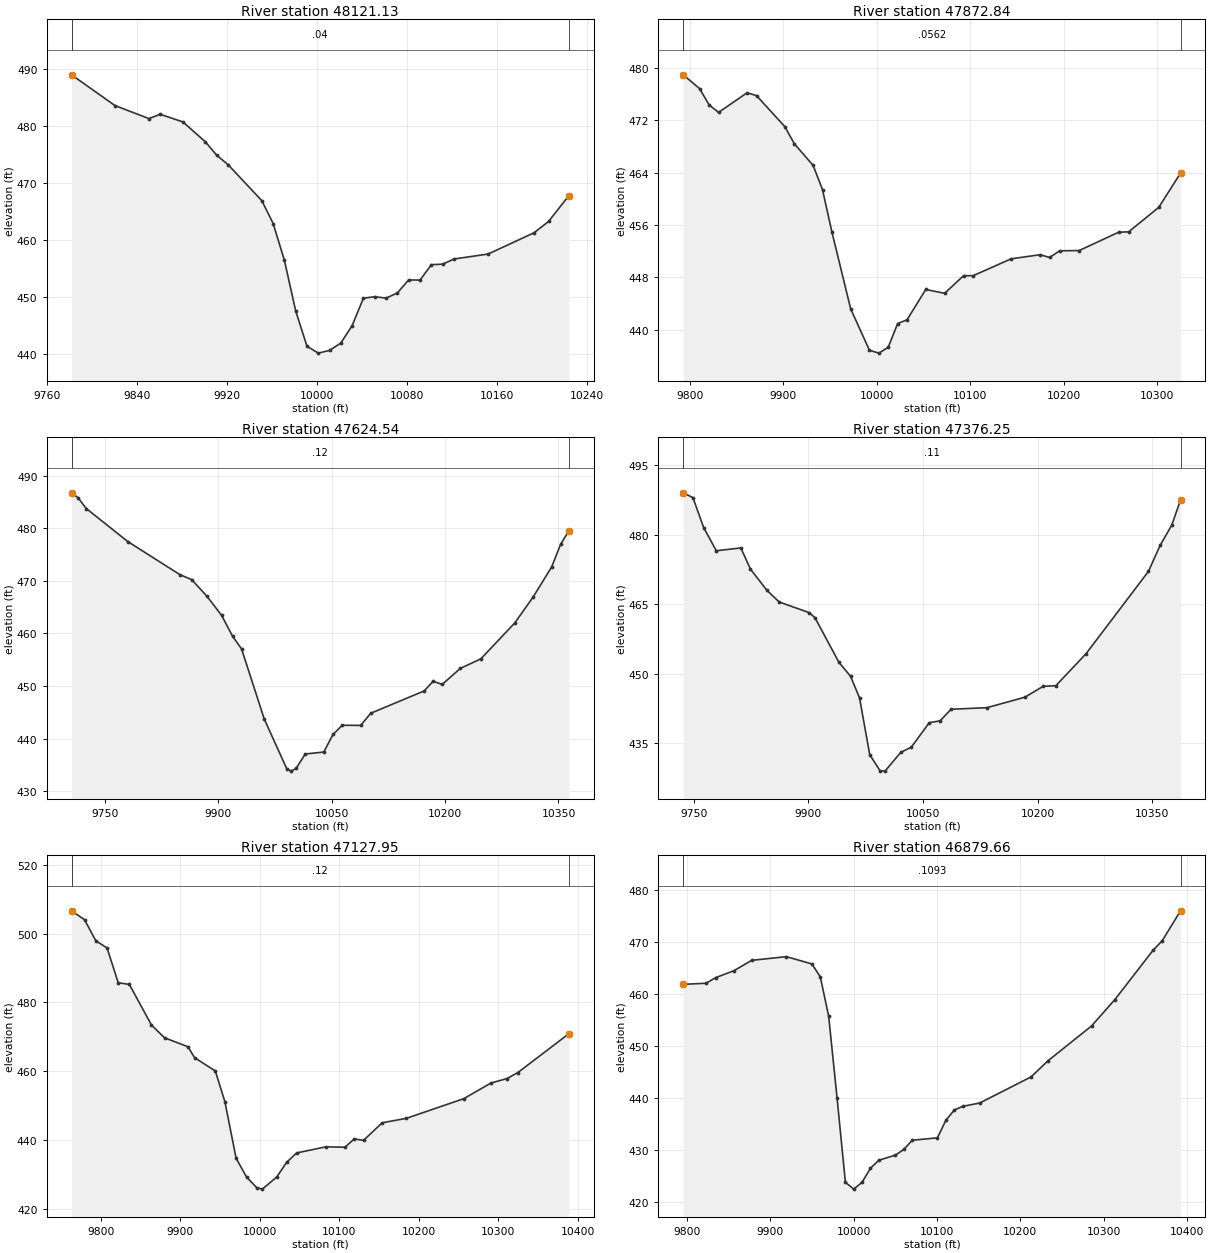
Type RM Length L Ch R = 1 ,48121.13,248.295300,248.295300,248.295300
XS GIS Cut Line= 6
573964.404112587743503.254964575 573951.98346799743402.431484312
 573938.52877097743220.049238349573926.068592833743132.321442794
573915.613311946 743082.47012174573910.852176824743065.018322118
#Sta/Elev= 30
9781.797488.92929820.341483.54839850.567481.25299860.643 482.0049880.794  480.67
9900.859477.16539910.885474.80759920.911473.17949950.989466.84649961.015462.8503
9971.041456.38039981.067447.49939991.093441.318910001.12440.113510011.15440.5885
10021.18441.885310031.21444.928310041.24449.746210051.27450.0134 10061.3449.7619
10071.36450.647610081.46452.962810091.56452.915410101.66455.628210111.76455.7197
10121.86 456.62710152.16457.4972   10193461.229910205.81463.205310223.89467.7408
#Mann= 3 , 0 , 0
9781.797    0.04       09781.797    0.04       010223.89    0.04       0
#XS Ineff= 2 , 0
       0                               0
Bank Sta=9781.797,10223.89
Exp/Cntr=0.3,0.1

Type RM Length L Ch R = 1 ,47872.84,248.295300,248.295300,248.295300
XS GIS Cut Line= 6
574218.554296224743482.365908385574203.222802375743389.148462439
574186.573621096743222.378791618574172.149707461743137.664916569
574142.071894121743034.062719892574113.260585361742963.814117841
#Sta/Elev= 30
9792.848478.97649810.448476.86369820.582474.36759830.716473.22439861.119476.2262
9871.254475.79859901.564471.04479911.633468.44229931.771465.1228 9941.84461.4136
9951.904454.92129971.975443.17289992.047  436.8410002.08436.401110012.12437.2922
10022.17440.915610032.21441.4983 10052.3446.136710072.49445.5532 10092.7448.2456
10102.85448.243710143.64450.829810174.58451.453310184.89451.034510195.35452.0545
10216.35452.095410258.55454.896710269.28454.958510301.49458.704510324.78463.9446
#Mann= 3 , 0 , 0
9792.848  0.0562       09792.848  0.0562       010324.78  0.0562       0
#XS Ineff= 2 , 0
       0                               0
Bank Sta=9792.848,10324.78
Exp/Cntr=0.3,0.1

Type RM Length L Ch R = 1 ,47624.54,248.295300,248.295300,248.295300
XS GIS Cut Line= 6
574568.241467317743452.531799458574529.340578542743374.580223186
574488.544148183743299.753523613574453.574956854743242.341290265
574372.649747166743125.533237462574219.320466873742896.210509755
#Sta/Elev= 30
9706.196486.71759714.613485.80819725.789483.7219 9780.64477.44469849.785471.1368
9865.054470.22289885.353467.03599904.577463.42749919.233459.42489930.942457.0595
9961.021443.7066 9990.91 434.2129996.606433.810810003.04434.316210015.25437.0674
10039.67437.440610051.89440.7856 10064.1442.526910088.51442.507810101.78444.8107
10172.32449.051510184.29450.889710196.26450.297810220.21453.337910247.26455.1432
10292.32461.996910316.62 466.94610340.92472.616810353.06477.001610363.74479.4923
#Mann= 3 , 0 , 0
9706.196    0.12       09706.196    0.12       010363.74    0.12       0
#XS Ineff= 2 , 0
       0                               0
Bank Sta=9706.196,10363.74
Exp/Cntr=0.3,0.1

Type RM Length L Ch R = 1 ,47376.25,248.295300,248.295300,248.295300
XS GIS Cut Line= 6
 574780.61123581743245.535013946574711.322749221743152.905817267
574651.627965708743081.230759665574591.728193479743015.152625815
574468.683839142742895.976684778574331.486227728742777.523483733
#Sta/Elev= 30
9736.331489.03449749.067487.99219763.076481.55159779.647476.54299811.773 477.146
9824.314472.58949845.929467.99369861.902465.49429901.353463.1864 9908.78462.1039
9940.031452.49529955.268449.47849967.032444.82299980.421432.56629993.811 429.112
10000.36429.016910021.03433.070410034.71434.165110058.29439.461310072.52439.8631
10086.74442.356610133.86442.703810183.54444.966110207.32447.306910223.91447.4359
10263.54454.361510345.04 472.08310360.34477.688510375.64482.086110387.09487.5022
#Mann= 3 , 0 , 0
9736.331    0.11       09736.331    0.11       010387.09    0.11       0
#XS Ineff= 2 , 0
       0                               0
Bank Sta=9736.331,10387.09
Exp/Cntr=0.3,0.1

Type RM Length L Ch R = 1 ,47127.95,248.295400,248.295400,248.295400
XS GIS Cut Line= 6
574956.323851475743016.999163745574904.554916242742964.096018624
574848.430795528742912.504508857574738.295250108   742823.902537
574641.185525514742761.751651955574448.541726924742658.095131528
#Sta/Elev= 30
9763.283506.68879779.647504.09879793.903497.95089807.978495.88359822.008485.7574
9836.039485.25429863.869473.43389880.301469.72169909.853467.09829918.028463.9365
9944.187460.06099956.212451.13269970.347434.65539983.426429.19349996.305 426.075
10003.36425.653310021.46429.1862   10034433.467110046.53436.191810083.14437.9648
10107.32437.866810119.02440.270110130.71439.858910154.11444.968810184.52446.2633
10256.79451.989710290.85456.534710311.15457.847210324.92459.607710389.03470.9116
#Mann= 3 , 0 , 0
9763.283    0.12       09763.283    0.12       010389.03    0.12       0
#XS Ineff= 2 , 0
       0                               0
Bank Sta=9763.283,10389.03
Exp/Cntr=0.3,0.1

Type RM Length L Ch R = 1 ,46879.66,248.295300,248.295300,248.295300
XS GIS Cut Line= 6
575088.804699448742699.625971856575032.379473178742670.142277819
 574967.30047077742650.344105552 574849.55325965742640.355263011
574727.493144859742621.462145165574514.136233645742556.814494206
#Sta/Elev= 30
9795.408461.91859822.932462.12989834.264463.20169856.263464.53979877.575466.5356
9919.292467.24829949.837465.84149959.972463.35169970.018455.75439980.039440.0885
 9990.06423.825210000.08 422.50710010.09423.8303 10020.1426.513410030.11428.0585
10050.15429.054810060.23430.1518 10070.3431.917510100.52432.376910110.64435.7557
10120.81437.735810130.99438.438210151.33439.084310212.89444.104110233.49447.2443
10285.57453.919810313.53458.996710359.48468.510610370.12470.2705 10392.3476.0654
#Mann= 3 , 0 , 0
9795.408  0.1093       09795.408  0.1093       0 10392.3  0.1093       0
#XS Ineff= 2 , 0
       0                               0
Bank Sta=9795.408,10392.3
Exp/Cntr=0.3,0.1

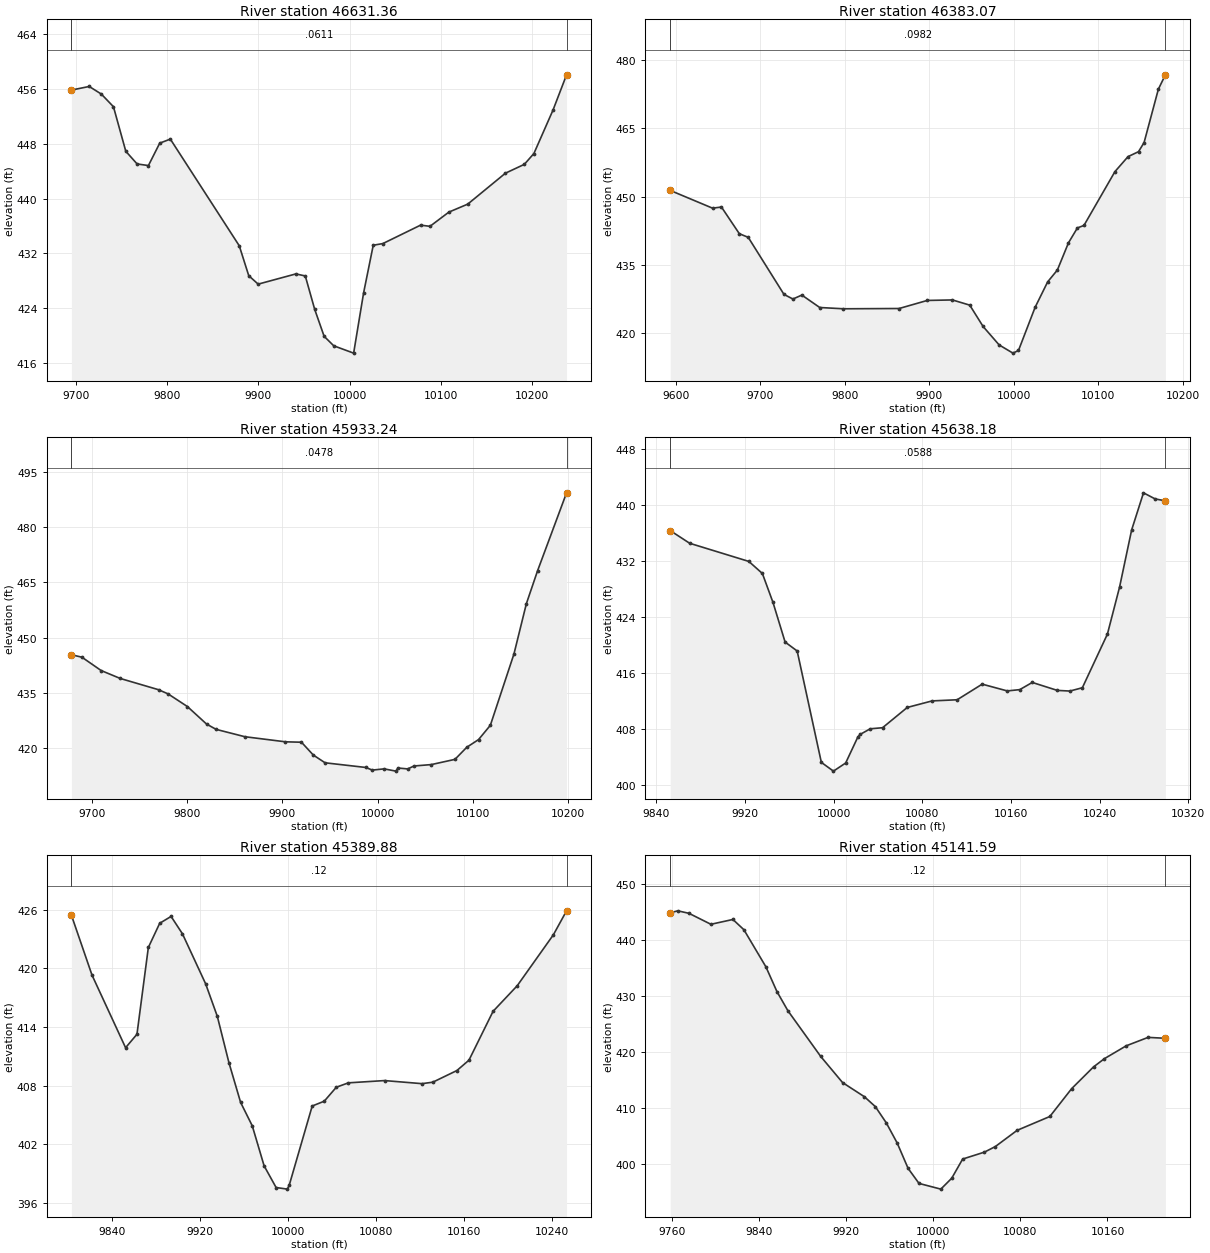
Type RM Length L Ch R = 1 ,46631.36,248.295300,248.295300,248.295300
XS GIS Cut Line= 6
575155.519045723742530.106410121575117.773896167742488.612498225
575083.146416883742463.165330327575037.292765629742441.117885589
574855.089406704742383.970495444574660.897167866 742330.20952841
#Sta/Elev= 30
9695.052455.82769714.564456.3516 9727.78 455.2519741.136453.40099754.678 446.903
9767.088445.05479779.498444.82129791.908448.09179803.526448.67589879.098433.1262
9889.507428.76419899.841427.53019941.177429.02129951.511428.72259961.845423.8476
9972.179419.92239982.717418.539810004.54417.470910015.48426.266810026.03433.2015
10036.57 433.44510077.93436.131210088.27435.961110108.95438.032410129.64439.1956
   10171 443.70910191.72 444.99610202.22446.577710223.22452.926810238.02  458.05
#Mann= 3 , 0 , 0
9695.052  0.0611       09695.052  0.0611       010238.02  0.0611       0
#XS Ineff= 2 , 0
       0                               0
Bank Sta=9695.052,10238.02
Exp/Cntr=0.3,0.1

Type RM Length L Ch R = 1 ,46383.07,449.827000,449.827000,449.827000
XS GIS Cut Line= 6
575183.345454247742502.280001603575124.738698226742331.732962573
575073.687410251742235.205322429575036.903427267742201.015321976
574931.545137829742140.006545055574829.353666586742070.105711728
#Sta/Elev= 30
9593.432451.36649643.461447.47279654.033447.71989675.175441.86459685.746441.0556
9728.031428.52349738.602427.50859749.173428.37569770.316425.64599798.437425.3638
9864.263425.42479897.579427.19469927.363427.30869947.867426.16649963.664421.4792
9982.651417.4221    9999415.621210005.55416.203210025.19425.671410040.05431.2723
10051.56433.876810064.71439.855410075.27443.130610083.03443.675310119.69   455.5
10135.18458.791610147.58459.8786 10154.2461.893410171.11  473.6210179.39476.7665
#Mann= 3 , 0 , 0
9593.432  0.0982       09593.432  0.0982       010179.39  0.0982       0
#XS Ineff= 2 , 0
       0                               0
Bank Sta=9593.432,10179.39
Exp/Cntr=0.3,0.1

Type RM Length L Ch R = 1 ,45933.24,295.059000,295.059000,295.059000
XS GIS Cut Line= 3
575252.588663326742525.998662857575276.202202574742334.138656524
575470.030003802742070.454135028
#Sta/Elev= 30
9678.101445.35519689.182444.67719709.333441.06419729.484438.90679769.786435.8482
9779.861434.70019800.012 431.2899820.163426.53459830.239425.08779860.465423.0925
9903.146421.70879919.983421.59749932.394418.11839944.805416.00969987.567414.7454
9994.449414.029610006.86414.359910019.27 413.74910021.33414.595210031.68414.3481
10038.22415.1418 10056.5415.527610081.33416.941110093.74420.220810106.15422.3149
10118.56426.197310143.38445.563610156.41459.2025 10168.2468.156410198.67489.3162
#Mann= 3 , 0 , 0
9678.101  0.0478       09678.101  0.0478       010198.67  0.0478       0
#XS Ineff= 2 , 0
       0                               0
Bank Sta=9678.101,10198.67
Exp/Cntr=0.3,0.1

Type RM Length L Ch R = 1 ,45638.18,248.295300,248.295300,248.295300
XS GIS Cut Line= 6
575525.259214945 742551.40383812575549.815729044742485.747678541
575580.188620347742415.776659143 575615.44422217742342.888608591
575693.964282935742193.390149846575711.940943386742146.255514261
#Sta/Elev= 30
9852.623436.38759870.137434.57959923.536431.98459935.741 430.2629945.339426.1161
9956.241 420.4659967.142419.18329988.945403.26739999.856 402.01910010.88403.1781
10021.91406.908410023.88407.259410033.03408.066610044.18408.221810066.47  411.12
10088.88412.053110111.47412.215910134.06414.447210156.65413.480610167.95413.6643
10179.25414.691510201.84413.553810213.13413.461610224.43413.933510247.02421.5939
10257.98428.303410268.88 436.47710279.58441.787710290.12440.913910299.33440.6463
#Mann= 3 , 0 , 0
9852.623  0.0588       09852.623  0.0588       010299.33  0.0588       0
#XS Ineff= 2 , 0
       0                               0
Bank Sta=9852.623,10299.33
Exp/Cntr=0.3,0.1

Type RM Length L Ch R = 1 ,45389.88,248.295300,248.295300,248.295300
XS GIS Cut Line= 6
575760.188658514 742683.40675998575768.529743061742637.171026266
575783.373260677742580.197729367575803.953474175742521.318721946
575814.873316855742495.885889295575918.670006109742264.057646208
#Sta/Elev= 30
9803.093425.42069821.796419.29529852.318 411.8659862.652413.24559872.986422.1198
 9883.32424.59749893.653425.29789903.987423.51739925.049418.40399935.643415.0819
9946.236 410.3289956.829406.27289967.422403.87349978.199399.77669989.081 397.564
9999.306397.3986   10001397.798910021.89405.902810032.84406.3955 10043.8407.8236
10054.76408.272510087.63408.504310121.65408.189310131.45408.338410153.36 409.531
10164.32410.590310186.23415.588810208.15418.203310241.02423.4172   10253425.8705
#Mann= 3 , 0 , 0
9803.093    0.12       09803.093    0.12       0   10253    0.12       0
#XS Ineff= 2 , 0
       0                               0
Bank Sta=9803.093,10253
Exp/Cntr=0.3,0.1

Type RM Length L Ch R = 1 ,45141.59,204.842000,204.842000,204.842000
XS GIS Cut Line= 6
576078.714512835742791.799957661576063.700119073742691.327510414
576057.315300323742619.125612121576053.157063259742551.035404879
576052.612553691742464.199877883576059.727344782742339.136264051
#Sta/Elev= 30
9758.686444.81379765.619445.16629775.813 444.7259796.015442.76519816.207 443.625
9826.303441.79019846.495 435.1739856.591430.77119866.651427.34779896.769419.1957
9916.847414.52969936.916 412.0019946.935410.23839956.954407.34949966.972403.7514
9976.991399.2261 9987.01396.540410007.04395.522510017.05397.472310027.06400.8879
10047.06402.123710057.06403.115510077.06406.010210107.09408.480110127.12413.4505
10147.16417.319510157.17418.7963 10177.2421.089210197.24422.589510213.13422.4325
#Mann= 3 , 0 , 0
9758.686    0.12       09758.686    0.12       010213.13    0.12       0
#XS Ineff= 2 , 0
       0                               0
Bank Sta=9758.686,10213.13
Exp/Cntr=0.3,0.1

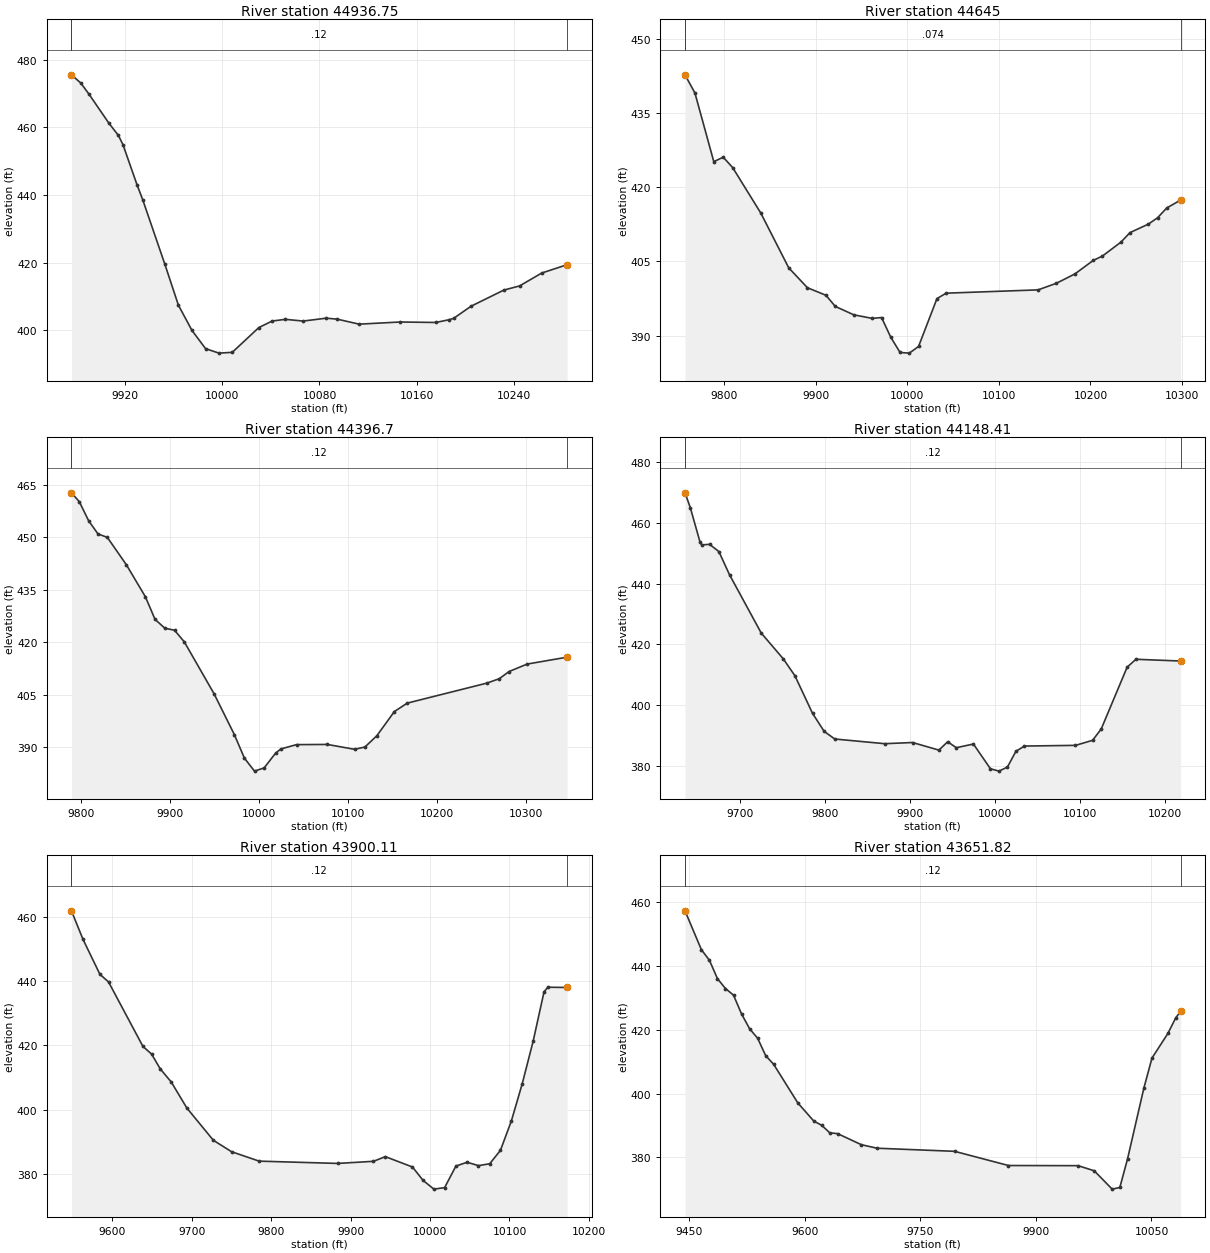
Type RM Length L Ch R = 1 ,44936.75,291.748700,291.748700,291.748700
XS GIS Cut Line= 6
576314.948560668742631.382115426576278.510708937742569.683466636
576212.632878468742432.755068477576189.303706056742399.902447508
   576149.506401 742356.35094138576082.819958698742303.789609673
#Sta/Elev= 30
9875.741 475.4829883.342473.09219890.304469.70539906.644461.15179914.402457.5751
9918.187454.82289929.731442.98669934.421438.56689952.644419.51029963.818407.3828
9974.992399.92359986.165394.54939997.175393.214110008.15393.445410030.04 400.767
10040.98402.696410051.91403.203510066.53402.694210085.49403.544810094.52403.2633
10112.63401.779510146.38402.417510175.77402.274910187.02403.112610190.59403.5226
10204.81407.081710231.76411.843510244.77413.079610262.95416.882810283.86419.3492
#Mann= 3 , 0 , 0
9875.741    0.12       09875.741    0.12       010283.86    0.12       0
#XS Ineff= 2 , 0
       0                               0
Bank Sta=9875.741,10283.86
Exp/Cntr=0.3,0.1

Type RM Length L Ch R = 1 ,   44645,248.295300,248.295300,248.295300
XS GIS Cut Line= 6
576625.519694507742348.834254608576563.549453557742333.710964397
576484.972621977742318.279322758576380.229250282742302.718369529
576332.599923134742297.525649503576089.910701811742277.138365164
#Sta/Elev= 30
9757.264442.74869768.092439.06739788.679425.17879798.973426.08259809.266423.9884
9839.957414.7959 9870.53403.69239890.912399.67059911.214398.13999921.325 395.893
9941.546394.18959961.768393.46229971.878393.63969981.989389.6426  9992.1386.5701
10002.21386.437210012.28387.7862 10032.4397.472310042.46398.569210142.84399.2358
10162.91400.578810182.98402.456410203.06405.199110213.09406.079710233.16408.8771
 10243.2410.824610263.27412.5424 10273.3413.831710283.34 415.80810298.48417.4134
#Mann= 3 , 0 , 0
9757.264   0.074       09757.264   0.074       010298.48   0.074       0
#XS Ineff= 2 , 0
       0                               0
Bank Sta=9757.264,10298.48
Exp/Cntr=0.3,0.1

Type RM Length L Ch R = 1 , 44396.7,248.295300,248.295300,248.295300
XS GIS Cut Line= 6
576573.388092279741977.018875465576437.583676308742030.848603174
576345.621792883742084.010233119576278.251044005742138.367732525
576172.735548496742238.453741521576100.761396259742251.096698493
#Sta/Elev= 30
 9788.98462.7618 9797.77460.24979808.309454.78619818.849451.01489829.388450.0194
 9850.72442.23539872.235433.03259882.992426.61779893.989424.07699905.013423.4886
9916.037420.14379949.529405.30939972.244393.68849983.601386.9425 9994.96383.2273
10005.82384.150610018.63388.3495 10024.6389.561610042.29390.802410076.95390.8515
10107.64389.457910119.26390.126310132.64393.343610152.33400.249610166.86402.6638
10256.69408.395410270.47409.652810281.45411.694110301.75413.825610346.67415.7912
#Mann= 3 , 0 , 0
 9788.98    0.12       0 9788.98    0.12       010346.67    0.12       0
#XS Ineff= 2 , 0
       0                               0
Bank Sta=9788.98,10346.67
Exp/Cntr=0.3,0.1

Type RM Length L Ch R = 1 ,44148.41,248.295300,248.295300,248.295300
XS GIS Cut Line= 6
576360.483785935741695.715061043576257.623469681 741766.99442992
576197.345212513 741845.65235621576168.242122059741930.730098285
576156.393174716742096.762893392576130.419000963742195.096805308
#Sta/Elev= 30
9634.702469.93139640.925465.05359652.274453.80069654.344452.75979663.622452.9521
9674.582450.56819687.155442.90449724.484423.69399750.355415.23279764.142409.6282
9784.924397.21619798.602391.28599811.069388.77179869.972 387.2279902.726387.6125
 9933.74385.11229944.064 387.8659954.276385.90669974.401387.11589994.457378.9584
10004.47378.182410014.47379.532710024.48384.725910034.49386.450910094.63386.6752
10114.77388.336910124.92392.073410155.45412.4509 10165.8415.055610218.47414.4803
#Mann= 3 , 0 , 0
9634.702    0.12       09634.702    0.12       010218.47    0.12       0
#XS Ineff= 2 , 0
       0                               0
Bank Sta=9634.702,10218.47
Exp/Cntr=0.3,0.1

Type RM Length L Ch R = 1 ,43900.11,248.295400,248.295400,248.295400
XS GIS Cut Line= 6
576328.722012079741637.485142301576227.896163061741677.442689431
 576091.51420511741751.849077869576035.416517644741794.644294385
 575935.24645515741884.860252675575828.405178584741996.143993789
#Sta/Elev= 30
9548.798 461.8759563.276453.02949584.608442.12019595.441439.75699638.774419.6684
9649.607417.30579660.529412.69049674.459408.57859693.946400.52959727.362390.4656
9750.222386.91029784.989383.96979883.911383.25929928.854383.91589943.835385.3719
9977.947382.14439991.377 377.95310004.91375.259110018.39375.723410032.61382.4377
10046.68383.619710061.02382.569810075.15383.156510088.63387.332410102.35396.4411
10116.06408.056710129.77421.260110143.49 436.64310148.23438.090610172.48438.0236
#Mann= 3 , 0 , 0
9548.798    0.12       09548.798    0.12       010172.48    0.12       0
#XS Ineff= 2 , 0
       0                               0
Bank Sta=9548.798,10172.48
Exp/Cntr=0.3,0.1

Type RM Length L Ch R = 1 ,43651.82,248.295300,248.295300,248.295300
XS GIS Cut Line= 6
576315.451708424741613.156252265576154.298011575741660.324075667
576070.135063888741678.881679763 575967.21987781741688.043317361
575824.445237246741684.245100846575688.907217594741727.887479353
#Sta/Elev= 30
9444.706457.32269465.953445.12459476.378 441.8199486.802436.04919497.226432.9565
 9507.65430.87899518.074424.98199528.499420.34889538.923417.37299549.347411.9265
9559.771409.18099591.044397.09869611.893391.37959622.197390.05699632.493 387.716
9642.789387.44469673.507383.98859693.879382.88199794.441381.90979864.479377.4561
9954.812377.40799975.718375.8053    9999370.052410008.96370.563210018.98379.5341
10040.15401.726410050.69411.1565 10071.4418.895710081.67423.837810087.87425.7624
#Mann= 3 , 0 , 0
9444.706    0.12       09444.706    0.12       010087.87    0.12       0
#XS Ineff= 2 , 0
       0                               0
Bank Sta=9444.706,10087.87
Exp/Cntr=0.3,0.1

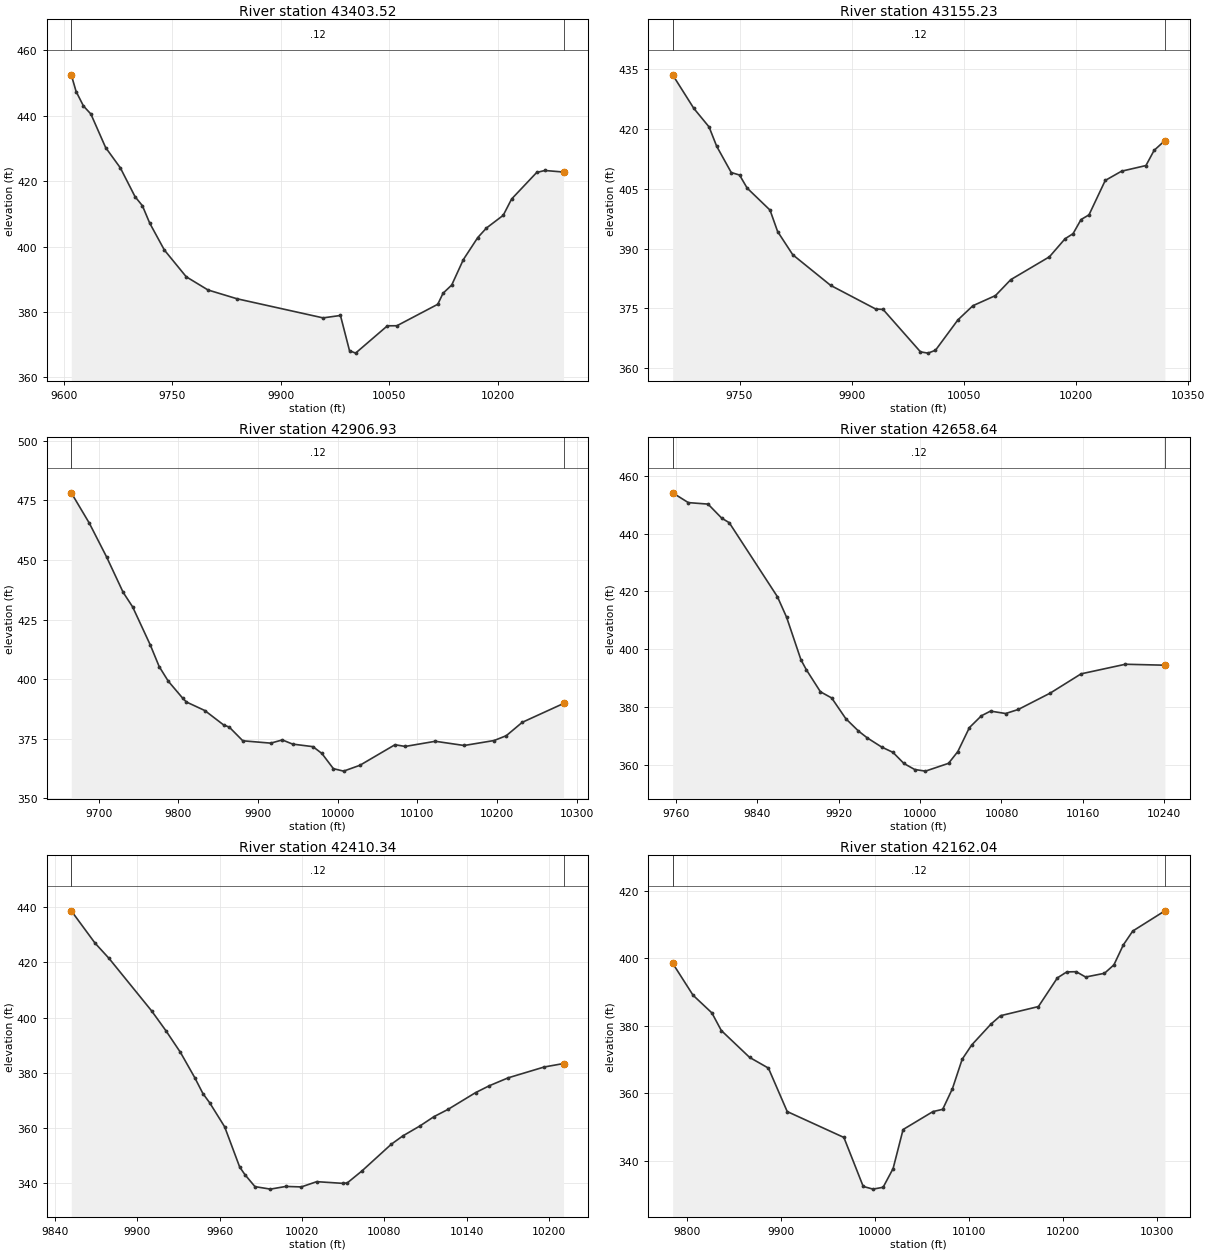
Type RM Length L Ch R = 1 ,43403.52,248.295300,248.295300,248.295300
XS GIS Cut Line= 6
576301.542965959741587.656891076576119.639905096741615.988455801
576031.585331665741606.227258401575964.200789799741574.332805465
575835.100010105741470.630677059575692.118111555741385.219521723
#Sta/Elev= 30
9610.608 452.5579617.284447.45169627.487443.01349637.691440.57079658.097430.3068
9678.497424.07729698.756415.28549708.886412.53219719.015 407.1979739.274 398.969
9769.486390.79079799.555386.75469839.632384.06519958.612378.2168 9982.63378.9579
9995.139368.198810003.55367.4387 10047.5375.792510060.69375.816610117.13382.3813
 10124.4385.7485 10136.4388.264210152.52396.058510172.42 402.79110184.43405.7066
10207.62409.597110219.19414.581710253.83422.690610265.12423.298710290.96422.8226
#Mann= 3 , 0 , 0
9610.608    0.12       09610.608    0.12       010290.96    0.12       0
#XS Ineff= 2 , 0
       0                               0
Bank Sta=9610.608,10290.96
Exp/Cntr=0.3,0.1

Type RM Length L Ch R = 1 ,43155.23,248.295300,248.295300,248.295300
XS GIS Cut Line= 6
576302.785606087741350.086473292576094.964150402 741312.10128194
 575912.08878587741309.965771097575870.981202031741305.208977557
575786.907982696741283.102445048575661.839148684741231.072074289
#Sta/Elev= 30
9660.558433.61759688.873425.19659709.254420.54049719.445415.68969738.925409.0953
9750.017408.46789760.207405.18579790.779399.66059800.931 394.2839821.184388.4595
9871.817380.7741 9931.96374.85049941.968374.73069991.991364.0831   10002363.7678
   10012 364.48310042.02372.111910062.07375.668510092.27 378.21410112.67382.2046
10164.39387.943610185.35392.478610196.01393.753110206.66397.293510217.32398.4738
10239.05 407.11210260.81409.428710293.47410.849910304.35414.650410318.82417.1241
#Mann= 3 , 0 , 0
9660.558    0.12       09660.558    0.12       010318.82    0.12       0
#XS Ineff= 2 , 0
       0                               0
Bank Sta=9660.558,10318.82
Exp/Cntr=0.3,0.1

Type RM Length L Ch R = 1 ,42906.93,248.295300,248.295300,248.295300
XS GIS Cut Line= 6
576346.184051776741263.289581902 576246.09382746741220.060920721
576162.255912775741170.628820856575980.851992465741027.547866955
575905.273143136740973.188613598575830.286165003740928.233179205
#Sta/Elev= 30
9665.435478.17789688.039465.48179709.701451.33769730.562436.44879742.475430.3424
 9764.66414.3652 9775.79405.32969787.228399.18539805.567391.96819810.104390.4379
9833.094 386.8819856.801380.81829863.767379.94589880.834374.18429915.918373.2005
9930.459374.55029943.281372.80549968.926371.72569980.115368.8772 9994.57362.4918
 10007.4361.464810027.86363.913610071.88372.532510084.77371.819910122.54373.9822
10158.76 372.21510196.43374.307710211.68376.3296 10231.7381.930910283.56389.8396
#Mann= 3 , 0 , 0
9665.435    0.12       09665.435    0.12       010283.56    0.12       0
#XS Ineff= 2 , 0
       0                               0
Bank Sta=9665.435,10283.56
Exp/Cntr=0.3,0.1

Type RM Length L Ch R = 1 ,42658.64,248.295400,248.295400,248.295400
XS GIS Cut Line= 6
576416.358458661741122.940768113576302.718032006741036.509479933
576233.438432652740899.341036273576206.404816547740867.866593822
576158.185961732740835.286328253576078.427214929740803.520348729
#Sta/Elev= 30
9756.597454.06629772.001450.6899  9791.4450.17459804.863445.3245 9812.27443.7486
9859.645418.18969868.674411.10679882.767396.43829888.027393.01849901.958385.3739
 9913.01 383.2439926.882376.09869939.344371.82769947.996369.46159962.059366.3202
  9973.3364.45559984.057 360.6179994.648358.542910005.22357.9829 10027.9 360.671
10037.07364.739610048.43373.003310060.26377.096310069.21378.703710084.12377.8733
10096.48379.266210128.08 384.952 10158.3391.571910201.86394.882510240.72 394.553
#Mann= 3 , 0 , 0
9756.597    0.12       09756.597    0.12       010240.72    0.12       0
#XS Ineff= 2 , 0
       0                               0
Bank Sta=9756.597,10240.72
Exp/Cntr=0.3,0.1

Type RM Length L Ch R = 1 ,42410.34,248.295300,248.295300,248.295300
XS GIS Cut Line= 6
576441.935321313740690.182486146576350.243373083 740714.67255265
576257.873948634 740760.12814336576214.212575785740776.055803271
576170.554694518740783.468826229576101.067591201740780.099269819
#Sta/Elev= 30
9851.977438.73139869.241427.05629879.487421.4813 9910.48402.46719920.996395.2102
9931.512387.39799942.028378.14919947.843 372.4959952.758 369.1659963.682 360.441
9974.606345.88779978.384343.14169985.756338.74799997.025337.844310008.28338.8225
10019.52338.645310030.76340.550410050.02339.927510053.08340.129710063.72344.4538
10085.01354.103310093.42357.124710105.94360.755910116.19364.135310126.27366.7225
10146.39372.810410156.39375.3105 10170.2378.195910196.49382.127810210.51383.3717
#Mann= 3 , 0 , 0
9851.977    0.12       09851.977    0.12       010210.51    0.12       0
#XS Ineff= 2 , 0
       0                               0
Bank Sta=9851.977,10210.51
Exp/Cntr=0.3,0.1

Type RM Length L Ch R = 1 ,42162.04,248.295300,248.295300,248.295300
XS GIS Cut Line= 6
576446.662741594740543.621579866576289.958867873740550.115139451
576244.648612285740541.489540519576178.839086858740518.107534031
576103.832013224 740500.75807652575930.880009135740484.823602987
#Sta/Elev= 30
9784.478398.45299806.192388.9776 9826.24383.73869836.264378.51749866.335 370.568
9886.383367.38559906.386354.51269966.685346.84529987.247332.32979997.719331.5337
10008.43332.085410019.05337.627110029.68349.188610061.45354.506210071.82355.1751
10082.18 361.30110092.55370.018510102.78374.266910123.14380.417410133.33382.9072
10173.67385.620110193.83394.110710203.86395.884310213.89395.943810223.91394.3685
10243.97395.4762   10254397.969610264.02403.888610274.05407.991210308.26413.9801
#Mann= 3 , 0 , 0
9784.478    0.12       09784.478    0.12       010308.26    0.12       0
#XS Ineff= 2 , 0
       0                               0
Bank Sta=9784.478,10308.26
Exp/Cntr=0.3,0.1