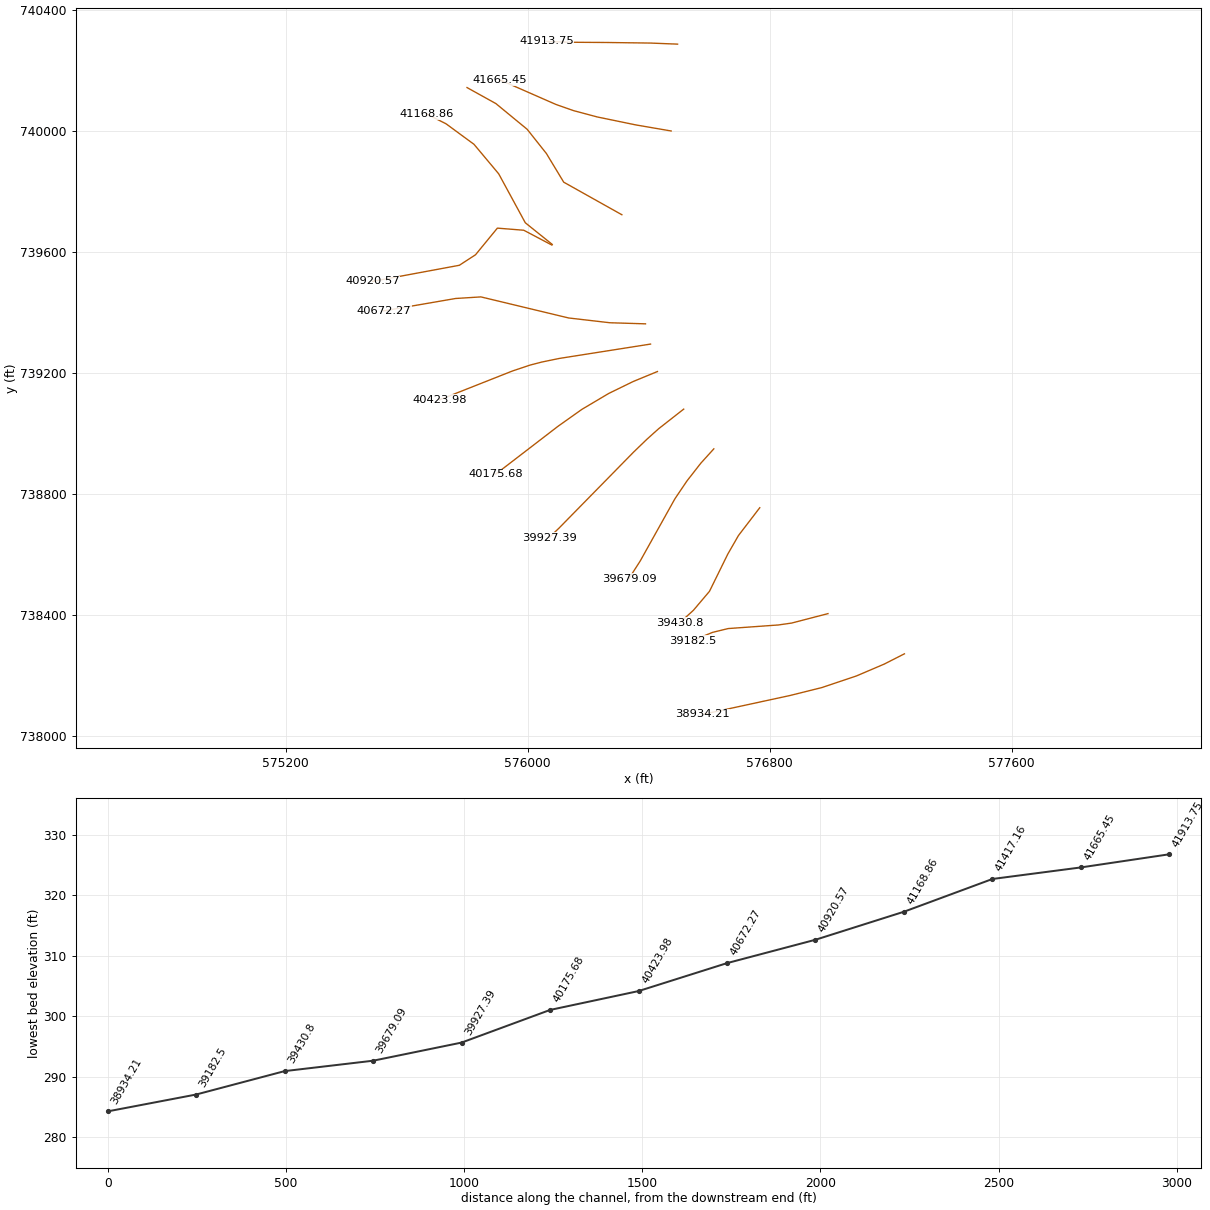
HEC-RAS study 2300_ras.prj: 2300

--- 2300_ras.g01 (geometry) --- (continued)

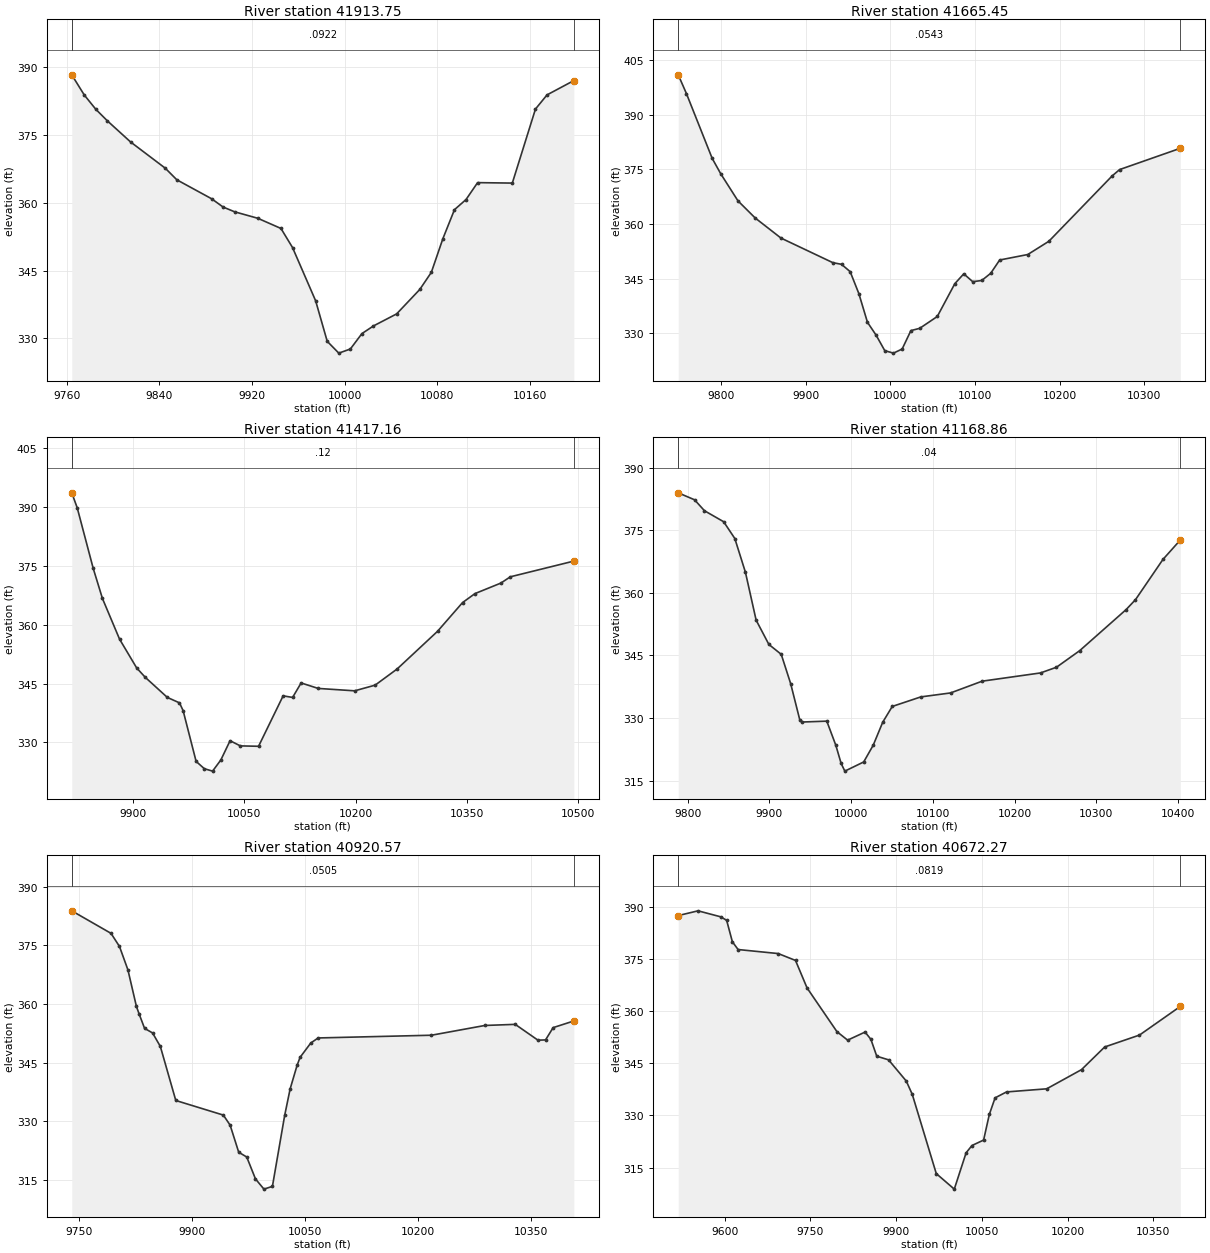
Type RM Length L Ch R = 1 ,41913.75,248.295300,248.295300,248.295300
XS GIS Cut Line= 6
576495.761763274740285.851716062576406.387270295740289.416083767
576261.011919394740291.321353107576143.388090818740292.054175904
576072.838948896740294.387929069576061.876477333740295.321630581
#Sta/Elev= 30
9764.167 388.2389774.937 383.7959784.945380.62669794.953378.06839814.969373.4129
9844.993367.6081    9855365.04269885.002360.86369895.003359.02339905.004357.9689
9925.006356.54069945.007354.29349955.008350.0794 9975.01338.29789985.011329.3554
9995.012326.744610005.01327.654210015.01331.061510025.01332.754910045.01335.4109
10065.01340.807310075.01344.588210085.01352.040510095.01358.438510105.01360.6822
10115.01 364.41710145.03364.316710165.04380.677910175.05 383.80610198.22386.9668
#Mann= 3 , 0 , 0
9764.167  0.0922       09764.167  0.0922       010198.22  0.0922       0
#XS Ineff= 2 , 0
       0                               0
Bank Sta=9764.167,10198.22
Exp/Cntr=0.3,0.1

Type RM Length L Ch R = 1 ,41665.45,248.295400,248.295400,248.295400
XS GIS Cut Line= 6
576474.504833647739998.813590643576357.117881319740018.981744586
576229.675277366740045.305797289576151.472468935740066.236954227
576093.977156466740086.380008815575909.389929901740167.329655966
#Sta/Elev= 30
 9749.76 400.9259759.404395.79799789.844377.9999 9799.99 373.7579820.283366.3463
9840.576361.6534 9871.03356.13919932.296349.38929942.507348.93869952.718346.9241
 9962.93340.93099973.141333.02979983.352329.49849993.563325.2543 10003.8324.5728
10014.08325.698910024.42330.7549 10034.8331.375310055.55 334.62210076.31343.6441
10086.82346.324510097.42344.169410108.02344.501310118.61346.472410129.21 350.121
10162.35351.625110187.25355.254410261.95 373.186 10270.8374.932810342.44380.7684
#Mann= 3 , 0 , 0
 9749.76  0.0543       0 9749.76  0.0543       010342.44  0.0543       0
#XS Ineff= 2 , 0
       0                               0
Bank Sta=9749.76,10342.44
Exp/Cntr=0.3,0.1

Type RM Length L Ch R = 1 ,41417.16,248.295300,248.295300,248.295300
XS GIS Cut Line= 6
576311.567839564739721.945278408576119.335570058739829.652023826
576062.198976049739924.222539186575998.622208783740004.354296815
575895.188570951740089.370880942575799.754770152740142.325145845
#Sta/Elev= 30
9817.105393.65949824.434389.84939846.046 374.3759858.455366.7151 9881.55356.3367
9904.645348.98869916.192 346.6029946.036341.46189962.382340.08319967.293338.1003
9984.811325.15429995.935323.277810007.02322.664910018.19325.513810030.62330.4244
10044.48329.103710069.05329.003810102.18341.865110114.98341.468410126.47345.1587
 10149.5343.762110198.65343.150810226.28344.597610255.91348.716410310.43358.3302
10344.24365.669610360.98367.956310395.92370.637910408.66372.237410494.31376.2453
#Mann= 3 , 0 , 0
9817.105    0.12       09817.105    0.12       010494.31    0.12       0
#XS Ineff= 2 , 0
       0                               0
Bank Sta=9817.105,10494.31
Exp/Cntr=0.3,0.1

Type RM Length L Ch R = 1 ,41168.86,248.295300,248.295300,248.295300
XS GIS Cut Line= 6
576081.544688891739623.818840963575992.381092877739695.429483196
575904.430710631 739857.29067819575822.793787693739954.775510839
575730.378438445 740022.60193703575665.716953564 740055.10643962
#Sta/Elev= 30
9788.547383.98819808.535382.31499820.616379.69659844.119377.05429857.743373.0367
9870.741364.92959883.799353.46269899.405347.63649914.521345.26189926.044338.2378
9937.128329.60779940.449329.03689970.227329.2453 9981.26323.46969987.787319.1004
9992.293317.260110015.36319.459610027.01323.476610038.65328.9934 10050.3332.7702
10085.24335.0589 10121.6 336.00710160.25338.829810231.61340.804510251.14 342.171
10279.46346.135410336.31355.995410347.76358.3718 10381.3368.009610402.57372.6772
#Mann= 3 , 0 , 0
9788.547    0.04       09788.547    0.04       010402.57    0.04       0
#XS Ineff= 2 , 0
       0                               0
Bank Sta=9788.547,10402.57
Exp/Cntr=0.3,0.1

Type RM Length L Ch R = 1 ,40920.57,248.295300,248.295300,248.295300
XS GIS Cut Line= 6
576079.957536162739621.886655033575987.377577483739670.723974474
575900.113050046739677.728654164575827.844607904739589.657808511
575774.441351876 739554.93420836575487.675494224739501.665491165
#Sta/Elev= 30
9740.442383.82719792.574378.06679803.814374.70959815.053368.71239826.292359.3893
9829.915 357.4399837.158353.75549847.764352.59129858.107 349.1279878.626335.3098
9941.789331.57359950.795328.99829962.187322.07299972.875320.84599984.431315.2546
9995.699312.634810006.97313.338610023.25331.498910030.51 338.28110039.81344.3473
10043.71346.348710057.91350.009510067.71351.307210218.19352.003310289.16354.5017
10329.49354.7848 10359.7350.735910369.76350.805310379.83353.947510407.35 355.654
#Mann= 3 , 0 , 0
9740.442  0.0505       09740.442  0.0505       010407.35  0.0505       0
#XS Ineff= 2 , 0
       0                               0
Bank Sta=9740.442,10407.35
Exp/Cntr=0.3,0.1

Type RM Length L Ch R = 1 ,40672.27,248.295300,248.295300,248.295300
XS GIS Cut Line= 6
576389.707007678739361.373280572576272.214490777739364.952290183
576135.603198835739380.771176939575845.638246186739450.404768883
575762.051718801739445.161652534575524.564607903739404.172833643
#Sta/Elev= 30
9518.567387.54519553.274 388.9119593.315 387.1689603.327386.16079613.339379.9952
9623.351 377.7659693.612376.60479723.859374.62289744.041366.70769796.293 354.134
 9815.04351.6708 9845.58354.0027 9855.76351.91219866.041347.04549886.704346.0022
9917.698 339.8979928.169336.07379970.215313.246310001.74308.774410022.45319.2408
 10032.7321.334310053.05322.9038 10063.1330.306810073.16335.056210093.16 336.762
10163.51337.6591 10224.4343.179810264.99 349.70810325.88353.132210397.35361.3842
#Mann= 3 , 0 , 0
9518.567  0.0819       09518.567  0.0819       010397.35  0.0819       0
#XS Ineff= 2 , 0
       0                               0
Bank Sta=9518.567,10397.35
Exp/Cntr=0.3,0.1

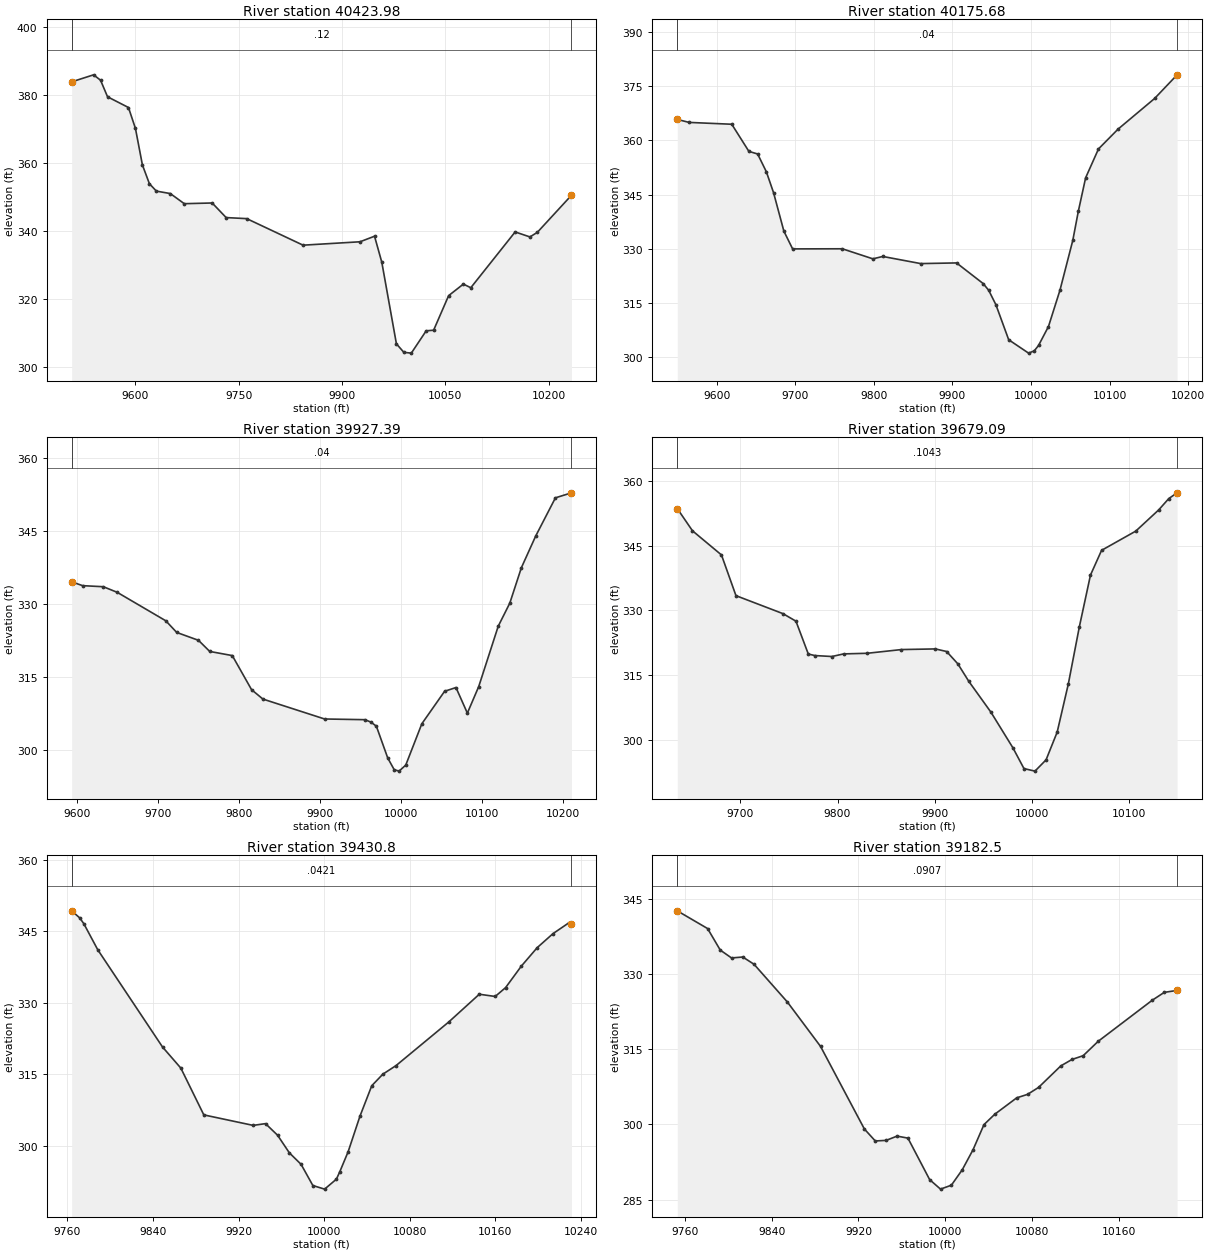
Type RM Length L Ch R = 1 ,40423.98,248.295400,248.295400,248.295400
XS GIS Cut Line= 6
 576406.42670098739294.494507376 576105.10286788739247.071119755
576047.295843602739235.150104744576008.267588821739225.051808431
575949.775799692739205.453030987575708.750613281739110.191103844
#Sta/Elev= 30
9507.781383.82729539.594385.89319549.717384.3048 9559.84379.4442 9590.21376.2936
9600.333370.14459610.456359.41129620.579353.91589630.702351.74389650.948351.0213
9671.194348.04859711.687348.25419731.933343.96859761.814343.6587 9843.55335.8637
9926.143336.86219947.236338.49579957.782330.86099978.995306.88769989.793304.3902
10000.61304.161410022.19310.716810032.98310.893410054.74321.041110076.13324.4348
10086.91 323.36710151.27339.754610172.71338.287810183.43339.626910233.02350.5274
#Mann= 3 , 0 , 0
9507.781    0.12       09507.781    0.12       010233.02    0.12       0
#XS Ineff= 2 , 0
       0                               0
Bank Sta=9507.781,10233.02
Exp/Cntr=0.3,0.1

Type RM Length L Ch R = 1 ,40175.68,248.295300,248.295300,248.295300
XS GIS Cut Line= 6
576429.117101383739203.732905787576349.460457766739170.921180052
 576268.35325277739131.390195879576179.476211828739078.705479007
576099.962055853739022.323931905575894.876104494738864.717224484
#Sta/Elev= 30
9550.001365.80299565.132 364.9769619.318364.4687 9641.12356.94999652.245356.2282
9663.369351.27849672.498345.49759685.619334.84629696.743329.9279 9759.93329.9591
9798.852327.17479811.456327.83049859.737325.85469905.292326.04089939.112320.3288
9946.185  318.469955.368 314.4529971.623304.75199996.921301.045410004.12301.6718
10009.59303.164510022.24308.423910036.81318.448310053.16332.268910060.16340.2912
 10069.5349.628110085.85357.624710110.73363.1102 10157.3371.615610185.88378.1622
#Mann= 3 , 0 , 0
9550.001    0.04       09550.001    0.04       010185.88    0.04       0
#XS Ineff= 2 , 0
       0                               0
Bank Sta=9550.001,10185.88
Exp/Cntr=0.3,0.1

Type RM Length L Ch R = 1 ,39927.39,248.295300,248.295300,248.295300
XS GIS Cut Line= 6
576515.920324174739079.497785965576433.145729522739014.673472541
576394.385974256738979.937078676576350.042416577738937.128341744
576104.612940734738686.988475046576070.701020703738654.456642603
#Sta/Elev= 30
9593.947334.55879607.513333.76879633.006333.55139650.195332.3934 9710.04326.5478
9723.468324.15829750.324322.53759764.195320.25199791.994 319.4029815.762312.3955
9829.751310.46489905.797306.37369955.653306.22929962.998305.72379969.642304.8875
9983.631298.36759991.599295.9546 9997.62295.659210005.87296.900410025.69305.3899
10053.76 312.06610067.79312.835610081.82307.576510095.85313.0463 10119.9325.4451
10134.16330.184310148.41337.455710166.09343.9724 10190.4351.818810210.21352.8452
#Mann= 3 , 0 , 0
9593.947    0.04       09593.947    0.04       010210.21    0.04       0
#XS Ineff= 2 , 0
       09959.264                       0
Bank Sta=9593.947,10210.21
Exp/Cntr=0.3,0.1

Type RM Length L Ch R = 1 ,39679.09,248.295300,248.295300,248.295300
XS GIS Cut Line= 6
576615.544727711738948.227983649 576572.57841135738900.796357934
576526.664883024738842.041552747576486.743822269738782.828875293
576372.343154976738577.766711077576334.908187356738519.286461191
#Sta/Elev= 30
9635.131353.59089650.777348.43069680.606342.82689695.521333.38159743.922329.2049
9757.254327.45569769.945 319.8379776.678319.48279794.252319.26249806.313319.8674
9830.434320.00829865.815 320.8739900.651321.02329912.263320.42259923.785317.5653
9935.126313.48839957.808306.3601 9980.49298.06739991.831293.259810003.16292.6664
10014.58295.284810026.01301.714410037.43312.833910048.85326.178910060.28338.1573
 10071.7343.898410106.88348.358510130.52353.289810140.89355.919610149.41357.2407
#Mann= 3 , 0 , 0
9635.131  0.1043       09635.131  0.1043       010149.41  0.1043       0
#XS Ineff= 2 , 0
       0                               0
Bank Sta=9635.131,10149.41
Exp/Cntr=0.3,0.1

Type RM Length L Ch R = 1 , 39430.8,248.295400,248.295400,248.295400
XS GIS Cut Line= 6
576767.346915331738753.548935475576696.950361153738661.660801373
 576661.60006448738600.125350293576601.216724638738477.346252743
576548.054083024738414.547659774576502.851315879738373.586325664
#Sta/Elev= 30
9764.058349.28659771.599347.80329775.462346.57679788.441341.12889848.983320.7424
9866.111316.31559887.581306.51049933.711304.31059945.244304.67919956.503302.2515
9967.502298.5642  9978.5296.14499989.499291.702810000.48290.949610011.49293.0353
10014.76294.640210022.51298.811210033.53  306.2510044.55312.625310054.92315.0476
10067.26316.848810116.59326.001910145.06331.803510159.91331.335210169.61333.1826
10184.36337.698310199.18341.569210213.99 344.51610228.46346.724210231.23346.5766
#Mann= 3 , 0 , 0
9764.058  0.0421       09764.058  0.0421       010231.23  0.0421       0
#XS Ineff= 2 , 0
       0                               0
Bank Sta=9764.058,10231.23
Exp/Cntr=0.3,0.1

Type RM Length L Ch R = 1 , 39182.5,248.295300,248.295300,248.295300
XS GIS Cut Line= 6
576992.818304919738403.547978843576872.534767456738372.305708534
576828.685449992 738366.03249085576663.071110912738354.189796503
576611.578327626738341.662646062576544.307629025738314.202958192
#Sta/Elev= 30
9753.047342.69529780.988339.1535 9792.65334.85079803.034  333.289813.418333.4658
9823.801332.01249854.479324.47889885.054315.60359925.436 299.1029935.471296.7102
9945.505296.82699955.539297.67929965.565297.27769985.582288.98399995.591287.0856
 10005.6287.873110015.61290.948710025.62294.986210035.63299.975910045.64302.0603
10065.78305.324310075.84306.026710085.91 307.40910106.45311.714210116.74312.9972
10127.03313.747810140.85316.622310190.67324.832310201.74326.401610213.57326.7931
#Mann= 3 , 0 , 0
9753.047  0.0907       09753.047  0.0907       010213.57  0.0907       0
#XS Ineff= 2 , 0
       0                               0
Bank Sta=9753.047,10213.57
Exp/Cntr=0.3,0.1

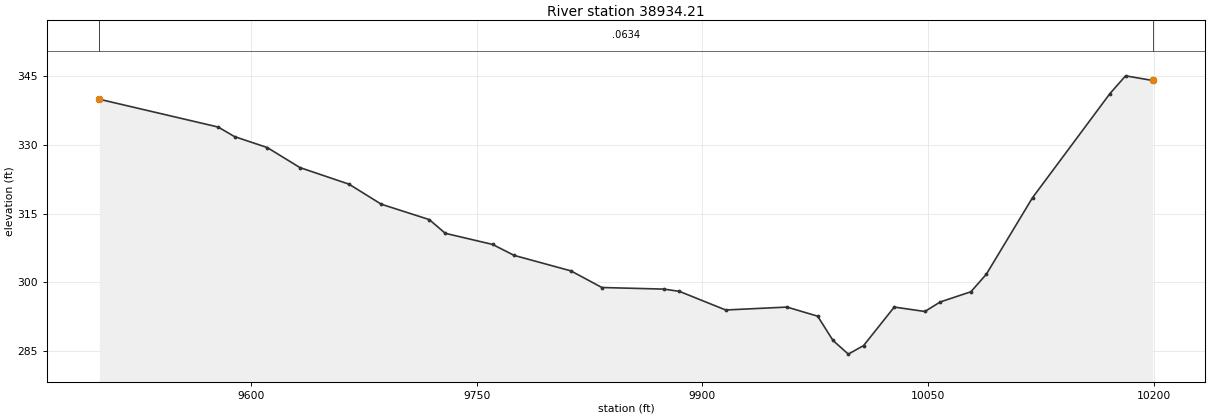
Type RM Length L Ch R = 1 ,38934.21,248.295300,248.295300,248.295300
XS GIS Cut Line= 6
 577245.55219766738270.721676222 577178.90630218738236.805159747
577086.903552204738197.549829973576972.599663007738159.146124055
576866.809340158738132.787427221576577.614266904738070.192700772
#Sta/Elev= 30
9499.002339.98659578.029333.91169588.901331.82149610.645 329.433 9632.39325.0561
9665.006321.43419686.474 317.0559718.395313.69129729.023310.69749760.465308.2687
9774.864305.86859812.559302.49049833.171298.85539874.394298.50669884.699 298.014
9915.484293.9437 9956.26294.58189976.647292.59029986.841287.29139997.035284.3021
10007.21286.177910027.58294.584510047.95293.616510058.13295.692810078.54297.9282
10088.79301.750310119.54318.489310171.01341.2262 10181.4345.100510199.46344.0803
#Mann= 3 , 0 , 0
9499.002  0.0634       09499.002  0.0634       010199.46  0.0634       0
#XS Ineff= 2 , 0
       0                               0
Bank Sta=9499.002,10199.46
Exp/Cntr=0.3,0.1