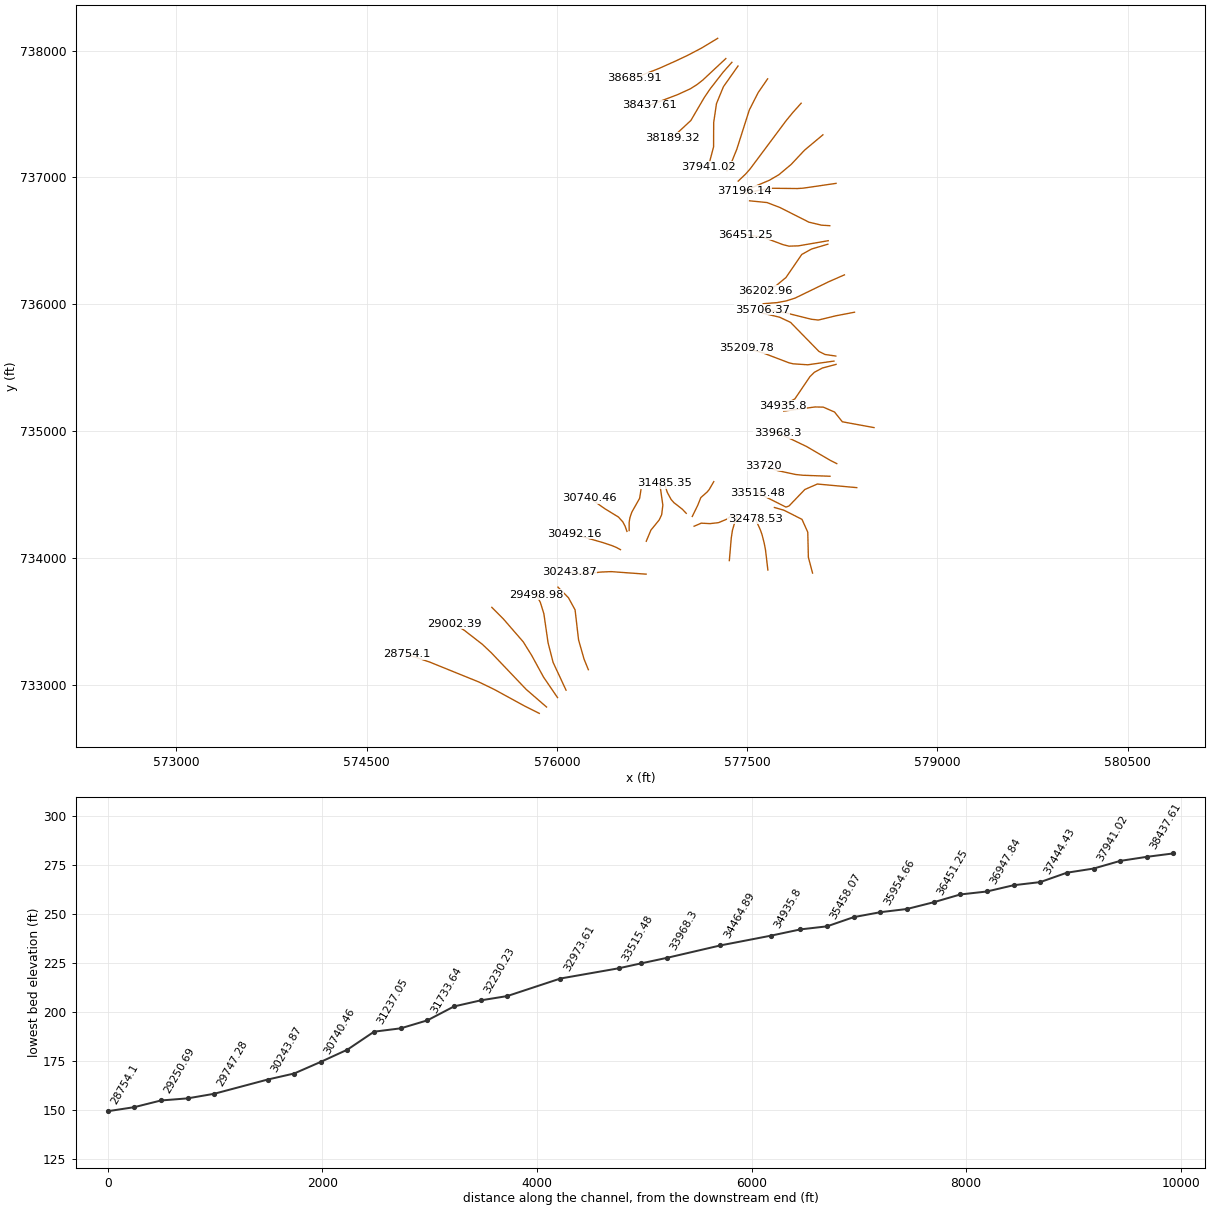
HEC-RAS study 2300_ras.prj: 2300

--- 2300_ras.g01 (geometry) --- (continued)

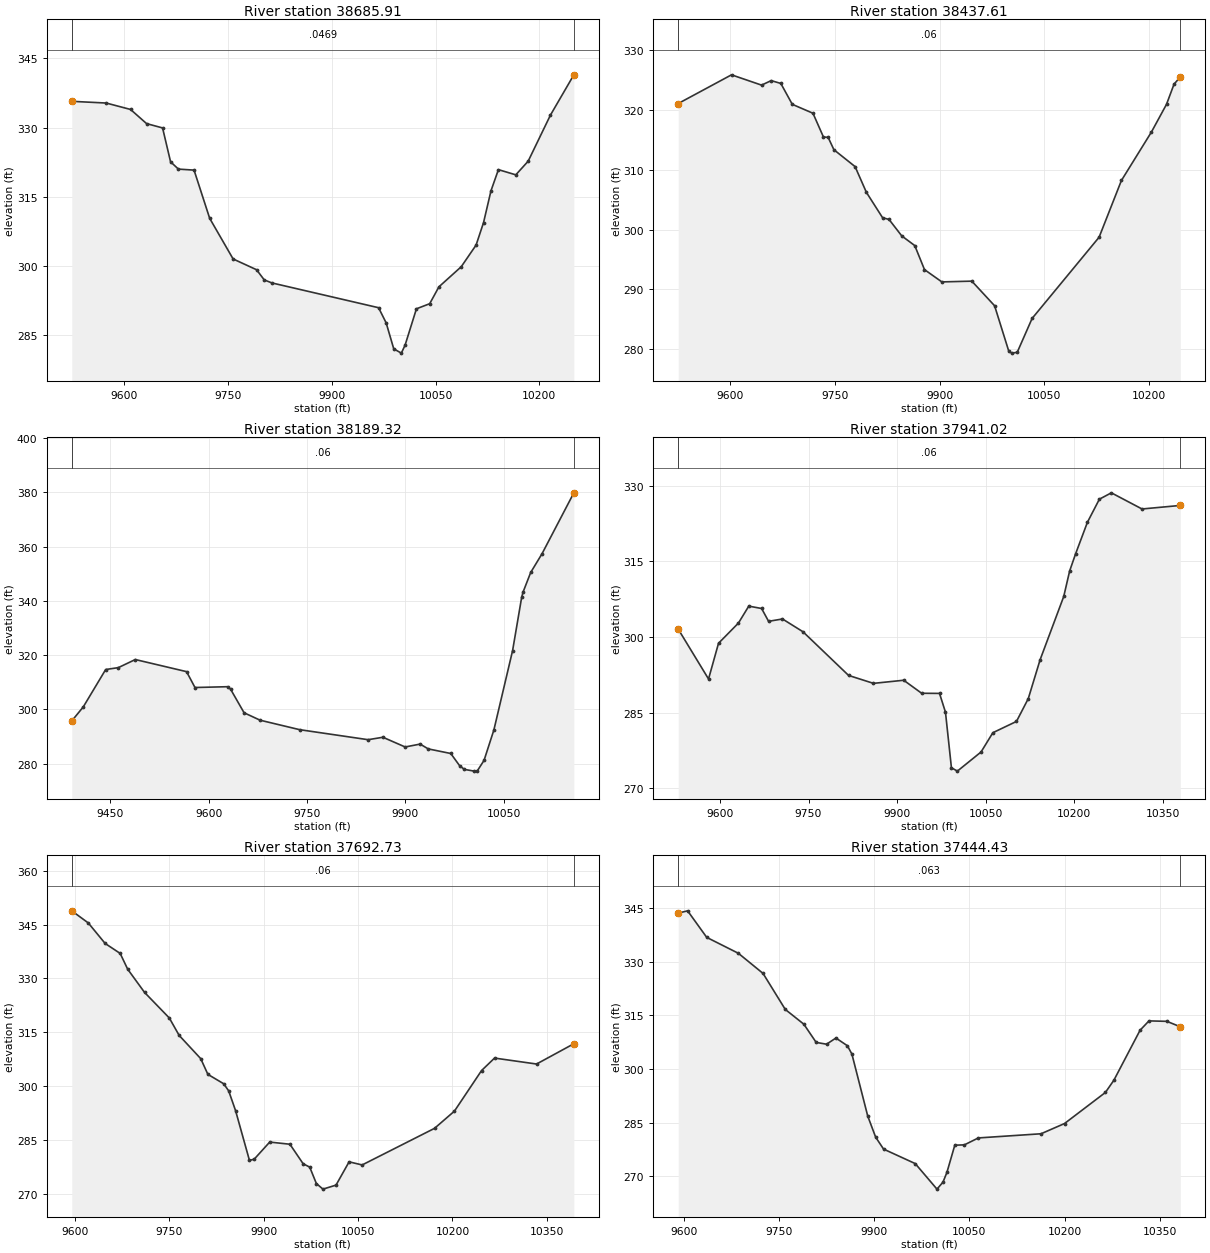
Type RM Length L Ch R = 1 ,38685.91,248.295300,248.295300,248.295300
XS GIS Cut Line= 6
577267.274398025738096.944073288577142.738548502738021.735417797
577032.333757938737963.719383414576933.515060605737917.068480077
576807.431748498737860.772053597576613.553450711  737784.1510607
#Sta/Elev= 30
9523.944 335.7119573.761335.34029608.976333.94719632.117330.88149655.258329.9432
9666.828322.59849678.186321.0162 9700.78320.79939723.373310.34859757.263 301.538
9791.153299.20559802.274297.00319813.333296.34439967.617290.97149978.584287.6797
9989.551282.059410000.53281.126910005.94282.857810022.36 290.73710041.52291.8369
10054.89295.502110087.15299.855810108.65304.558310119.41309.427510130.16316.3163
10140.91320.902410166.06319.776710183.92322.732710216.18332.734110249.99341.4556
#Mann= 3 , 0 , 0
9523.944  0.0469       09523.944  0.0469       010249.99  0.0469       0
#XS Ineff= 2 , 0
       0                               0
Bank Sta=9523.944,10249.99
Exp/Cntr=0.3,0.1

Type RM Length L Ch R = 1 ,38437.61,248.295300,248.295300,248.295300
XS GIS Cut Line= 6
577331.540160764737937.592765194577149.904186209737768.046493329
577105.822463693737733.472991031577051.677892131737699.093301914
576952.229872967737653.581864572576726.683607105737567.596122755
#Sta/Elev= 30
9525.246321.03789601.585325.82759644.641324.10999658.437324.85979672.234324.3919
9688.676320.90399718.322 319.4159733.318315.45219740.065315.38719748.315313.3304
9778.677310.5083 9794.88306.21549818.099301.97269827.288301.69599845.569298.9428
9864.225297.32479878.119293.31979903.001 291.2669945.975 291.3939978.594287.2849
    9999279.674910003.32279.379210011.03279.518310032.36285.172410128.35 298.723
10160.35308.195810203.36316.284510224.95320.904310235.75324.272910244.73325.4779
#Mann= 3 , 0 , 0
9525.246    0.06       09525.246    0.06       010244.73    0.06       0
#XS Ineff= 2 , 0
       0                               0
Bank Sta=9525.246,10244.73
Exp/Cntr=0.3,0.1

Type RM Length L Ch R = 1 ,38189.32,248.295400,248.295400,248.295400
XS GIS Cut Line= 6
577379.349571191737908.093341743577309.596919769 737829.52559151
 577207.28445035737697.647007189577160.707991334737628.808377719
577055.919106954737449.366904138576907.305148023737311.589405299
#Sta/Elev= 30
9391.236295.77939408.745 300.9369442.974314.71589462.234315.41149488.161318.3954
9566.334313.93559579.178308.09059629.208308.38999633.482307.47689654.096 298.783
9678.516296.05329738.886292.56099843.257288.87289865.873289.77059899.796286.1926
9922.637287.25319935.049285.47989969.371283.79019983.033279.24349990.216277.9289
10005.14277.295610010.06277.467310020.15  281.2610035.16292.4688 10063.7 321.691
10077.49341.245910079.65343.228610091.29350.450810108.67357.392410157.13379.7909
#Mann= 3 , 0 , 0
9391.236    0.06       09391.236    0.06       010157.13    0.06       0
#XS Ineff= 2 , 0
       0                               0
Bank Sta=9391.236,10157.13
Exp/Cntr=0.3,0.1

Type RM Length L Ch R = 1 ,37941.02,248.295300,248.295300,248.295300
XS GIS Cut Line= 6
577427.398270856 737878.44627174577312.585515904737715.610428795
577257.859106287737582.615231081577235.745179535737433.382994774
577234.854713219737241.205382159577193.030220026   737083.634308
#Sta/Elev= 30
9529.224301.55019580.562291.66229597.468298.7447 9631.28302.7651 9648.73306.1162
9670.487305.64589682.281303.10299705.868 303.5679740.576301.03179817.826292.3696
9859.974290.79539911.246291.41339941.666288.82899971.906288.80169981.986285.0721
9992.066274.058410002.14273.384310042.26277.181610062.27281.006210102.29283.2444
10122.29287.7727 10142.3295.472510182.35308.028610192.36313.090710202.38316.4715
10222.48 322.75510242.75327.331710263.02328.591210314.99325.386710379.85326.0882
#Mann= 3 , 0 , 0
9529.224    0.06       09529.224    0.06       010379.85    0.06       0
#XS Ineff= 2 , 0
       0                               0
Bank Sta=9529.224,10379.85
Exp/Cntr=0.3,0.1

Type RM Length L Ch R = 1 ,37692.73,248.295300,248.295300,248.295300
XS GIS Cut Line= 6
577660.931874757737777.444330767577586.663401636737669.771389224
577516.870560866737532.884734446577417.901073939737222.562322719
577382.301675863737134.435721515577339.775064851737052.817890584
#Sta/Elev= 30
9595.278348.84229621.535345.46099648.293339.74759672.169336.97039684.107 332.574
9710.899326.10299750.284318.96519765.886314.11569800.159307.63999811.531303.2568
9836.576300.6451 9844.56298.66439855.569293.11129877.588279.26279885.178279.6282
9909.751284.38499941.848 283.782 9962.85278.3458 9973.35277.3958 9983.85272.8349
9994.335271.268110015.09272.386210035.86278.876910056.62278.009610171.64288.2149
10203.26293.018410246.34304.323510266.97307.798510333.72306.139810392.94311.7929
#Mann= 3 , 0 , 0
9595.278    0.06       09595.278    0.06       010392.94    0.06       0
#XS Ineff= 2 , 0
       09909.654                       0
Bank Sta=9595.278,10392.94
Exp/Cntr=0.3,0.1

Type RM Length L Ch R = 1 ,37444.43,248.295300,248.295300,248.295300
XS GIS Cut Line= 6
577925.248460666737585.471059232577860.059987462737512.793147356
577807.401576116737448.690039953577522.273340507737066.566773996
577487.841247229737027.540928339577428.939135327736971.398640445
#Sta/Elev= 30
9591.416343.5119  9606.2344.15419636.302336.74069686.113332.30539725.027326.6807
9760.046316.62939789.301312.50739808.715307.42259825.097306.92559839.802308.6482
 9857.86306.49669864.975304.17629889.926286.86349902.401280.97259914.877277.6447
9964.778273.5939    9999266.469210008.46268.420210014.62271.123310027.07278.7337
10042.17 278.82510064.15280.758610162.88281.920410199.91 284.77810264.27293.4485
10277.61296.849310318.94310.828910332.97313.433310361.11313.305710382.31311.7901
#Mann= 3 , 0 , 0
9591.416   0.063       09591.416   0.063       010382.31   0.063       0
#XS Ineff= 2 , 0
       0                               0
Bank Sta=9591.416,10382.31
Exp/Cntr=0.3,0.1

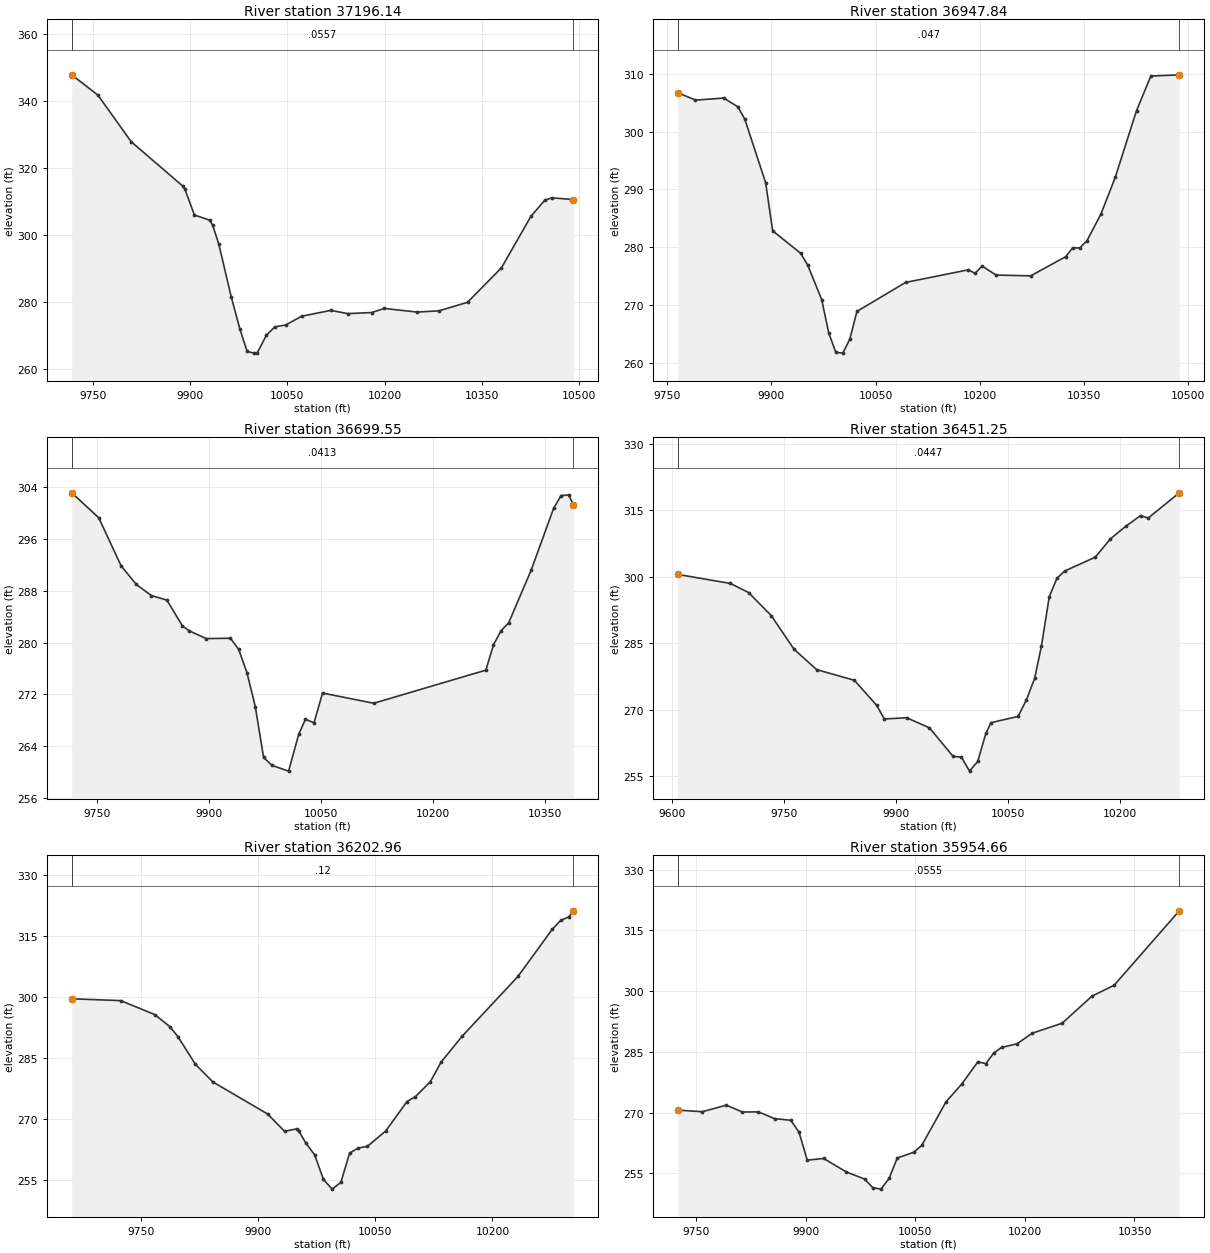
Type RM Length L Ch R = 1 ,37196.14,248.295400,248.295400,248.295400
XS GIS Cut Line= 6
578096.852858949737336.404562628577952.549970558737215.875859587
577846.308683897737102.882885094577749.244093772737021.527437523
577674.536699843736978.188129233577474.244053107736893.085854005
#Sta/Elev= 30
 9717.09347.78049757.471341.73589808.873 327.8559888.496314.63339891.493313.8413
9906.427306.03359930.027 304.472 9934.69302.9333 9944.18297.24869963.254281.6218
9976.475272.13119987.832265.3671    9999264.875610003.54265.016510017.56 270.207
10030.51272.712410047.37273.253810071.81275.866610117.09277.616410142.76276.6499
10180.12276.958610199.45278.190510250.32277.099210284.05277.482910327.91280.0218
10380.24290.278610425.64305.579210447.24310.435410458.04311.137410491.25310.6281
#Mann= 3 , 0 , 0
 9717.09  0.0557       0 9717.09  0.0557       010491.25  0.0557       0
#XS Ineff= 2 , 0
       0                               0
Bank Sta=9717.09,10491.25
Exp/Cntr=0.3,0.1

Type RM Length L Ch R = 1 ,36947.84,248.295300,248.295300,248.295300
XS GIS Cut Line= 6
578200.291241561736953.675969507577941.997180578736915.990101118
577895.498675766736912.889896773577694.827307631736915.116586905
577605.435114003736902.992329452 577485.72577306736873.238880946
#Sta/Elev= 30
9765.067306.73439790.716305.43139831.258305.78579851.416304.30649861.495302.1977
9891.732291.14499901.811282.83299942.127278.94559952.206276.91019972.415270.9325
9982.551265.17499992.686 261.82610002.85261.679710012.98264.114710023.11268.8916
10093.27273.907710183.33276.081910193.34 275.48710203.34276.740410223.36275.1836
10273.39275.042210323.74278.359810333.83279.900110343.97279.865310354.11281.0721
10374.49285.741310394.97292.0515 10425.7303.611310446.29309.588310487.22309.8054
#Mann= 3 , 0 , 0
9765.067   0.047       09765.067   0.047       010487.22   0.047       0
#XS Ineff= 2 , 0
       0                               0
Bank Sta=9765.067,10487.22
Exp/Cntr=0.3,0.1

Type RM Length L Ch R = 1 ,36699.55,248.295300,248.295300,248.295300
XS GIS Cut Line= 6
578151.023139003736620.076310096578085.904974826736624.203053247
577986.079876891736648.065252886577756.999579482736763.889146532
577656.345584362736802.364908549577518.647832566736816.330749522
#Sta/Elev= 30
9715.914303.10649752.013299.26699782.092291.82479802.411288.96259822.729287.2422
9843.341286.55419864.223282.55499873.321281.80899895.984280.61089928.492280.6647
 9939.48 278.938 9950.61275.34129961.741270.10219972.872262.27539984.003261.0481
10006.33260.156810019.91 265.84710028.95268.165210040.37267.608710051.79272.2065
10120.33270.632410270.56275.743510280.76279.656810290.95281.832410301.15 283.057
10331.31291.191510361.34300.732810371.34302.693910381.35302.7646 10387.7301.2955
#Mann= 3 , 0 , 0
9715.914  0.0413       09715.914  0.0413       0 10387.7  0.0413       0
#XS Ineff= 2 , 0
       0                               0
Bank Sta=9715.914,10387.7
Exp/Cntr=0.3,0.1

Type RM Length L Ch R = 1 ,36451.25,248.295300,248.295300,248.295300
XS GIS Cut Line= 6
578138.564774186 736501.72184434577903.953280331736461.204773244
577829.246979126736458.745422147577782.346063105736470.599898886
577632.048422827736526.884807254577483.540618765 736550.66354893
#Sta/Elev= 30
9607.097300.51669677.748298.47799702.161 296.4329732.582291.23889763.003283.6866
9793.424279.05739844.125276.65139874.226270.96799884.256267.9348 9914.31268.1988
9944.818265.93689976.621259.48479987.599259.35859998.577256.177310009.57258.3602
10020.56264.687110027.53267.108710063.64268.497610074.98272.259410085.91 277.081
10095.12284.426710105.52295.469310115.92299.672510126.31301.281310167.24304.3879
10187.68308.5427 10207.9311.327810228.11 313.78610238.22 313.20910279.93318.8973
#Mann= 3 , 0 , 0
9607.097  0.0447       09607.097  0.0447       010279.93  0.0447       0
#XS Ineff= 2 , 0
       0                               0
Bank Sta=9607.097,10279.93
Exp/Cntr=0.3,0.1

Type RM Length L Ch R = 1 ,36202.96,248.295300,248.295300,248.295300
XS GIS Cut Line= 6
578135.651540336736474.046122777578007.299418107736436.183623628
577930.229920851736393.624509552577805.322895078736211.352200875
 577728.69542532736148.035399826577639.831415709736107.397931914
#Sta/Elev= 30
9661.204299.54419723.899299.09379767.508295.6624 9786.98292.68219797.621290.1177
9819.495  283.469841.945279.10169912.172271.20639933.767266.96199949.155267.5498
 9951.73267.10399961.049264.0707  9972.3261.17399983.552255.12879994.803252.7444
10005.96254.4258 10017.1261.613410028.24262.850910039.81263.257510063.29267.0271
10090.54274.2697 10101.4275.497310120.34279.103710134.17283.948510161.06290.3102
10232.67305.030810276.62316.6298 10287.4318.809410298.17319.720510303.63321.1718
#Mann= 3 , 0 , 0
9661.204    0.12       09661.204    0.12       010303.63    0.12       0
#XS Ineff= 2 , 0
       0                               0
Bank Sta=9661.204,10303.63
Exp/Cntr=0.3,0.1

Type RM Length L Ch R = 1 ,35954.66,248.295400,248.295400,248.295400
XS GIS Cut Line= 6
578266.384667572736232.563713336578142.226136289736178.056670014
577877.387971085736049.333027321577809.353419184736027.723504494
 577736.12663509736013.747709577577626.038432206736005.039475473
#Sta/Elev= 30
9724.686270.61619758.434270.21429791.171271.83249813.206270.13879835.241270.1734
9857.275268.51169879.646268.09779890.859265.11849902.071258.25619924.496258.6723
9955.527255.34579980.558253.58619991.771251.459310002.96251.099810014.12253.7477
10025.29258.789110047.61260.188810058.78261.891510091.99272.649610113.82277.0989
10135.65282.556910146.57 282.08210157.41284.727310168.02286.0812 10189.2286.9839
10210.01289.597710251.09292.071810291.81298.758410322.08301.428510411.33319.8179
#Mann= 3 , 0 , 0
9724.686  0.0555       09724.686  0.0555       010411.33  0.0555       0
#XS Ineff= 2 , 0
       0                               0
Bank Sta=9724.686,10411.33
Exp/Cntr=0.3,0.1

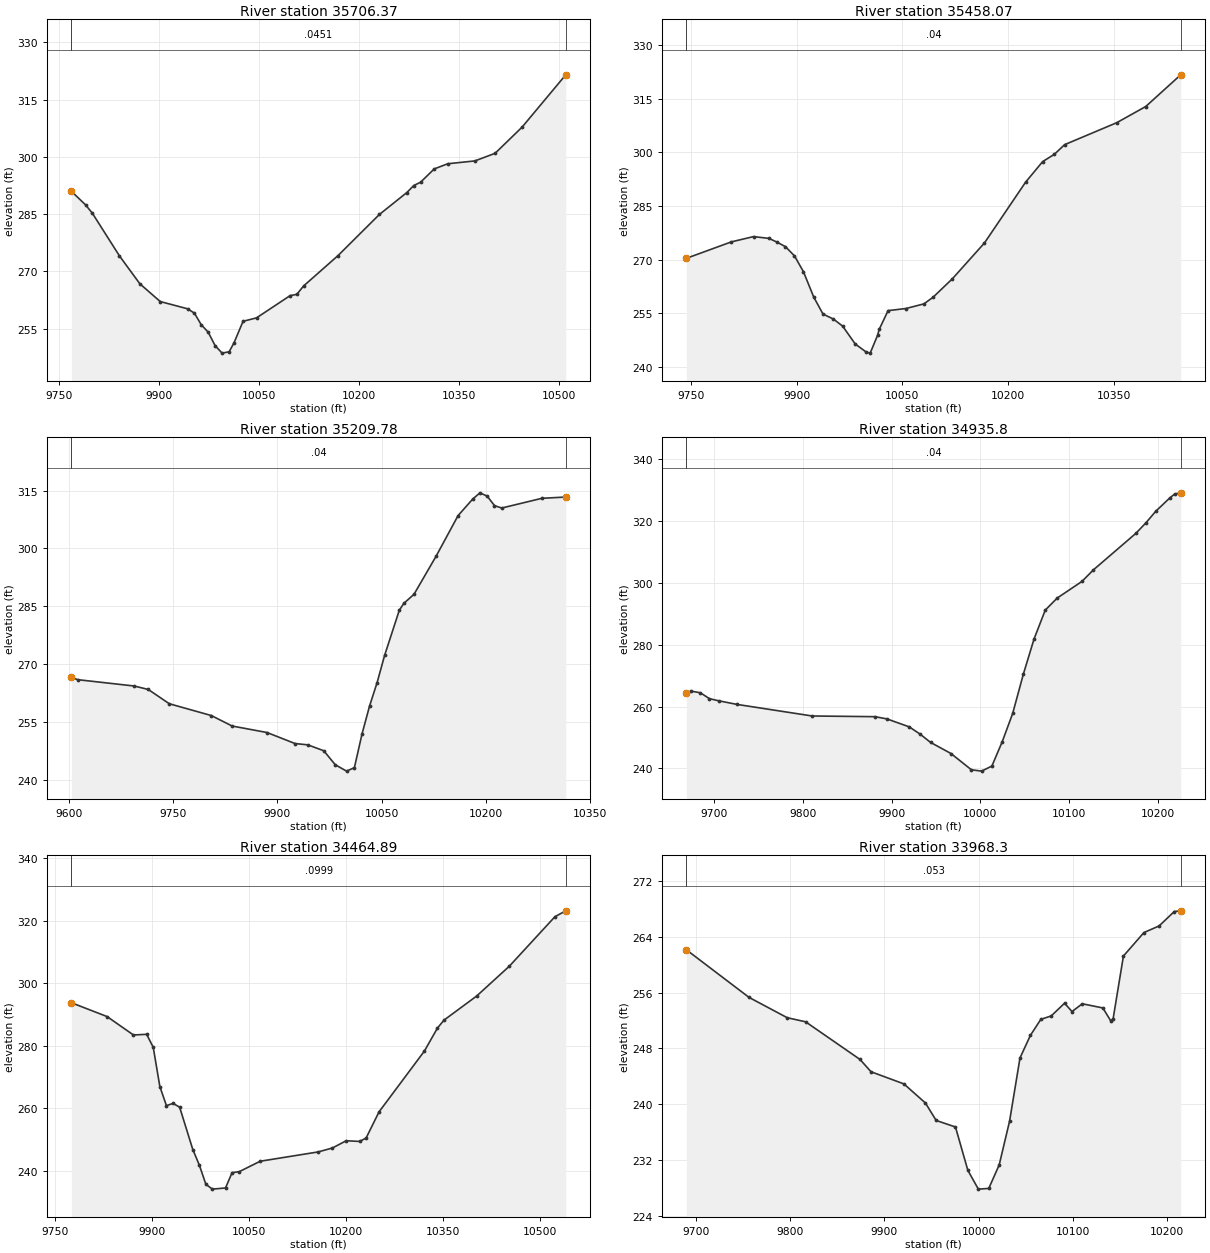
Type RM Length L Ch R = 1 ,35706.37,248.295300,248.295300,248.295300
XS GIS Cut Line= 6
578345.876949373735938.051325057578199.522679497735909.947759345
578060.567585032735876.246509475578004.787000812735882.836950715
577800.620239026735933.727545063577619.805131229735958.781820887
#Sta/Elev= 30
9767.936290.96019789.194287.41319799.377285.23139840.108 274.0339870.656266.7429
9901.204262.09399942.166260.19649952.444259.06089962.721256.03079973.114254.0773
9983.588250.53999994.063248.582710004.57248.935710011.89251.268310025.48256.9203
10045.69257.813310095.99263.634310106.14263.9794 10116.3266.170410167.95274.1262
10229.94284.887510271.26290.644710281.52 292.46810291.75293.334910312.23296.8193
10332.66298.179710373.28298.920110403.62 300.91610443.94307.743410509.57321.4656
#Mann= 3 , 0 , 0
9767.936  0.0451       09767.936  0.0451       010509.57  0.0451       0
#XS Ineff= 2 , 0
       0                               0
Bank Sta=9767.936,10509.57
Exp/Cntr=0.3,0.1

Type RM Length L Ch R = 1 ,35458.07,248.295300,248.295300,248.295300
XS GIS Cut Line= 6
578198.292457288735592.625372716578113.516578356735604.841126293
578065.673073138 735628.80459394577841.572467311 735858.07280213
577755.716005601735898.496263894577616.216300481735932.148919037
#Sta/Elev= 30
9743.712270.39059807.611274.9969 9839.04276.47249860.899275.96489872.548274.8908
9884.266273.64659896.949271.08579909.632266.68759924.288259.56389937.441254.8048
9952.165253.41149965.271251.43819983.074246.44579998.715244.170710004.31  243.88
10014.92248.915610017.01250.4887 10029.7255.7646 10055.1  256.36 10080.5257.6518
10093.59259.530910120.86264.677610166.35274.699510224.65291.697310248.77297.4363
10265.43299.495610279.94302.179810353.68308.308210394.92312.847410444.49321.7112
#Mann= 3 , 0 , 0
9743.712    0.04       09743.712    0.04       010444.49    0.04       0
#XS Ineff= 2 , 0
       0                               0
Bank Sta=9743.712,10444.49
Exp/Cntr=0.3,0.1

Type RM Length L Ch R = 1 ,35209.78,273.977900,273.977900,273.977900
XS GIS Cut Line= 6
578183.982752604735552.948464296577977.300283166735523.687907663
577863.360292798735531.132312596577829.380048909735539.231269002
577630.086902534735615.118375665577496.707413672735654.371529508
#Sta/Elev= 30
9604.002266.6161 9613.11 266.0049694.219264.36449714.497263.4716  9744.8259.7661
9805.109256.71569835.152253.99759885.225252.31639925.591249.45969943.928249.1197
9966.851247.59249983.385 243.9679999.639242.3132 10010.9243.218510021.91251.9763
10032.74259.204310043.56265.253110054.38272.3232 10075.5284.007610081.99285.7762
10096.62288.1281 10128.3297.967210159.98308.514110181.03312.800110191.47314.4072
 10201.9 313.53910212.33311.095610222.77310.467410280.48312.988210314.76313.3162
#Mann= 3 , 0 , 0
9604.002    0.04       09604.002    0.04       010314.76    0.04       0
#XS Ineff= 2 , 0
       0                               0
Bank Sta=9604.002,10314.76
Exp/Cntr=0.3,0.1

Type RM Length L Ch R = 1 , 34935.8,470.908100,470.908100,470.908100
XS GIS Cut Line= 6
578200.333395338 735526.76839668578091.995571875735497.962859229
578029.203729146735464.454224922577994.527246384735430.293087593
577876.034018823735255.196924578577778.566025517735200.747323367
#Sta/Elev= 30
9668.791264.43659674.268264.96199684.538264.44789694.807262.54149705.076261.8569
9725.615260.69289810.568256.93949881.415 256.7179894.812255.99259919.939253.4263
9932.246251.0592  9943.9248.41489966.928244.81599989.955239.558910001.47239.1248
10013.03240.770810024.62248.569810036.49257.780510048.52270.483310060.54281.8206
10073.17291.145910086.61295.037310114.56300.425410127.33304.124910175.13315.9107
10186.75319.401110197.68323.086410213.19327.313710218.93328.642510225.76329.0377
#Mann= 3 , 0 , 0
9668.791    0.04       09668.791    0.04       010225.76    0.04       0
#XS Ineff= 2 , 0
       0                               0
Bank Sta=9668.791,10225.76
Exp/Cntr=0.3,0.1

Type RM Length L Ch R = 1 ,34464.89,496.590600,496.590600,496.590600
XS GIS Cut Line= 6
578499.467535866735028.572402491578249.822885764735074.433322753
 578188.46509947735151.263534187578099.571856924735189.880916768
578034.969609893735191.214547066577788.343948264735158.627040717
#Sta/Elev= 30
9774.712293.7603 9829.96289.33649870.778 283.4439891.191283.66329901.398279.4897
9911.605266.94629921.812260.84129932.019 261.5679942.225260.35079962.614246.7977
 9972.72241.81989982.826235.68059992.933234.1393 10013.2 234.50910023.34   239.4
10034.39239.717510066.84243.058510156.59246.0404 10178.7247.302810199.95249.6132
10220.57249.396310230.69250.457510250.78258.861110320.97278.309610341.14285.6536
10351.25288.193910401.81295.904810452.36305.443910522.93321.278410539.66323.1607
#Mann= 3 , 0 , 0
9774.712  0.0999       09774.712  0.0999       010539.66  0.0999       0
#XS Ineff= 2 , 0
       0                               0
Bank Sta=9774.712,10539.66
Exp/Cntr=0.3,0.1

Type RM Length L Ch R = 1 , 33968.3,248.295300,248.295300,248.295300
XS GIS Cut Line= 6
578205.991243846734744.832859415578155.515811678734769.934644781
 577968.75305298734879.058757698 577847.57259279734937.170368969
 577780.14968726734966.995674543577738.681087231734983.471725518
#Sta/Elev= 30
9689.451262.14369756.109255.3119 9796.72252.39479816.182251.81469874.075246.4092
9885.781244.64539920.674242.90679943.565240.1694 9955.01237.66159975.513 236.725
9988.684230.50319999.842227.8128 10010.9227.912310021.97231.279410033.03237.5612
10044.09246.623610055.15249.863810066.22252.160210077.28252.654510091.48254.4789
10099.37253.279710110.31 254.39710132.18253.798310140.63251.929310143.11  252.27
10154.05261.247810175.83264.612410191.96265.561510208.11267.629610214.91267.7281
#Mann= 3 , 0 , 0
9689.451   0.053       09689.451   0.053       010214.91   0.053       0
#XS Ineff= 2 , 0
       0                               0
Bank Sta=9689.451,10214.91
Exp/Cntr=0.3,0.1

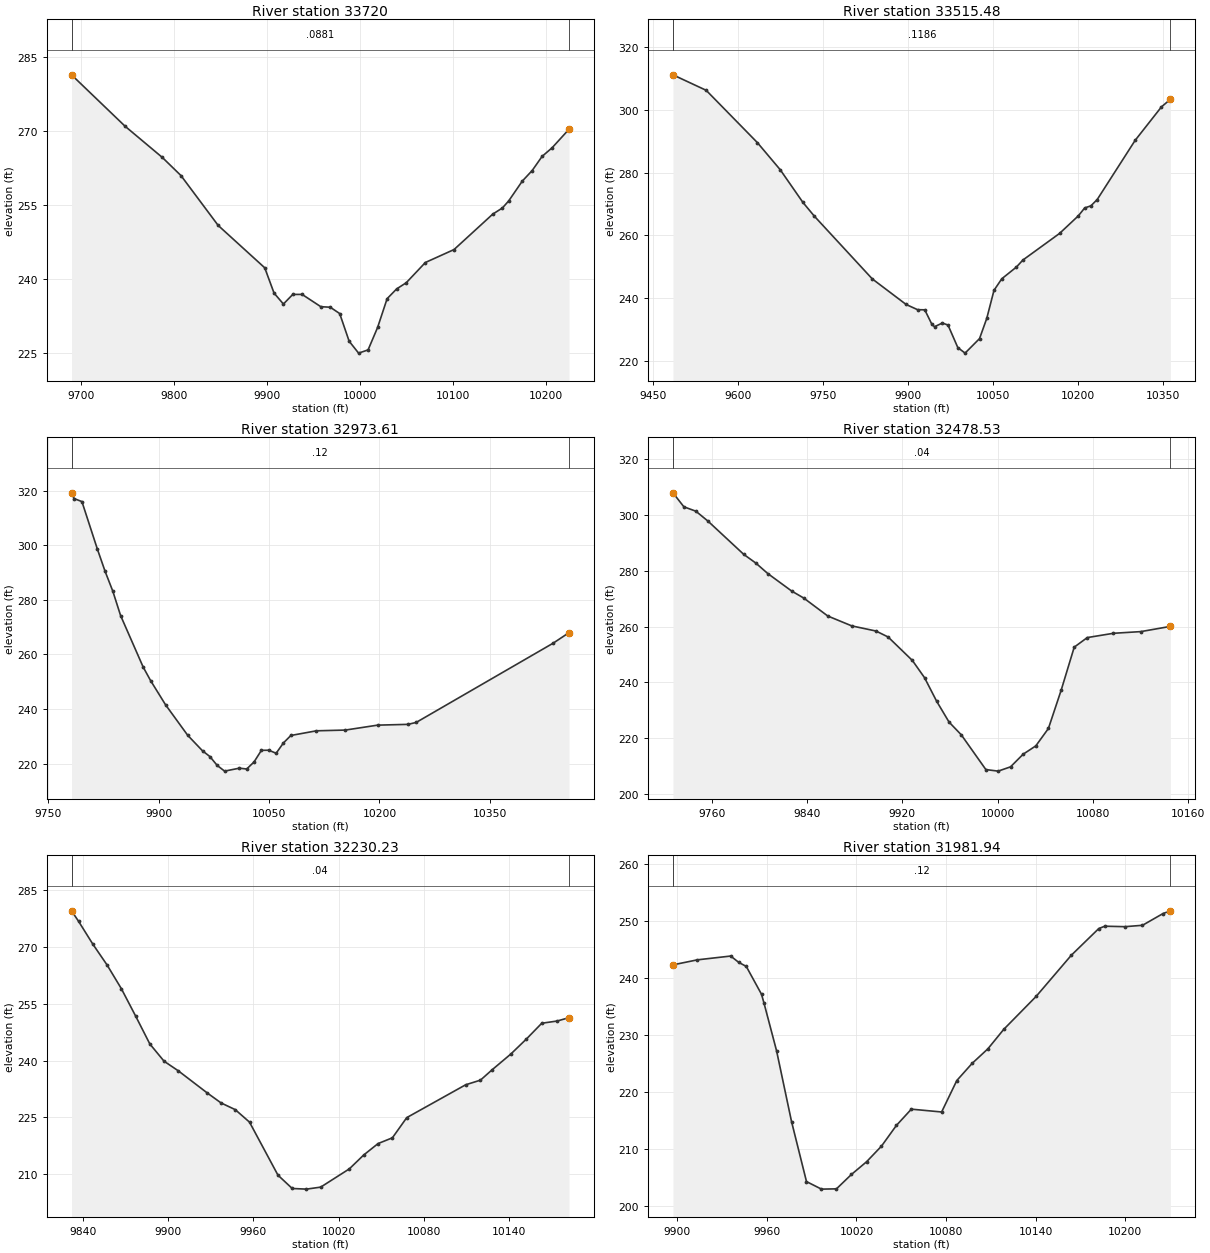
Type RM Length L Ch R = 1 ,   33720,204.528500,204.528500,204.528500
XS GIS Cut Line= 6
578152.459419225734645.003240564577939.349048788 734652.92298938
577880.965469459734658.967080372577740.594030356734689.348173738
 577693.91405329734703.032479951577628.508108789734729.008577876
#Sta/Elev= 30
9690.153 281.3699747.771270.92789787.783264.59799807.789260.9255  9847.8250.8061
9897.813242.21699907.838237.08339917.891 234.8659927.945236.81379937.998236.8183
9958.105234.32579968.222234.22039978.381232.93339988.541227.32619998.701224.9049
10008.91225.560910019.13 230.10910029.37235.954610039.64 237.93910049.92239.1844
10070.47243.291110101.29245.918610142.91253.106710153.33254.360510160.13255.8102
10174.63259.7978 10185.3261.953310195.96 264.82310206.67266.561510224.89270.3287
#Mann= 3 , 0 , 0
9690.153  0.0881       09690.153  0.0881       010224.89  0.0881       0
#XS Ineff= 2 , 0
       0                               0
Bank Sta=9690.153,10224.89
Exp/Cntr=0.3,0.1

Type RM Length L Ch R = 1 ,33515.48,541.864300,541.864300,541.864300
XS GIS Cut Line= 6
578363.390985489734555.261283576578052.803293973734583.759414732
577954.279129416734540.722536922  577829.5936023734410.691792816
577805.574246466 734401.93868573577581.587661684734514.237266317
#Sta/Elev= 30
9485.803311.20939544.439306.26889634.817289.57649674.985280.96129715.153270.5109
9735.237  266.149837.483246.12329897.288237.95539917.447236.29919930.143236.2534
9942.838231.58239947.376230.86479961.234 232.0529971.137231.39249988.475224.2073
10001.26222.442410026.77227.076610039.54233.526610052.31242.484210066.09246.1654
10091.81249.888510103.19252.121110167.99 260.623 10201.2266.244710212.27268.7443
10223.35 269.43110234.42271.435710301.39290.319910347.83300.993210363.62303.4158
#Mann= 3 , 0 , 0
9485.803  0.1186       09485.803  0.1186       010363.62  0.1186       0
#XS Ineff= 2 , 0
       0                               0
Bank Sta=9485.803,10363.62
Exp/Cntr=0.3,0.1

Type RM Length L Ch R = 1 ,32973.61,495.083800,495.083800,495.083800
XS GIS Cut Line= 6
578014.961792928733881.752358906577982.060266488734007.136605441
577977.437163979734203.797764942 577931.76600641734305.484596208
577788.437099934734377.677823827577714.349074841734398.845831007
#Sta/Elev= 30
9781.827319.21189785.311317.10949795.933315.99399816.933298.57689827.433290.4201
9837.871283.17879848.491274.21459879.081255.38599889.231250.3896 9909.53241.5383
9939.655230.34619959.721 224.6789969.722 222.5759979.723219.30699989.723217.2317
10009.72218.313210019.72218.009310029.72 220.59710039.72224.853710049.72224.8952
10059.72223.777510069.72227.595810079.72 230.29510114.47232.005610153.69232.2765
10197.54234.084410238.77234.366710249.96235.078610436.05264.127810457.53 267.979
#Mann= 3 , 0 , 0
9781.827    0.12       09781.827    0.12       010457.53    0.12       0
#XS Ineff= 2 , 0
       0                               0
Bank Sta=9781.827,10457.53
Exp/Cntr=0.3,0.1

Type RM Length L Ch R = 1 ,32478.53,248.295400,248.295400,248.295400
XS GIS Cut Line= 6
577662.944298716733905.874360988577644.033993006734065.735074628
577633.546285477734119.308830761577617.067387789734184.042855099
577603.703096374734221.953966677 577564.84291654734308.695489956
#Sta/Elev= 30
9727.442307.83319736.623302.82699746.683301.26129756.743297.74839786.923285.7958
9796.983 282.7179807.044278.95889827.164  272.689837.232270.19439857.414263.7663
9877.596260.22759897.869258.39579908.059256.26339928.439247.86299938.629241.7127
9948.888233.21589959.199225.8379 9969.51221.25349990.133 208.82810000.45208.2758
10010.83209.808210021.44214.333110032.04217.299910042.64223.537110053.35237.2332
10064.31252.628810075.27256.049110097.19257.583410120.22258.188210145.07260.0543
#Mann= 3 , 0 , 0
9727.442    0.04       09727.442    0.04       010145.07    0.04       0
#XS Ineff= 2 , 0
       0                               0
Bank Sta=9727.442,10145.07
Exp/Cntr=0.3,0.1

Type RM Length L Ch R = 1 ,32230.23,248.295300,248.295300,248.295300
XS GIS Cut Line= 6
577359.101774557733980.015502126577373.438483379734146.613265985
577374.469093429734159.241666683577383.712346317734219.632377317
577399.248826323734272.753441154577420.834928342734322.629764109
#Sta/Elev= 30
9831.786279.62169836.789276.82329846.826270.79699856.863265.2921  9866.9259.0448
9876.937251.82939886.974244.43489897.011239.87319907.048237.33169927.122231.5754
9937.159228.84999947.196227.06839957.233223.77439977.307209.74639987.344206.2322
9997.381206.062410007.41206.590710027.61211.417910037.73215.083110047.85218.1028
10057.96219.627610068.08224.962910109.61233.644910120.03234.868810128.11237.5617
10141.46241.776810152.35245.713510163.25249.909210174.14250.496710182.46251.3866
#Mann= 3 , 0 , 0
9831.786    0.04       09831.786    0.04       010182.46    0.04       0
#XS Ineff= 2 , 0
       0                               0
Bank Sta=9831.786,10182.46
Exp/Cntr=0.3,0.1

Type RM Length L Ch R = 1 ,31981.94,248.295300,248.295300,248.295300
XS GIS Cut Line= 6
577081.407442861734251.057186741577137.934722703734275.249752513
577206.880704181734271.640273901577274.088695515734279.339431745
577340.924474316734307.469846008577388.596803773734345.465102336
#Sta/Elev= 30
9897.151242.33829913.488243.21929935.816243.8862 9941.11242.79459946.263242.0594
9956.464237.17349958.193235.55949966.537227.25749976.558214.83719986.581204.2964
9996.604202.972310006.65203.020910016.71205.555810026.77207.766310036.79210.5169
10046.79214.1554 10056.8217.010110077.08216.513510087.24222.033510097.45 225.031
10108.06227.603310118.67231.014910140.36 236.80110163.89244.018210182.32248.7136
10186.35249.124410199.78249.041410211.58 249.28210225.35251.3472 10230.3251.8232
#Mann= 3 , 0 , 0
9897.151    0.12       09897.151    0.12       0 10230.3    0.12       0
#XS Ineff= 2 , 0
       0                               0
Bank Sta=9897.151,10230.3
Exp/Cntr=0.3,0.1

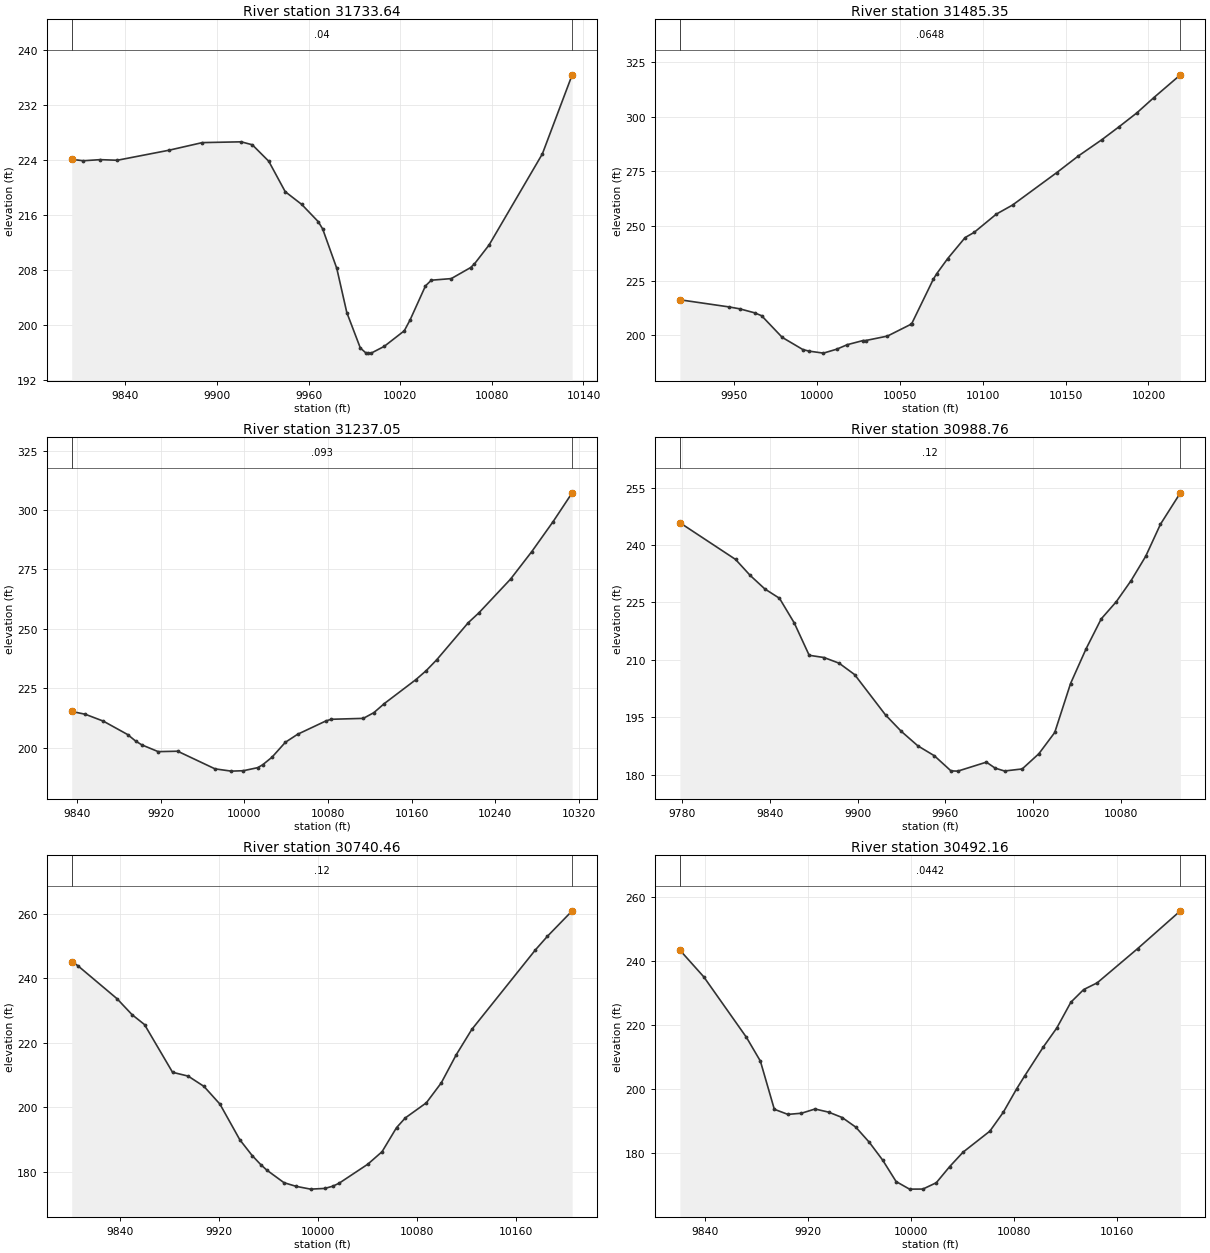
Type RM Length L Ch R = 1 ,31733.64,248.295300,248.295300,248.295300
XS GIS Cut Line= 6
577066.987801458734328.212807063577110.416088334734416.827831248
577134.647744313734477.228335385577183.306214657734520.067927261
577200.333898023734540.315843106577236.433772895734602.695533607
#Sta/Elev= 30
9804.882 224.036 9812.44223.83239823.576223.99079834.713223.90199868.535225.3584
9890.394226.46869915.877226.58319923.146226.15299933.921223.75979944.696219.3363
 9955.47217.49029966.245 214.9969969.222213.9209 9978.47208.1824 9985.03201.7643
9993.882196.61349997.328195.9294    9999 195.864   10001195.865910009.54 196.846
10022.66199.110510026.41200.666910036.55205.640210040.36206.464110053.43 206.699
10066.05208.295510068.62208.841410078.18211.582910113.07224.8232 10132.6 236.322
#Mann= 3 , 0 , 0
9804.882    0.04       09804.882    0.04       0 10132.6    0.04       0
#XS Ineff= 2 , 0
       0                               0
Bank Sta=9804.882,10132.6
Exp/Cntr=0.3,0.1

Type RM Length L Ch R = 1 ,31485.35,248.295400,248.295400,248.295400
XS GIS Cut Line= 6
577019.275043165734352.843794635576988.422648994734385.458906549
576922.717341455734436.506978087576900.570841022734461.520144776
576869.427020694734519.192578376576846.642047971734590.394117476
#Sta/Elev= 30
9917.098216.22059946.758212.95349953.209212.08259962.166210.25469966.428208.9266
9978.881 199.0049991.334193.43529994.956192.724910003.75 191.79310011.84193.6091
10018.19195.669410027.76197.568210029.23197.557210042.41199.596410056.76205.0623
10057.06205.267810070.12225.631110072.15228.142110078.83 235.12310089.33244.7131
10094.73247.067410108.17255.453810117.93259.591510144.52274.385810157.75282.1083
 10171.9289.534510182.32295.484410192.91301.738910203.31308.826110219.31 319.236
#Mann= 3 , 0 , 0
9917.098  0.0648       09917.098  0.0648       010219.31  0.0648       0
#XS Ineff= 2 , 0
       0                               0
Bank Sta=9917.098,10219.31
Exp/Cntr=0.3,0.1

Type RM Length L Ch R = 1 ,31237.05,248.295300,248.295300,248.295300
XS GIS Cut Line= 6
576704.216731861734132.448163175576740.887359978734220.162904917
576806.426050415734300.974981554   576825.678659734341.872783439
 576835.07224644734417.635203969576812.629550562734572.801446403
#Sta/Elev= 30
9834.857 215.2129847.926 214.011  9865.1211.13199888.347205.47879896.008202.7376
9901.869201.14179917.573198.2841  9936.2  198.469971.947191.02659987.458190.0767
    9999 190.24810012.81191.544210017.57192.780110026.37195.919410039.19202.2222
10050.95 205.60310077.93211.2002 10083.1211.909710113.75212.289510123.83214.7042
10133.86218.531710163.89228.559410173.92232.399110183.96236.9754 10214.1252.5822
10224.22256.6981 10254.6270.957710274.89282.5434 10295.3295.176710313.47307.2569
#Mann= 3 , 0 , 0
9834.857   0.093       09834.857   0.093       010313.47   0.093       0
#XS Ineff= 2 , 0
       0                               0
Bank Sta=9834.857,10313.47
Exp/Cntr=0.3,0.1

Type RM Length L Ch R = 1 ,30988.76,248.295300,248.295300,248.295300
XS GIS Cut Line= 6
576569.542651881734216.996445159576569.589000901 734283.63561592
576576.298201267734321.285442455576590.682995098734362.638174021
576651.877180391 734471.10805951 576662.51924765734538.601924744
#Sta/Elev= 30
9778.513245.84019816.587236.24329826.591232.06529836.595228.5343 9846.62226.0899
9856.778219.60959866.935211.18979877.093210.6027 9887.41 209.1239897.998206.1489
9919.174195.58069929.935 191.3079941.258187.5182 9952.58184.91719963.903180.9748
9968.572180.90779988.142183.25559994.126181.692110000.53180.941310012.64181.4782
10024.04 185.46210034.88191.006710045.71203.809410056.34212.899110066.66220.6977
 10076.9 225.15610087.02230.661410097.14237.096310107.19245.445710120.83253.6576
#Mann= 3 , 0 , 0
9778.513    0.12       09778.513    0.12       010120.83    0.12       0
#XS Ineff= 2 , 0
       0                               0
Bank Sta=9778.513,10120.83
Exp/Cntr=0.3,0.1

Type RM Length L Ch R = 1 ,30740.46,248.295300,248.295300,248.295300
XS GIS Cut Line= 6
576552.073249183734210.445419143576537.029924196 734252.31004687
576519.016152377734286.027522657576485.389307785734323.271758299
 576377.80305484734389.156058533576258.904561584734472.793570025
#Sta/Elev= 30
9800.706245.1801 9805.47243.93969837.391233.64879849.519228.71519859.598225.6445
9882.274210.86039894.891209.67789907.654 206.4989920.602200.99489936.672189.9563
9946.647185.07299953.558182.27729958.484180.55819972.433176.65299982.236175.5291
9993.844174.667310005.41174.883810012.01175.596910016.98 176.50310040.12182.3786
10051.69186.2616 10063.4193.720310070.49196.7291 10087.5201.406310099.56 207.575
10111.61216.248810124.23 224.12310175.71248.783810185.34252.962610205.43260.8779
#Mann= 3 , 0 , 0
9800.706    0.12       09800.706    0.12       010205.43    0.12       0
#XS Ineff= 2 , 0
       0                               0
Bank Sta=9800.706,10205.43
Exp/Cntr=0.3,0.1

Type RM Length L Ch R = 1 ,30492.16,248.295300,248.295300,248.295300
XS GIS Cut Line= 6
576501.139813958734066.357539775576466.992592496734084.586925017
576434.877752053734097.958137382576366.977943725734120.709374245
576213.354295695734165.330268904576133.391960328734190.870712609
#Sta/Elev= 30
9820.371243.39239838.934235.04929872.101216.14199882.933208.71649893.765193.6672
9904.315192.07169914.861192.43279925.408193.75559935.954  192.789946.501191.0959
9957.047188.10249967.571183.36899978.002177.77959988.433171.08499998.864168.7169
10009.27168.738910019.68170.715410030.09175.7623 10040.5180.273910061.32186.8347
10071.72192.711210082.13200.049310088.25204.007710102.95213.184610113.36219.0769
10124.29227.123610134.25231.081310144.74233.173710176.21243.880610209.43255.6817
#Mann= 3 , 0 , 0
9820.371  0.0442       09820.371  0.0442       010209.43  0.0442       0
#XS Ineff= 2 , 0
       0                               0
Bank Sta=9820.371,10209.43
Exp/Cntr=0.3,0.1

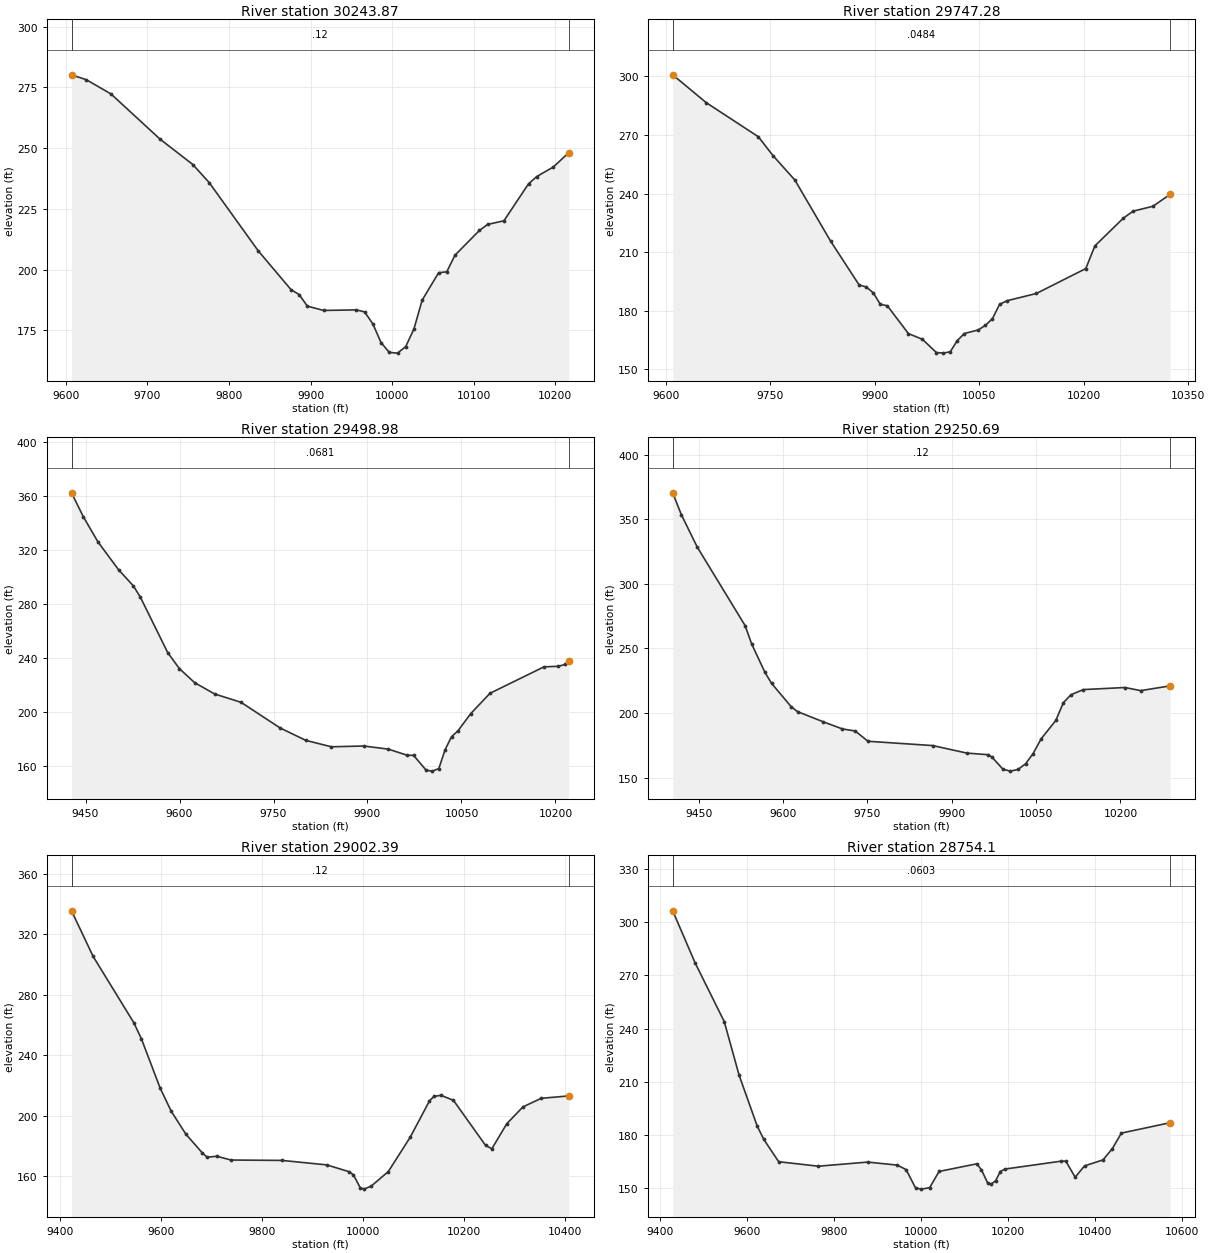
Type RM Length L Ch R = 1 ,30243.87,496.590700,496.590700,496.590700
XS GIS Cut Line= 6
576703.221348435 733873.24393484576427.720534325733893.260516047
576345.729320675733889.869027942576251.623383552733878.346923336
576183.825377375733876.687597588576096.385821819733888.085647956
#Sta/Elev= 30
9607.166280.17049625.433278.13519655.509272.2976 9715.66253.68359755.761243.2563
9775.812 235.8269835.963207.70229876.091191.75429886.115189.68859896.115184.9544
9916.116183.18179956.209183.40559966.245182.59079976.331177.65389986.417169.9521
9996.503165.911310006.58 165.61110016.65168.315410026.72175.559610036.79187.4287
10056.92198.704210066.95199.093310076.95205.910210106.96216.124510116.96218.5841
10136.99220.094410167.08235.309710177.18238.313110197.43242.206710216.45248.1441
#Mann= 3 , 0 , 0
9607.166    0.12       09607.166    0.12       010216.45    0.12       0
#XS Ineff= 2 , 0
       0                               0
Bank Sta=9607.166,10216.45
Exp/Cntr=0.3,0.1

Type RM Length L Ch R = 1 ,29747.28,248.295300,248.295300,248.295300
XS GIS Cut Line= 6
576247.815324264733120.442820426576213.816592534 733203.80006151
576170.652154375733355.501938443576143.181114416733591.932838572
576091.126198049733687.218136898576008.234388888733771.163129263
#Sta/Elev= 30
9610.217300.80339658.337286.55569733.069269.11459754.113259.47239785.446246.9862
9836.952215.60269877.795193.22689887.911192.24599898.027 189.2229908.142183.3648
9918.258182.59189948.488 168.3549968.523165.45779988.558158.68379998.575158.3656
10008.58 159.09210018.59164.7787 10028.6168.374610048.69170.233910058.75172.5418
10068.95175.943910079.19183.269610089.42185.142510132.02188.885710202.99201.6389
10216.09213.253610256.57227.348610270.84 231.01810299.44 233.53910323.84239.5798
#Mann= 3 , 0 , 0
9610.217  0.0484       09610.217  0.0484       010323.84  0.0484       0
#XS Ineff= 2 , 0
       0                               0
Bank Sta=9610.217,10323.84
Exp/Cntr=0.3,0.1

Type RM Length L Ch R = 1 ,29498.98,248.295300,248.295300,248.295300
XS GIS Cut Line= 6
576072.044873414732958.751476481575970.201031045733177.176937885
 575930.16405172733332.577357696575897.300098412733560.750545361
575869.332778582733650.889556671575838.428972223733709.710372781
#Sta/Elev= 30
9427.616362.56299446.536 344.7469469.767 326.1439502.893305.36979526.155 293.577
9537.228285.37189581.142243.97619599.872232.03529624.166221.64929656.157213.2597
9698.152207.08869760.537188.05639801.487178.85439842.294174.07799893.887174.6604
9933.207172.35079963.427 167.788  9973.5167.74389993.647156.686410003.73156.0166
10013.87157.959910024.01172.063710034.16 181.60610044.31185.860610064.69198.6524
10095.65213.8186 10181.7233.420110204.02233.805210215.73235.1874 10221.3237.7503
#Mann= 3 , 0 , 0
9427.616  0.0681       09427.616  0.0681       0 10221.3  0.0681       0
#XS Ineff= 2 , 0
       0                               0
Bank Sta=9427.616,10221.3
Exp/Cntr=0.3,0.1

Type RM Length L Ch R = 1 ,29250.69,248.295400,248.295400,248.295400
XS GIS Cut Line= 6
576004.630280002732900.571758891575894.288570742733062.191122537
575801.146003188733232.740373123575734.709832037733339.552352571
575578.890524373733519.273337788575487.092578653733611.420919467
#Sta/Elev= 30
9403.976370.39149419.281353.50989447.519328.44849532.612267.65719544.371 253.364
 9567.89231.44129579.649 222.9389614.459204.88119625.854200.9948 9671.43193.1617
9705.612187.61779728.401186.00619751.189178.05469866.495174.71459926.942168.8992
 9964.97167.64769971.321165.92719991.138156.385510004.44154.940410017.88 156.243
10031.32160.631210044.76 168.51910059.02179.970410085.07194.1625 10098.5207.9021
10111.94214.047710133.88218.068410207.99219.669810235.98217.264110288.09220.9357
#Mann= 3 , 0 , 0
9403.976    0.12       09403.976    0.12       010288.09    0.12       0
#XS Ineff= 2 , 0
       0                               0
Bank Sta=9403.976,10288.09
Exp/Cntr=0.3,0.1

Type RM Length L Ch R = 1 ,29002.39,248.295300,248.295300,248.295300
XS GIS Cut Line= 6
575918.238984053732826.014887059575757.470094511732965.303044485
575482.712153247733253.684889067575411.693089384733320.677910316
575273.598392009733427.933862409575189.155472441733483.351263502
#Sta/Elev= 30
9423.322335.66219466.089305.49949546.667261.64589561.503251.1463 9598.86 218.359
9620.844203.00789649.764187.89839682.316175.50579691.948172.63369710.765173.2788
9739.214170.78069840.311170.51979928.577167.5725 9972.71163.08319981.376161.0781
 9995.01152.467110002.12151.526110016.64153.464810050.65163.146910093.85185.7788
10132.14209.8819 10140.8212.832210154.73213.610710179.59210.311210243.27180.4401
10255.68178.239310285.22194.776210317.39205.969910353.44211.614110408.08213.2021
#Mann= 3 , 0 , 0
9423.322    0.12       09423.322    0.12       010408.08    0.12       0
#XS Ineff= 2 , 0
       09891.008                       0
Bank Sta=9423.322,10408.08
Exp/Cntr=0.3,0.1

Type RM Length L Ch R = 1 , 28754.1,248.295300,248.295300,248.295300
XS GIS Cut Line= 6
575860.916595691732775.892547777 575744.31223053732834.330621987
575507.649891926732963.864898546575385.482542342733023.035499684
574997.753501372733180.068548837574818.944893484733240.409485352
#Sta/Elev= 30
9429.503306.48169480.863277.18599547.976  243.979582.153 213.6889623.809184.9786
9638.946177.47529673.146164.91099764.345162.3773 9877.58164.70359945.826162.9994
9966.029160.45899987.654150.1502   10001149.446710020.12150.258110041.78159.4233
10128.41163.727210139.24160.302610153.34152.9844 10160.9152.121410171.73154.1392
10182.56 159.38510193.39160.773210322.46 165.23110333.19165.203610354.64156.1748
10376.08162.528310418.55165.939610439.74172.185910460.93181.061410572.59186.9105
#Mann= 3 , 0 , 0
9429.503  0.0603       09429.503  0.0603       010572.59  0.0603       0
#XS Ineff= 2 , 0
       09773.872        10067.23       0
Bank Sta=9429.503,10572.59
Exp/Cntr=0.3,0.1