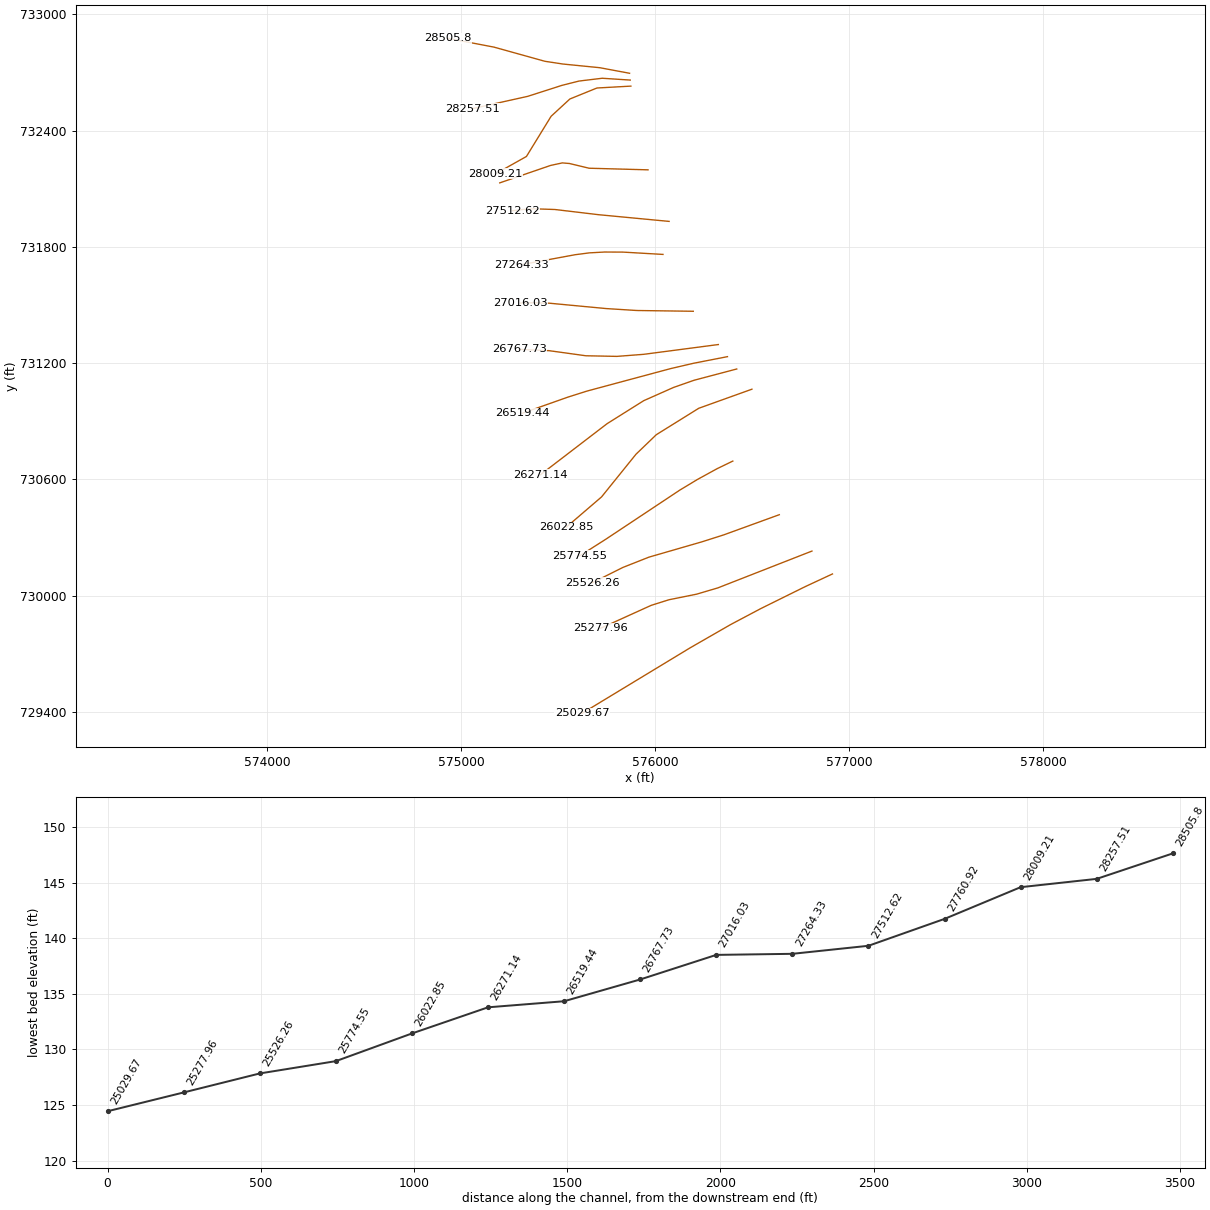
HEC-RAS study 2300_ras.prj: 2300

--- 2300_ras.g01 (geometry) --- (continued)

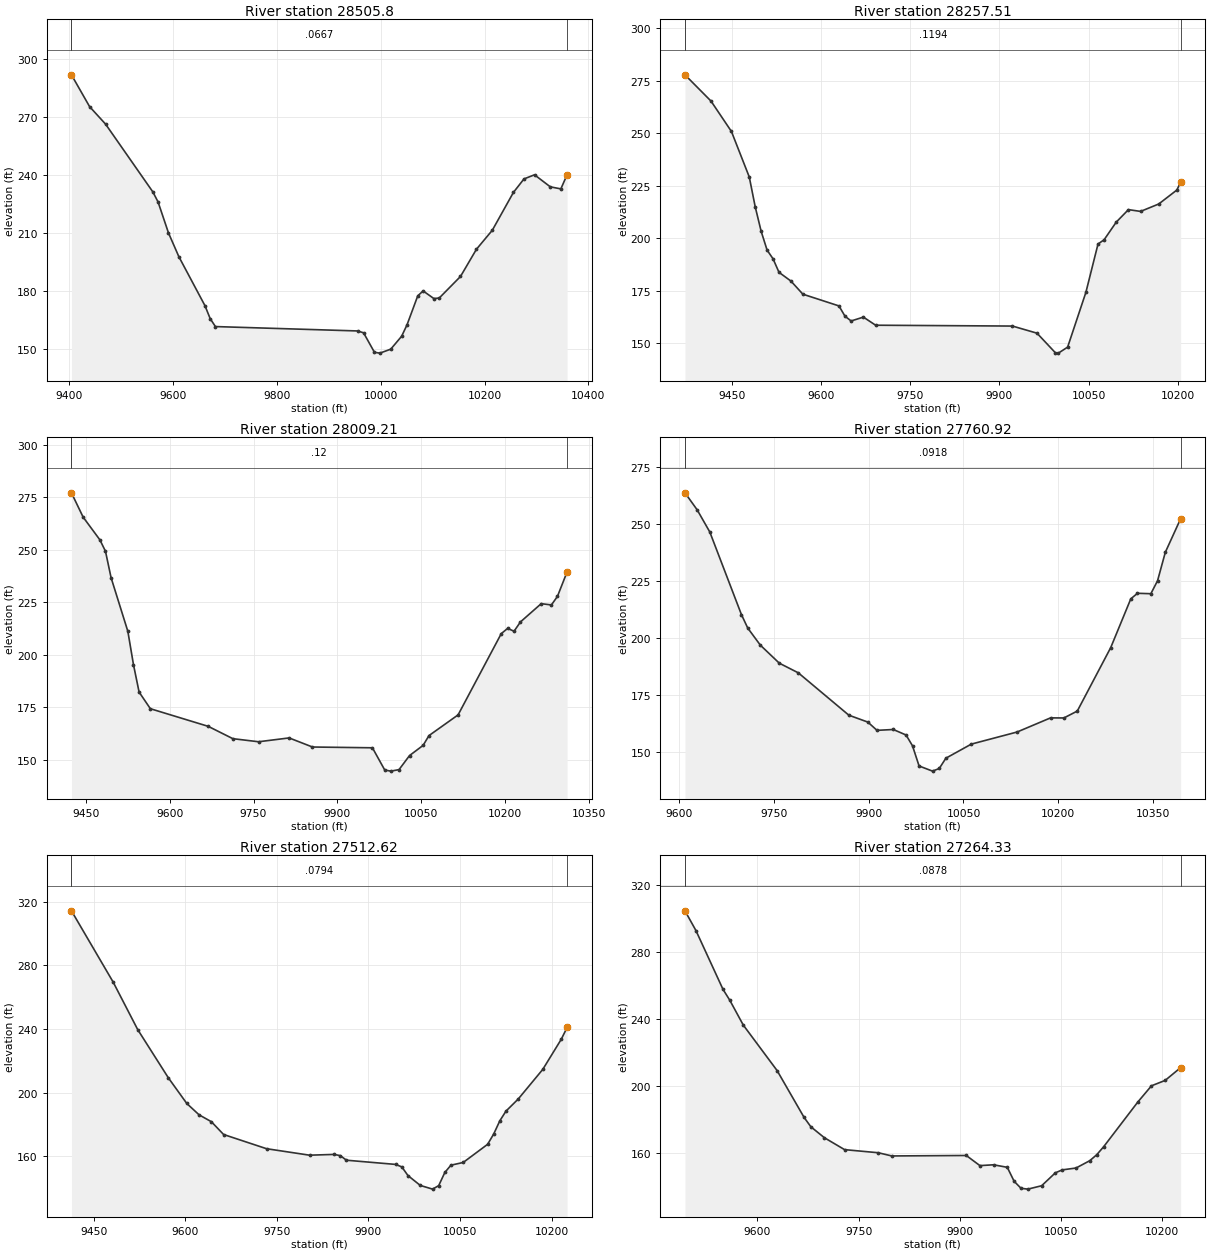
Type RM Length L Ch R = 1 , 28505.8,248.295300,248.295300,248.295300
XS GIS Cut Line= 6
575869.086497287732695.360660623 575715.72210841732724.049305692
575525.438991559732743.035611254575432.583788761732757.216975679
575170.255305372732830.277603348574933.067494077732875.558390465
#Sta/Elev= 30
 9403.85291.59419438.869275.12219469.563266.10919560.692231.04199570.741225.8493
9590.841209.8133 9610.94197.46099661.188172.14889671.238165.45329681.288161.3629
9955.381 159.0939966.835158.13239987.772148.0486 9998.24147.6238 10019.2149.6754
10040.16156.347510050.56162.258510071.26177.2681 10081.6179.7923 10102.3175.8481
10112.64176.1344 10153.6187.278310184.27201.332910214.94 211.20210255.64230.7827
10275.95237.738410296.26239.879910326.72233.6416   10347232.592110359.07239.9206
#Mann= 3 , 0 , 0
 9403.85  0.0667       0 9403.85  0.0667       010359.07  0.0667       0
#XS Ineff= 2 , 0
       0                 10091.1       0
Bank Sta=9403.85,10359.07
Exp/Cntr=0.3,0.1

Type RM Length L Ch R = 1 ,28257.51,248.295300,248.295300,248.295300
XS GIS Cut Line= 6
 575872.64872633732660.247260071575727.958589367732669.624772414
 575608.82674622732655.207070418575521.338122264732633.186975777
575344.477783382732576.393220752575058.816179035732512.831471711
#Sta/Elev= 30
9370.841277.87649414.643265.37269448.991250.91579479.032229.23399489.032215.0238
9499.032203.35179509.032194.38719519.039190.25619529.063183.81139549.111179.6593
9569.241173.40129629.922167.81969640.112162.91589650.424160.64969671.047162.4896
9691.671158.62669921.916158.22429963.183154.83279994.133 145.4989999.141145.3348
 10014.7148.1908 10045.4174.235810065.86197.3044 10076.1199.328310096.56207.7422
10117.03213.678210137.43212.828410167.99216.353510198.56223.019410204.86 226.783
#Mann= 3 , 0 , 0
9370.841  0.1194       09370.841  0.1194       010204.86  0.1194       0
#XS Ineff= 2 , 0
       0                               0
Bank Sta=9370.841,10204.86
Exp/Cntr=0.3,0.1

Type RM Length L Ch R = 1 ,28009.21,248.295400,248.295400,248.295400
XS GIS Cut Line= 6
575875.810677395732629.079456718575700.990161617732619.368756454
575561.464860764732562.659830379575464.813382999 732473.50736419
575337.676716406732266.214467957575178.953870163732176.976178814
#Sta/Elev= 30
9424.116277.01459444.971265.47189475.021254.63459485.022249.20139495.024236.6482
9525.074211.08229535.125 195.2479545.177182.21079565.341174.28779668.901165.8969
9713.002160.02939759.012158.56429813.654160.38679855.459156.0616 9962.76155.6933
9984.851  145.099995.896144.587510010.35145.304410029.17151.993310053.45156.8454
10063.99161.504610116.04171.344510193.35210.022410204.78212.510110216.21 211.149
10227.64 215.57810264.79224.267210283.11223.675410293.88227.745810311.16239.4262
#Mann= 3 , 0 , 0
9424.116    0.12       09424.116    0.12       010311.16    0.12       0
#XS Ineff= 2 , 0
       0                               0
Bank Sta=9424.116,10311.16
Exp/Cntr=0.3,0.1

Type RM Length L Ch R = 1 ,27760.92,248.295300,248.295300,248.295300
XS GIS Cut Line= 6
575964.258337572732197.268502172575660.508590097732205.532955395
575558.921386602732229.980840255575522.489831974732232.952206716
575462.296185555732219.999080176575200.225832253732129.979983507
#Sta/Elev= 30
9609.277 263.5199628.549256.08919648.564246.39239698.586  210.279708.587 204.356
9728.589 196.8539758.592188.96739788.594184.75829868.628 166.2129898.669163.1933
 9913.18159.58019938.957159.95479959.168157.53879969.344152.81259979.742 143.994
10001.02141.737310011.69142.891510022.15147.394610062.43153.561110134.84158.8518
10187.77165.036210208.94165.007210230.11168.017810283.04195.801910314.79217.1337
10325.38219.554910346.55219.377410357.13225.0486 10369.4237.485910393.65252.1828
#Mann= 3 , 0 , 0
9609.277  0.0918       09609.277  0.0918       010393.65  0.0918       0
#XS Ineff= 2 , 0
       0                               0
Bank Sta=9609.277,10393.65
Exp/Cntr=0.3,0.1

Type RM Length L Ch R = 1 ,27512.62,248.295300,248.295300,248.295300
XS GIS Cut Line= 6
576072.877796036731931.250230512575709.708145612731965.787794107
575484.390098156731992.632345635575373.989128699731996.262530582
575320.715223695731992.801541534575265.463200624731985.850913877
#Sta/Elev= 30
9413.794314.2987 9482.08269.48029522.278239.60889572.482209.25719602.605193.1702
9622.687186.03829642.769181.7254 9662.85173.66659733.137 164.7339803.498160.6597
9843.781161.14519853.852160.37579863.923157.49799944.491154.85699954.562  153.29
9964.633 147.8389984.774141.646910004.91139.320310014.93141.524610024.95149.7909
10034.96 154.376   10055 156.07810095.02167.509110105.02174.032510115.02182.3063
10125.04188.367610145.08195.967810185.26214.598610215.49233.519910225.11 240.956
#Mann= 3 , 0 , 0
9413.794  0.0794       09413.794  0.0794       010225.11  0.0794       0
#XS Ineff= 2 , 0
       0                               0
Bank Sta=9413.794,10225.11
Exp/Cntr=0.3,0.1

Type RM Length L Ch R = 1 ,27264.33,248.295300,248.295300,248.295300
XS GIS Cut Line= 6
576041.248255469731760.937319747575835.085204285731772.832708422
575740.029569971731773.227132155575662.511228751731768.940198355
 575589.88381846 731759.56015783575312.308590218731708.259540308
#Sta/Elev= 30
9492.615 304.7779508.904292.97229549.003257.87459559.028251.40989579.077236.5405
9629.157209.41479669.195181.42129679.205175.84129699.224169.30539729.225162.1797
9779.225160.31949799.233158.40859909.655158.68449929.821152.64039950.037153.1242
9970.408151.62829980.593 143.2679990.779139.094910000.97138.598310021.36140.6257
10041.76 148.36110051.95150.088710072.35151.207810092.74155.589710102.93 159.103
10113.13163.835710163.93190.618810184.18200.296710204.42203.507610227.39211.1548
#Mann= 3 , 0 , 0
9492.615  0.0878       09492.615  0.0878       010227.39  0.0878       0
#XS Ineff= 2 , 0
       0                               0
Bank Sta=9492.615,10227.39
Exp/Cntr=0.3,0.1

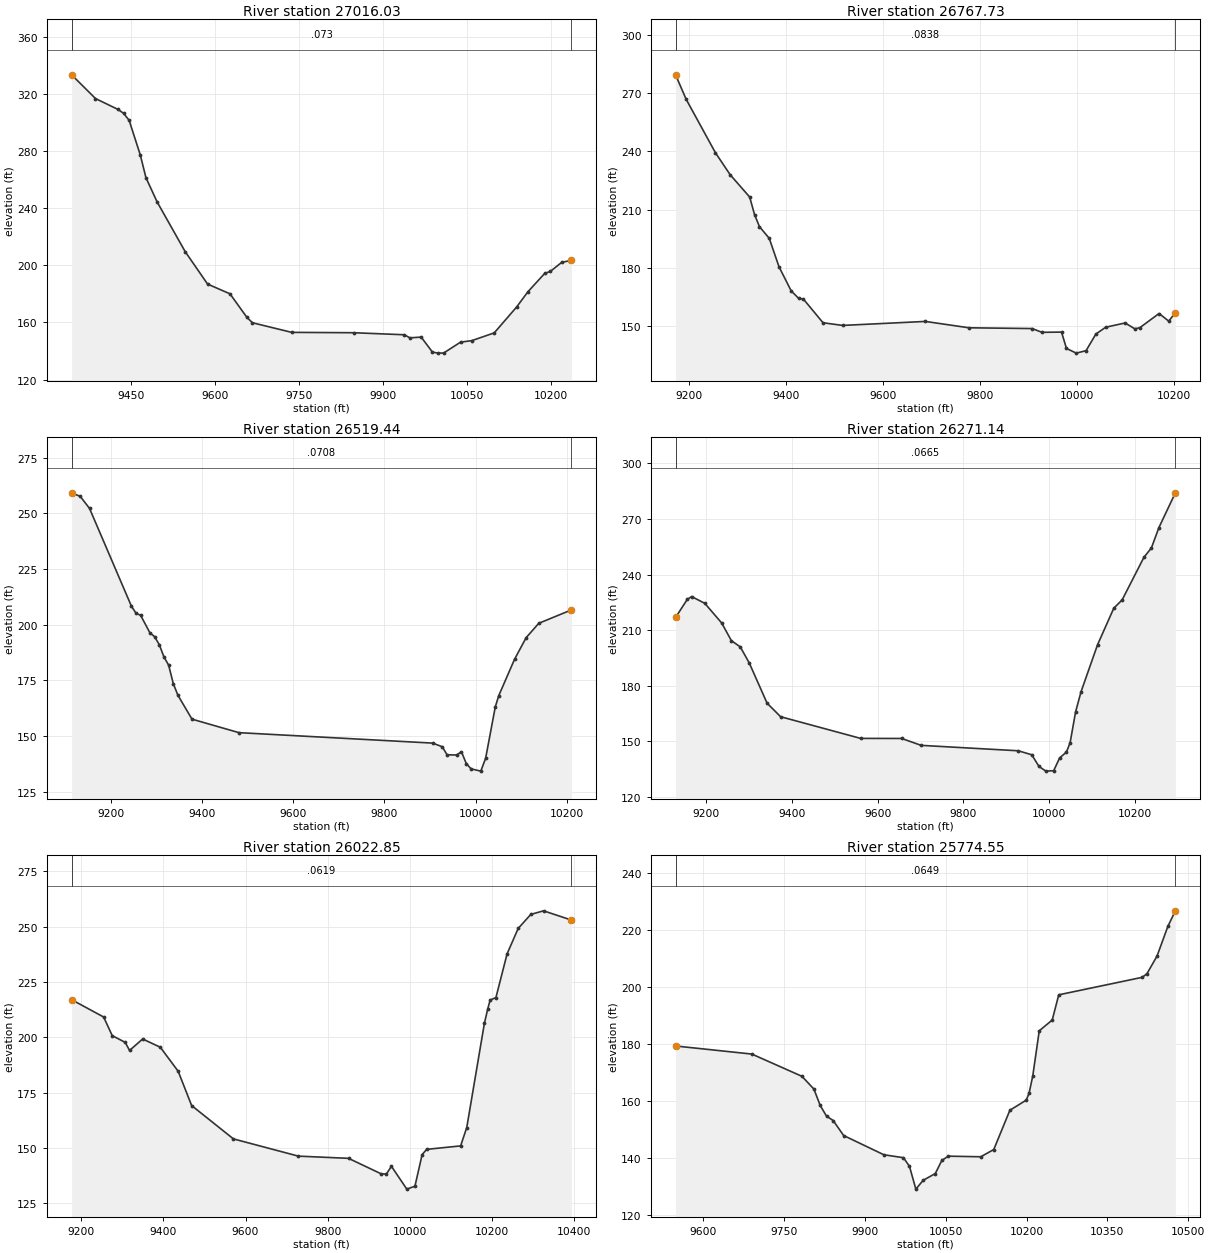
Type RM Length L Ch R = 1 ,27016.03,248.295400,248.295400,248.295400
XS GIS Cut Line= 6
576197.544397731731467.635008476575906.225767895731471.626602324
575748.503989649731481.587624242575456.120490796731509.262407576
575375.378711075731511.739377435575307.353833158731510.069257916
#Sta/Elev= 30
9344.761333.70679387.306317.08139427.306309.46439437.306306.76669447.306301.8262
9467.306277.45199477.309261.59859497.315244.53899547.329209.72059587.341186.9372
9627.353180.10579657.398163.64339667.418159.79789737.557153.0612 9847.94152.8133
9938.393151.38399948.444149.21989968.545149.74969988.645 139.2369998.692138.5023
10008.73138.582310038.83146.214510058.89147.258810098.99152.708810139.01 170.916
10159.02181.533410189.03194.431810199.03 195.81210219.04202.078410236.69203.6403
#Mann= 3 , 0 , 0
9344.761   0.073       09344.761   0.073       010236.69   0.073       0
#XS Ineff= 2 , 0
       0                               0
Bank Sta=9344.761,10236.69
Exp/Cntr=0.3,0.1

Type RM Length L Ch R = 1 ,26767.73,248.295300,248.295300,248.295300
XS GIS Cut Line= 6
 576326.61563268731296.028934749575942.317410916731245.597698557
 575803.56658868 731234.92009715575643.703727822 731238.13106328
575454.722837606731264.354013517575301.379178664731271.083078122
#Sta/Elev= 30
9172.355279.42359194.156266.84829254.671239.31719284.928228.06729325.271216.5587
9335.357207.46469345.443201.34699365.614195.33169385.785180.67899410.831 168.332
9426.128164.49249436.214164.05689476.557151.9172  9516.9  150.549687.677152.5962
9777.708149.32539908.113148.92989928.245146.99789968.738147.11189978.861138.7049
9999.108136.293110019.33137.564710039.55   146.110059.69149.596910099.83151.7999
 10119.9148.811410129.92149.321910169.93 156.66610189.93152.754710203.56157.1084
#Mann= 3 , 0 , 0
9172.355  0.0838       09172.355  0.0838       010203.56  0.0838       0
#XS Ineff= 2 , 0
       0                               0
Bank Sta=9172.355,10203.56
Exp/Cntr=0.3,0.1

Type RM Length L Ch R = 1 ,26519.44,248.295300,248.295300,248.295300
XS GIS Cut Line= 6
 576373.62368442731233.529593236576198.408225012731199.325830781
576078.892055937 731171.43010318575649.648580902731055.970399239
 575551.41097462731024.822693116575317.428346372730941.947847344
#Sta/Elev= 30
9113.325259.1571 9132.21257.54859152.544252.17519244.339208.40089254.538 205.178
9264.738204.21139285.137196.3576 9295.36194.64869305.629191.08199315.897185.5691
9326.166181.89249336.435 173.5789346.704168.3068 9377.51157.64349480.505151.5932
9905.942146.90249926.923145.25899937.413141.65399958.395141.57439968.973143.0263
9979.599137.71219990.226135.344110011.48134.336310022.08 140.10310043.29163.1831
10050.98168.243710085.71184.573210111.07194.219910138.73200.636810210.39 206.654
#Mann= 3 , 0 , 0
9113.325  0.0708       09113.325  0.0708       010210.39  0.0708       0
#XS Ineff= 2 , 0
       0                               0
Bank Sta=9113.325,10210.39
Exp/Cntr=0.3,0.1

Type RM Length L Ch R = 1 ,26271.14,248.295300,248.295300,248.295300
XS GIS Cut Line= 6
 576421.45824209731169.931374521576201.081228878731111.649536227
576095.807885628731074.722053125575941.966705969731006.377989479
575753.408993662730887.876281197575408.158264266730623.060554022
#Sta/Elev= 30
9128.146216.77749155.236226.50119165.516228.09479196.357 224.425 9235.84213.7751
9258.329204.25139279.052200.92179299.842192.32469341.645170.50289373.233163.1812
9559.954151.46819655.585151.43579701.396147.70699927.934144.77969959.333142.6169
9976.094136.33369992.147133.789810010.46134.027610024.25140.8848 10040.3144.1127
10048.82149.1636 10061.6165.837810074.39176.742310112.74202.012710150.66221.7804
10170.23226.303310221.02249.282810238.51254.358510255.99 265.34410294.36284.1199
#Mann= 3 , 0 , 0
9128.146  0.0665       09128.146  0.0665       010294.36  0.0665       0
#XS Ineff= 2 , 0
       0                               0
Bank Sta=9128.146,10294.36
Exp/Cntr=0.3,0.1

Type RM Length L Ch R = 1 ,26022.85,248.295300,248.295300,248.295300
XS GIS Cut Line= 6
576499.825201356731065.738940048576225.797295642730967.305655057
576006.814772125730830.836591862575902.107866465730730.092826338
 575724.76135504730510.050244058575543.081210866730354.034224254
#Sta/Elev= 30
9176.241216.99219254.179209.18249275.148200.76579306.796197.72319317.419194.0759
9349.288199.25249392.313195.52769435.791184.70079468.706169.18659570.603154.1227
9728.829146.34379851.107145.34829930.564138.35289943.191138.25029955.691141.7388
9993.188131.440910012.98132.765410030.51147.047410041.52149.402110124.32150.9663
10139.29159.272210182.31206.369310190.35212.785310196.33216.855910210.35217.9377
10237.53237.677310264.61249.187710295.38255.518210326.43257.137510394.38252.9613
#Mann= 3 , 0 , 0
9176.241  0.0619       09176.241  0.0619       010394.38  0.0619       0
#XS Ineff= 2 , 0
       0                               0
Bank Sta=9176.241,10394.38
Exp/Cntr=0.3,0.1

Type RM Length L Ch R = 1 ,25774.55,248.295400,248.295400,248.295400
XS GIS Cut Line= 6
576401.191727386730694.889357793576319.563829065730655.257968221
576219.531587804730600.387948412576127.877652733730545.034946157
575746.702680661730291.730793248575613.220875906730206.740927664
#Sta/Elev= 30
9548.316179.16449689.884176.33049782.915168.52749805.172164.03729816.854158.2915
9828.536154.55039840.945153.01589860.286147.76079934.949141.0101 9971.32139.9776
9982.487136.97529994.379128.952110008.02132.056210030.49134.413310042.55138.9986
10054.61140.515410114.92140.301110139.04142.848710168.98156.628610199.35160.1684
10204.75 162.70710211.41168.637210223.47184.490310247.59 188.28110259.66197.1133
10414.77203.256710423.54204.558410442.16210.713310462.19221.096410476.15 226.579
#Mann= 3 , 0 , 0
9548.316  0.0649       09548.316  0.0649       010476.15  0.0649       0
#XS Ineff= 2 , 0
       0                               0
Bank Sta=9548.316,10476.15
Exp/Cntr=0.3,0.1

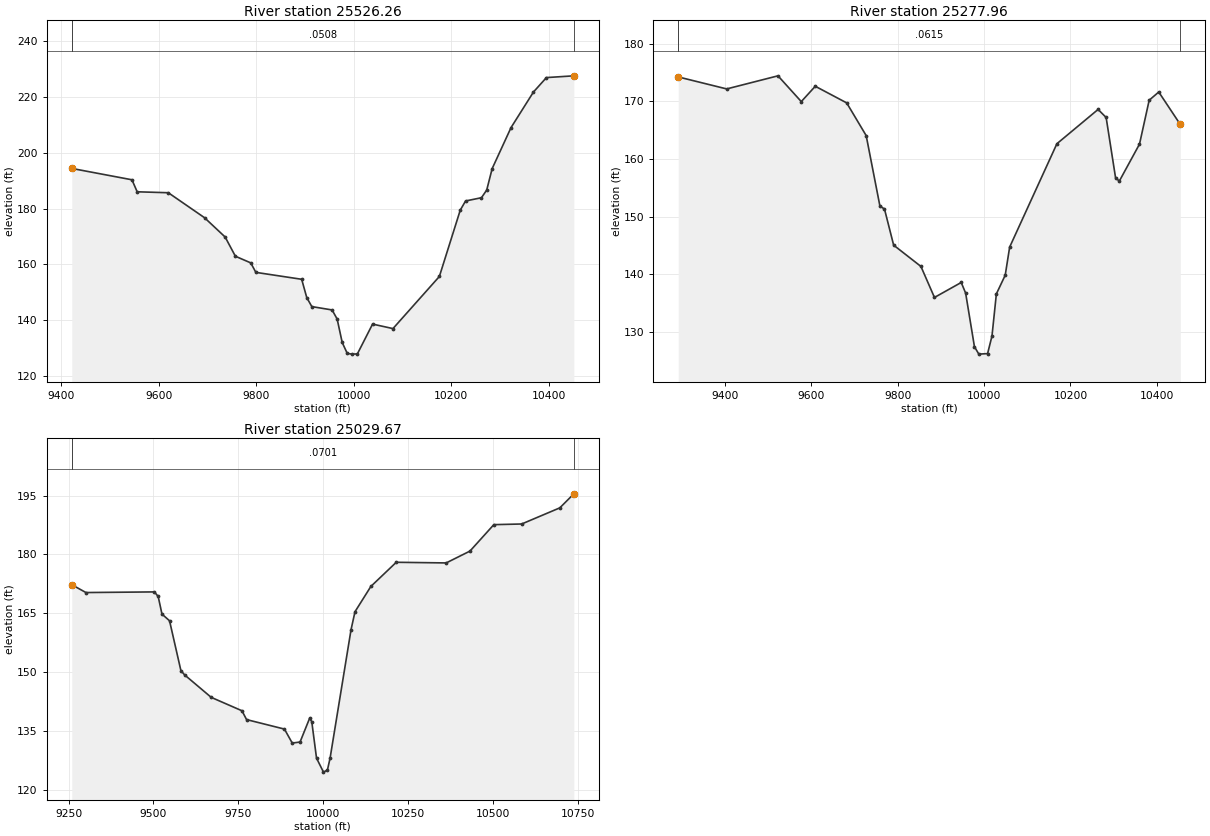
Type RM Length L Ch R = 1 ,25526.26,248.295300,248.295300,248.295300
XS GIS Cut Line= 6
576640.717739614730418.269982166576354.363502861730314.141406685
 576241.22755889730278.103468531575969.328970536730199.464254477
575835.088240431730146.378019165575675.312972026730066.560970999
#Sta/Elev= 30
9421.662194.39389545.097190.32569555.764186.02469619.649185.68259693.882176.7354
9736.198169.80929757.188162.92529788.673160.54779799.168157.14439893.123154.6667
 9903.51148.11939913.897144.87749955.443143.6799 9965.83140.43929976.217 132.017
9986.603128.0882 9996.99127.845610007.36127.933910038.47138.607610080.31136.9986
10175.45155.670410218.34179.467510229.21182.732110261.81183.903810272.58186.6656
10283.74194.340710322.42209.035410368.36221.772610395.01 226.95410451.22227.5828
#Mann= 3 , 0 , 0
9421.662  0.0508       09421.662  0.0508       010451.22  0.0508       0
#XS Ineff= 2 , 0
       0                               0
Bank Sta=9421.662,10451.22
Exp/Cntr=0.3,0.1

Type RM Length L Ch R = 1 ,25277.96,248.295300,248.295300,248.295300
XS GIS Cut Line= 6
576808.922561043730230.656912104576324.170485237730040.766991247
576214.482990824730008.292992198576072.104022208729979.532060748
575980.425361641729950.604275392575720.507233419729832.616434949
#Sta/Elev= 30
9292.088174.22799404.254172.14589522.978174.41899576.944169.94799609.324 172.609
9682.017169.72449727.153164.0496 9758.94151.82869769.535151.30659790.727145.0441
9853.885141.35079885.199135.96949947.158138.56819957.395136.72029977.783127.4233
9987.925126.137910008.21126.229810018.36129.277810028.52136.585410049.01139.8312
10059.28144.707310168.68162.6415   10264168.588610282.62167.193810304.51156.7036
10313.22156.166410359.84162.569510382.26170.1872 10404.4171.612410454.32165.9784
#Mann= 3 , 0 , 0
9292.088  0.0615       09292.088  0.0615       010454.32  0.0615       0
#XS Ineff= 2 , 0
       0                10073.52       0
Bank Sta=9292.088,10454.32
Exp/Cntr=0.3,0.1

Type RM Length L Ch R = 1 ,25029.67,248.295300,248.295300,248.295300
XS GIS Cut Line= 6
576914.710042855730112.663182388576774.238003229730047.212222126
576546.116775976729934.314659386576390.592382177 729851.94582745
576180.625913783729731.128554089575623.883071098729393.415697012
#Sta/Elev= 30
9259.612172.27049301.434170.27199502.994170.43549514.152169.2683 9525.31164.7777
9547.625163.06429581.098150.34889592.255149.24329670.376143.52699760.904140.1087
9774.479137.85459886.044135.43349909.049131.86719932.055132.12779960.334138.2198
9966.563137.32059980.569128.019210001.08124.448810012.68124.983910020.52 128.022
10082.28160.820110093.92165.387110140.63171.829410215.42177.9947 10362.5177.8291
10432.56180.852710502.83 187.59510584.86187.765310697.12191.878210738.52 195.462
#Mann= 3 , 0 , 0
9259.612  0.0701       09259.612  0.0701       010738.52  0.0701       0
#XS Ineff= 2 , 0
       0 9661.61                       0
Bank Sta=9259.612,10738.52
Exp/Cntr=0.3,0.1