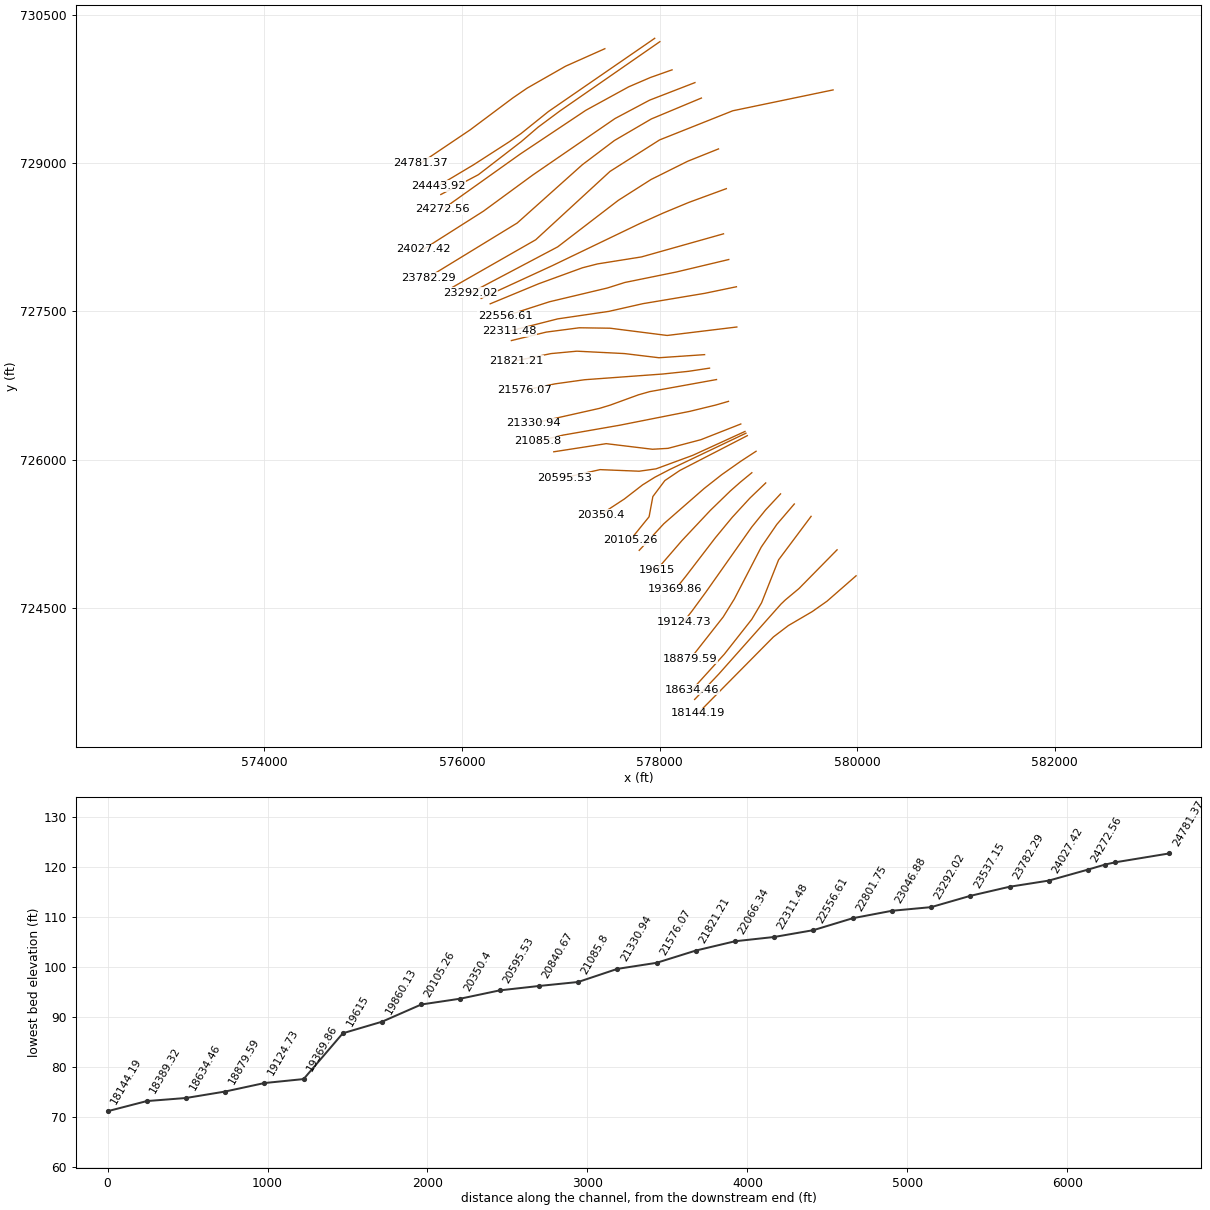
HEC-RAS study 2300_ras.prj: 2300

--- 2300_ras.g01 (geometry) --- (continued)

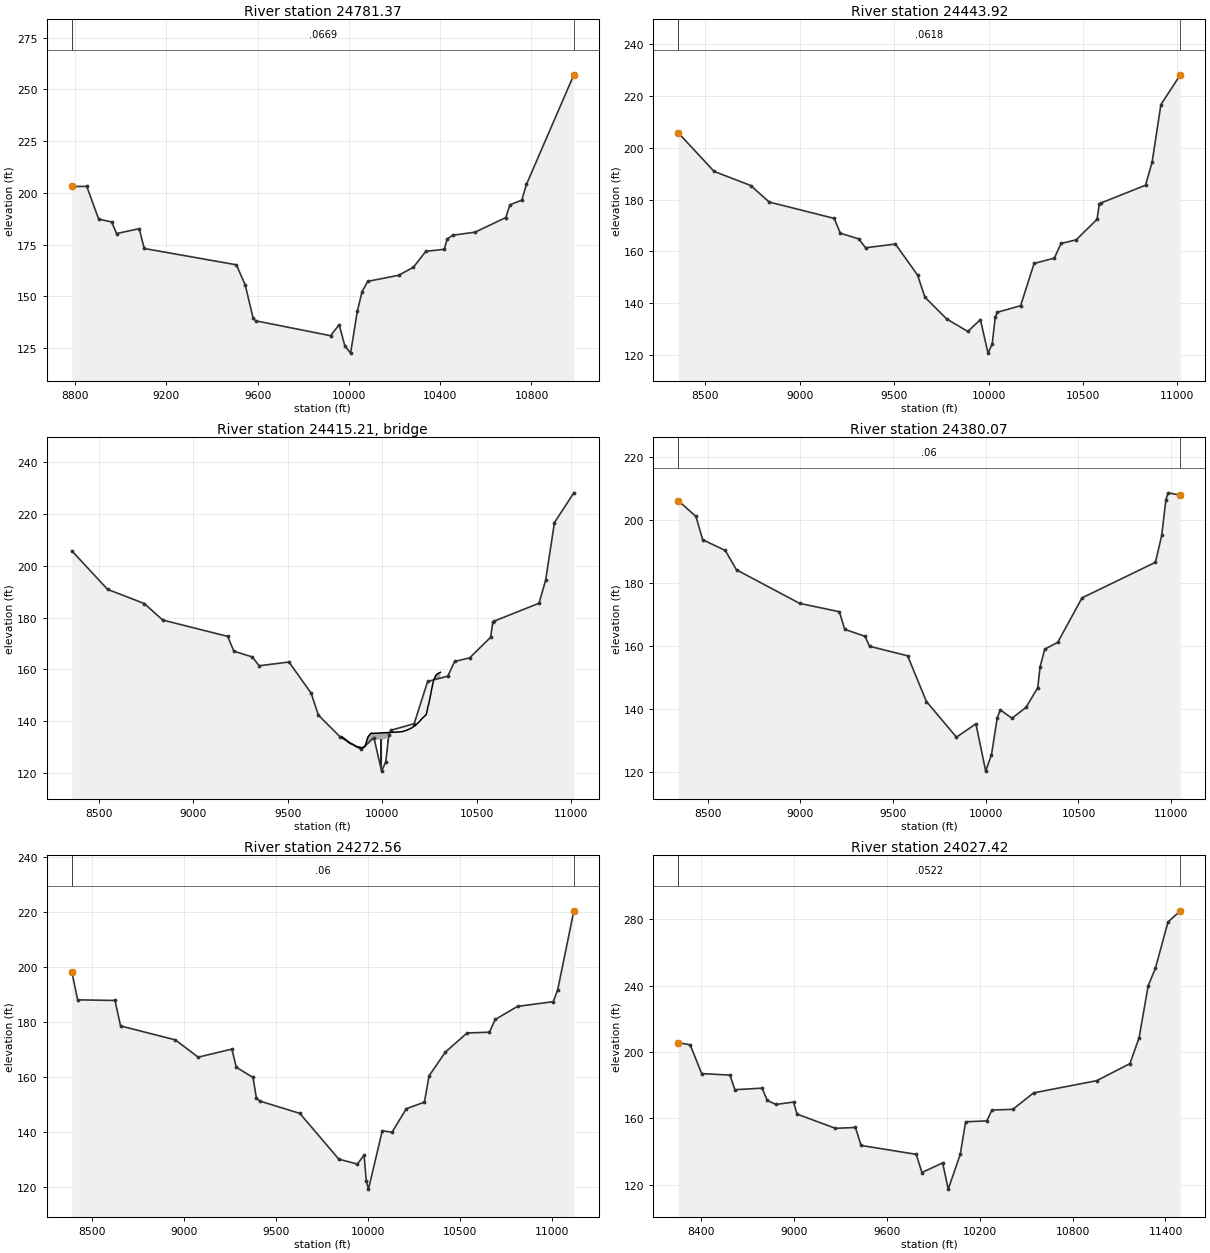
Type RM Length L Ch R = 1 ,24781.37,337.451100,337.451100,337.451100
XS GIS Cut Line= 6
 577446.57453511730159.042503878577048.498266526729981.676141068
576659.607831648729759.716910707576514.461287538729660.213193715
576082.814981821729337.347708308575583.896815349729001.448324563
#Sta/Elev= 30
8785.174203.13838851.011203.1753 8902.97187.38968959.779186.00498981.667180.4019
9080.633182.75759102.849173.18199506.463165.30559545.075155.68589580.448139.3803
9592.209138.23019919.493131.06519957.024136.35689982.044126.162710007.08122.6407
10036.64142.8113 10057.3152.246210082.41157.306310218.55160.259710282.65164.1546
10337.06171.829810418.12172.779410430.32177.766110454.74179.582510552.85181.0687
10687.62 188.14210705.45194.303410757.44 196.50910777.91204.127110985.68257.0627
#Mann= 3 , 0 , 0
8785.174  0.0669       08785.174  0.0669       010985.68  0.0669       0
#XS Ineff= 2 , 0
       09651.958        10074.89       0
Bank Sta=8785.174,10985.68
Exp/Cntr=0.3,0.1

Type RM Length L Ch R = 1 ,24443.92,63.846800,63.846800,63.846800
XS GIS Cut Line= 6
577951.058695819730263.982299771576875.833761778729523.373932611
576598.413684216729300.379944141576478.357770737729216.513133715
576118.241541412728984.395776387575756.898614463728768.617630925
#Sta/Elev= 30
8357.656205.70128547.289190.8368 8741.71185.38178838.921179.0351 9183.17 172.734
9215.614167.02869312.824164.83929349.279161.43089507.246162.86779624.566150.8977
 9663.27142.40259778.583134.02419890.712129.20199956.942133.77379997.527120.8683
10019.45124.385610035.82134.756510046.31136.5965 10169.9139.128810241.28155.3879
10348.36157.449810384.05163.077810464.02164.484110574.41172.3758 10586.3178.2151
10593.23178.606110831.06185.507910866.01 194.414 10912.6216.558811015.21228.0038
#Mann= 3 , 0 , 0
8357.656  0.0618       08357.656  0.0618       011015.21  0.0618       0
#XS Ineff= 2 , 0
       09683.843        10064.99       0
Bank Sta=8357.656,11015.21
Exp/Cntr=0.3,0.1

Type RM Length L Ch R = 3 ,24415.21,,,
BEGIN DESCRIPTION:
END DESCRIPTION:
Bridge Culvert--1,0,-1,-1, 0
Deck Dist Width WeirC Skew NumUp NumDn MinLoCord MaxHiCord MaxSubmerge Is_Ogee
21.423400,21.000000,2.6,0, 34, 34, , , 0.95, 0, 0,0,,
 9787.19 9811.90 9820.88 9833.60 9846.32 9860.43 9893.36 9896.80 9910.02 9921.80
 9926.69 9934.30 9938.03 9943.47 9944.73 9961.63 9961.6310057.6310057.6310107.34
10132.3110157.9010178.4810194.5210210.5610234.6410242.6310247.4310258.6710260.22
10273.0210285.8110298.6010308.64
  134.15  132.72  132.03  131.42  131.10  130.42  129.89  129.93  130.38  133.25
  134.21  134.82  135.23  135.54  135.39  135.45  135.45  135.81  135.81  136.05
  136.66  137.53  138.63  139.68  141.00  142.72  145.65  146.76  150.85  151.53
  155.95  157.90  158.55  158.91
 -865.85 -867.28 -867.97 -868.58 -868.90 -869.58 -870.11 -870.07 -869.62 -866.75
 -865.79 -865.18 -864.77 -864.46 -864.61 -864.55  132.95  133.31 -864.19 -863.95
 -863.34 -862.47 -861.37 -860.32 -859.00 -857.28 -854.35 -853.24 -849.15 -848.47
 -844.05 -842.10 -841.45 -841.09
 9787.19 9811.90 9820.88 9833.60 9846.32 9860.43 9893.36 9896.80 9910.02 9921.80
 9926.69 9934.30 9938.03 9943.47 9944.73 9967.71 9967.7110063.7110063.7110107.34
10132.3110157.9010178.4810194.5210210.5610234.6410242.6310247.4310258.6710260.22
10273.0210285.8110298.6010308.64
  134.15  132.72  132.03  131.42  131.10  130.42  129.89  129.93  130.38  133.25
  134.21  134.82  135.23  135.54  135.39  135.47  135.47  135.83  135.83  136.05
  136.66  137.53  138.63  139.68  141.00  142.72  145.65  146.76  150.85  151.53
  155.95  157.90  158.55  158.91
 -865.85 -867.28 -867.97 -868.58 -868.90 -869.58 -870.11 -870.07 -869.62 -866.75
 -865.79 -865.18 -864.77 -864.46 -864.61 -864.53  132.97  133.33 -864.17 -863.95
 -863.34 -862.47 -861.37 -860.32 -859.00 -857.28 -854.35 -853.24 -849.15 -848.47
 -844.05 -842.10 -841.45 -841.09
Pier Skew, UpSta & Num, DnSta & Num=  ,9993.13, 2 ,9999.21, 2 , 0 , 0 , 0 ,,
    3.00    3.00
 -864.43  135.57
    3.00    3.00
 -864.41  135.59
Pier Skew, UpSta & Num, DnSta & Num=  ,10026.13, 2 ,10032.21, 2 , 0 , 0 , 0 ,,
    3.00    3.00
 -864.31  135.69
    3.00    3.00
 -864.29  135.71
BR Coef=-1 , 0 , 0 ,, 0 ,,,0.8,0,1,0,
WSPro=,,,, 1 ,,,, 0 ,,,, 0 ,,,,-1 ,-1 ,-1 , 0 , 0 , 0 , 0 , 0
BC Design=,, 0 ,, 0 ,,,,,,

Type RM Length L Ch R = 1 ,24380.07,107.518700,107.518700,107.518700
XS GIS Cut Line= 6
578003.404069563730230.170789814576992.846439978729529.595660022
576770.281237295729364.343385046576601.208100458729219.150634801
576166.585065117 728883.87000755575786.238377859728683.043497792
#Sta/Elev= 30
8340.708206.1437 8436.11201.16428472.614193.76358594.294190.37568655.134184.2191
8995.838173.5886 9209.83170.94689239.198165.3452 9348.71163.15649373.046 159.992
9578.064156.98329679.768 142.4769841.685 131.1859946.792135.41749999.517120.4197
10030.75125.628410061.44137.221810078.26139.829110141.41137.187610217.19140.6224
10280.34146.865110292.97153.476810318.23159.068610388.28161.253710519.26175.3365
10915.15186.602610949.07195.131510971.69206.3876   10983208.631811049.45207.8957
#Mann= 3 , 0 , 0
8340.708    0.06       08340.708    0.06       011049.45    0.06       0
#XS Ineff= 2 , 0
       0  9689.6        10082.51       0
Bank Sta=8340.708,11049.45
Exp/Cntr=0.3,0.1

Type RM Length L Ch R = 1 ,24272.56,245.134800,245.134800,245.134800
XS GIS Cut Line= 6
578126.653937185 729944.97874656577908.399701393729867.888863573
577688.667450097729773.527235963577253.846073061 729535.47796541
576589.599765504729092.387339435575802.233776708728532.029728488
#Sta/Elev= 30
8389.452198.37738421.482188.13728624.638187.92248654.839178.67468953.114173.5983
9077.154167.32229260.535170.26059284.641 163.676 9375.44159.95879393.863152.5543
9412.287151.39539630.429146.91159842.368130.28499943.982128.50259979.851131.8145
9991.807 122.45310003.74 119.40710078.99140.602510132.26140.063110209.52 148.612
10308.29151.003910333.11160.516310422.24169.178310540.38176.117710661.77176.3876
10693.18 181.01110814.77 185.77311009.53187.4828 11033.6191.896811121.18220.4706
#Mann= 3 , 0 , 0
8389.452    0.06       08389.452    0.06       011121.18    0.06       0
#XS Ineff= 2 , 0
       09702.815        10095.81       0
Bank Sta=8389.452,11121.18
Exp/Cntr=0.3,0.1

Type RM Length L Ch R = 1 ,24027.42,245.134700,245.134700,245.134700
XS GIS Cut Line= 6
578358.330902936729815.824048508577899.536291192729638.321124162
577549.105552803729451.875375476576715.584430702728879.498751988
576218.184450156728514.885321188575606.736946061728126.594515404
#Sta/Elev= 30
8253.936205.5519 8330.86204.36398405.272186.96648587.496186.04248619.852177.2264
8795.719178.18128829.054170.72318884.976168.32518998.226169.7723  9021.1162.5004
9269.231153.91969398.144154.42779434.611143.57579790.665138.21139827.608127.2435
9961.088133.01419997.412117.208210074.63138.124710109.83157.880110246.28 158.391
10279.89164.979610414.33165.375610548.78175.316510956.31182.678411170.71 192.979
11229.77 208.57411288.17239.901311334.89250.482711416.65278.522111495.95285.2157
#Mann= 3 , 0 , 0
8253.936  0.0522       08253.936  0.0522       011495.95  0.0522       0
#XS Ineff= 2 , 0
       09739.075        10105.87       0
Bank Sta=8253.936,11495.95
Exp/Cntr=0.3,0.1

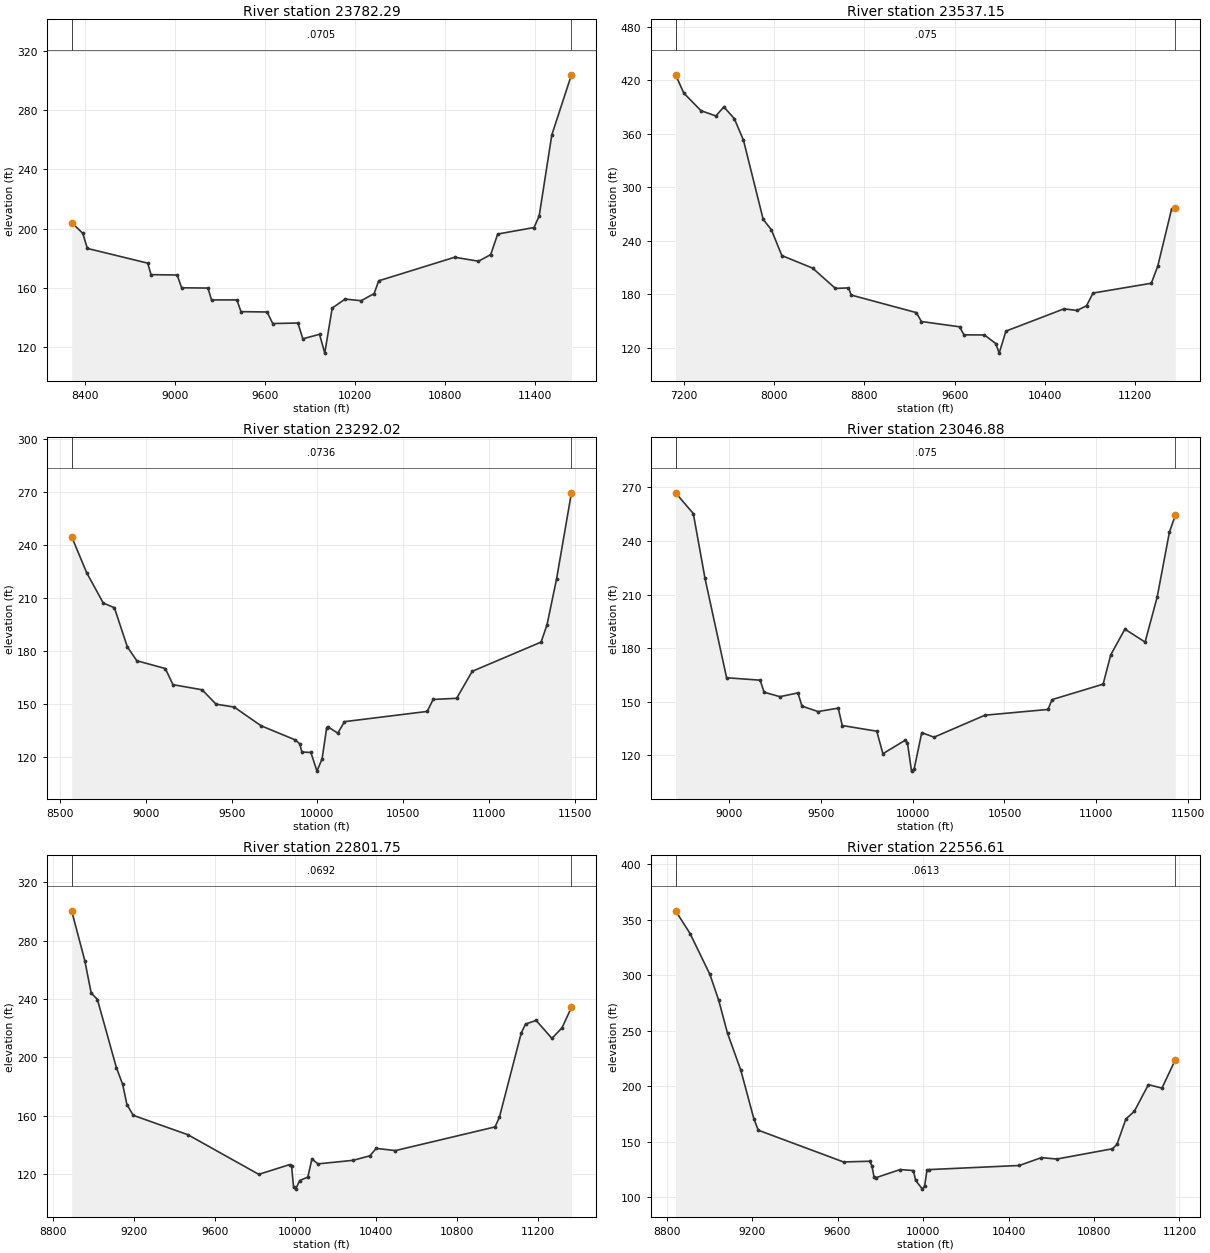
Type RM Length L Ch R = 1 ,23782.29,245.134800,245.134800,245.134800
XS GIS Cut Line= 6
578423.756803746729659.646091733577916.756985245729447.902303515
577544.223169524729230.292440859577219.339685201728985.208072015
576559.633773754728394.801215266575656.393632772727842.576674884
#Sta/Elev= 30
8310.368204.1645 8384.36 196.8588415.241186.66358817.731 176.7288839.978168.9688
9014.602168.70979044.107160.0943 9219.84159.90919243.568151.89989412.683 151.904
9440.278143.98429614.368 143.7429651.976135.96519820.117136.30199852.773125.6581
9964.194128.7009    9999115.980110048.75146.397610134.84 152.47310242.55151.3738
10328.51156.201310359.03164.801210865.76180.712611024.65178.036711106.27182.4976
11152.87196.383411395.31200.7754 11429.8208.644911513.79263.248711644.83303.8659
#Mann= 3 , 0 , 0
8310.368  0.0705       08310.368  0.0705       011644.83  0.0705       0
#XS Ineff= 2 , 0
       09787.378        10087.56       0
Bank Sta=8310.368,11644.83
Exp/Cntr=0.3,0.1

Type RM Length L Ch R = 1 ,23537.15,245.134800,245.134800,245.134800
XS GIS Cut Line= 6
579756.961044852729741.921489728578741.370603887729530.670094665
578001.114781248729235.953618852577499.056178801728917.161971615
576746.540405299 728224.77263524   575905.834858727744.666101281
#Sta/Elev= 30
7128.712426.22467201.451405.74427353.234386.0594 7485.22380.11137556.289390.2868
7648.178377.1844 7729.88352.88567904.403264.16277976.427252.57038069.797 223.544
8341.606209.54098543.922186.71968659.432 187.334 8684.36179.2531 9260.28159.5961
9305.364149.59779643.012143.70199682.555134.6639  9863.2134.53619964.164124.8707
9993.995114.164310053.84 138.83810567.96163.821610683.61161.985410767.45167.2839
10825.54181.534711341.23192.524811397.76211.496411521.52276.065411554.24276.4109
#Mann= 3 , 0 , 0
7128.712   0.075       07128.712   0.075       011554.24   0.075       0
#XS Ineff= 2 , 0
       09814.991        10091.26       0
Bank Sta=7128.712,11554.24
Exp/Cntr=0.3,0.1

Type RM Length L Ch R = 1 ,23292.02,245.134700,245.134700,245.134700
XS GIS Cut Line= 6
578597.084472418729144.722273991578285.542171002729020.029467514
577913.393893335728834.599408898577582.843737424728624.234689378
576969.250387311728153.199816393576087.222075923727687.385927195
#Sta/Elev= 30
8566.174244.80688653.757224.36298750.533207.19068815.386204.52298891.519182.2607
8946.332174.47369112.657170.05339157.224160.91179327.447158.00719408.465149.8669
9514.318148.21959670.642137.6573 9870.98129.5922 9896.67127.38059909.514122.7509
9961.811122.48119997.477111.908610027.43118.954110053.62136.286410059.39137.1366
10119.11133.4466 10157.9139.949110640.56145.751510675.22152.527810812.16153.1926
10903.15168.4772 11305.1185.056311339.73194.941611395.38 220.91411481.94269.6372
#Mann= 3 , 0 , 0
8566.174  0.0736       08566.174  0.0736       011481.94  0.0736       0
#XS Ineff= 2 , 0
       09810.138        10121.11       0
Bank Sta=8566.174,11481.94
Exp/Cntr=0.3,0.1

Type RM Length L Ch R = 1 ,23046.88,245.134800,245.134800,245.134800
XS GIS Cut Line= 6
578676.280558907728742.496775531578295.535924161728602.765372569
578036.940884697728495.414565558577798.243661578728387.928239756
576911.743743503727961.580405981576195.057563485727631.612549979
#Sta/Elev= 30
 8710.06266.92038806.526255.30298870.269218.97998987.717163.43289170.239162.0701
 9191.83155.32379278.255152.8486 9376.06154.95949397.813147.5651 9485.55144.5139
9595.221 146.4329617.156136.69979805.021133.5224 9838.34120.92039960.803128.5467
9971.936126.99859994.202111.178310008.98 112.62310049.87132.735210116.63130.1661
10393.98142.478410736.92145.696910758.99151.200211036.95159.843511078.44176.2371
 11155.4190.635611265.33 183.403 11331.3208.664811397.96245.028911430.18254.4489
#Mann= 3 , 0 , 0
 8710.06   0.075       0 8710.06   0.075       011430.18   0.075       0
#XS Ineff= 2 , 0
       09731.728        10109.97       0
Bank Sta=8710.06,11430.18
Exp/Cntr=0.3,0.1

Type RM Length L Ch R = 1 ,22801.75,245.134700,245.134700,245.134700
XS GIS Cut Line= 6
578647.535178198728285.264167128577817.265859817728051.369191464
577372.220629615727980.554829046577219.197137284727941.233393355
576775.624808984727779.341449882576286.071959028 727576.73622326
#Sta/Elev= 30
8892.284300.42718957.439 266.2238988.695244.24869019.952239.59899113.722192.9425
9144.979181.43289165.816167.65479197.073160.26689467.761146.96939818.523119.8114
9970.596126.48039980.677125.60679990.759111.080710000.85109.6909   10021115.6019
 10061.3117.949610081.45 130.33810111.68127.0057 10285.2129.431310368.26132.5318
10399.73137.616410494.74136.102810988.05152.342311009.65159.044311117.66216.7207
11138.79222.792611191.29225.333311269.39212.995511319.26220.2185   11366234.2404
#Mann= 3 , 0 , 0
8892.284  0.0692       08892.284  0.0692       0   11366  0.0692       0
#XS Ineff= 2 , 0
       09754.638        10110.48       0
Bank Sta=8892.284,11366
Exp/Cntr=0.3,0.1

Type RM Length L Ch R = 1 ,22556.61,245.134800,245.134800,245.134800
XS GIS Cut Line= 6
 578700.91146785728025.054755052578170.267820675727898.750013505
577648.590129926727792.653883148577471.302528424727736.629550074
576885.675585919727597.381018942576435.855885671727452.351151779
#Sta/Elev= 30
8842.181357.92088910.065337.43059002.759300.65399043.956277.33399085.153247.6796
9146.854214.71799208.409170.66959228.927160.40029628.038131.78819750.276132.4344
9760.462128.53739770.648118.42619780.835117.70159893.027124.93559954.938124.0382
9965.325115.20419997.195107.312210007.85110.466410018.46124.407410029.07124.9144
   10451128.614810553.73135.6867 10626.1134.403210886.24143.657710907.25147.5363
10949.27170.4262 10988.8177.395711054.57201.365211118.16198.314611180.84223.8605
#Mann= 3 , 0 , 0
8842.181  0.0613       08842.181  0.0613       011180.84  0.0613       0
#XS Ineff= 2 , 0
       09711.663        10071.67       0
Bank Sta=8842.181,11180.84
Exp/Cntr=0.3,0.1

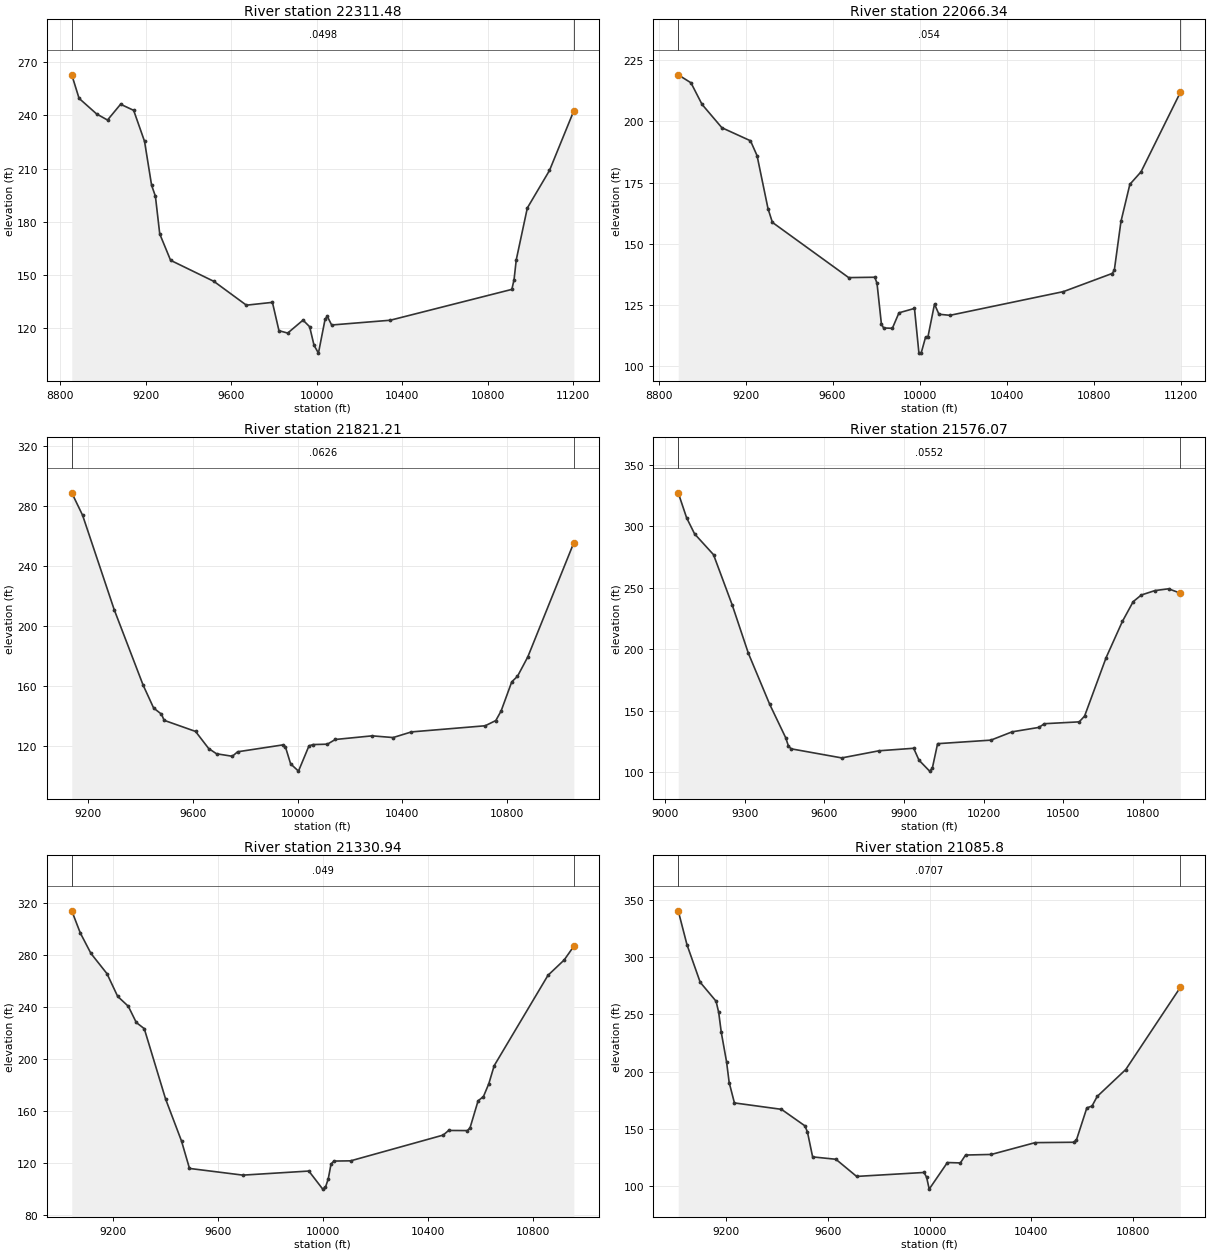
Type RM Length L Ch R = 1 ,22311.48,245.134700,245.134700,245.134700
XS GIS Cut Line= 6
578778.356266542727749.369704684578458.544404844727683.062001786
577831.116510011727578.121973431577487.246941105727500.167349021
576969.187515018  727424.1899406576475.998570087727298.701566592
#Sta/Elev= 30
 8854.84262.88058888.984249.62168970.875240.84299022.004237.38149083.159246.2908
9144.313242.85689195.221225.36229228.161200.63129245.984194.44999266.289 173.181
9317.051158.29349519.716146.4056 9671.57132.98739793.387134.58149823.893118.6024
9864.803117.25569936.501 124.5619967.388120.8397 9987.98 110.36110008.58105.9485
10039.45124.936110049.75126.754210070.33121.811510344.38 124.49610913.15141.8892
10923.49  147.3410933.84158.576210985.57187.794411089.17208.933611203.16242.6255
#Mann= 3 , 0 , 0
 8854.84  0.0498       0 8854.84  0.0498       011203.16  0.0498       0
#XS Ineff= 2 , 0
       09729.233        10114.55       0
Bank Sta=8854.84,11203.16
Exp/Cntr=0.3,0.1

Type RM Length L Ch R = 1 ,22066.34,245.134800,245.134800,245.134800
XS GIS Cut Line= 6
578782.296662867727342.021631589578077.186254969 727256.42373416
 577498.75714473727329.887205164577187.488383664   727334.071422
576853.155994696727290.359606075576500.557761088727204.699145858
#Sta/Elev= 30
8890.685219.11698949.195215.85369000.042207.01239091.318197.44169222.757 192.099
9253.018186.00649303.429 164.259 9323.54 158.6599674.188136.03829794.364136.1878
9804.431133.66919824.576117.02239834.649115.41089874.939115.26339905.336121.6135
9976.609123.40819997.055105.131810007.27105.094110027.73111.686910037.97111.4999
10068.67 125.17310089.14121.026210139.81120.587510661.58130.306510884.86137.7174
10895.08138.986210925.76159.040810966.67174.251711018.09179.384111198.58 211.895
#Mann= 3 , 0 , 0
8890.685   0.054       08890.685   0.054       011198.58   0.054       0
#XS Ineff= 2 , 0
       09736.267        10122.79       0
Bank Sta=8890.685,11198.58
Exp/Cntr=0.3,0.1

Type RM Length L Ch R = 1 ,21821.21,245.134800,245.134800,245.134800
XS GIS Cut Line= 6
578455.979081732727062.289609445577994.311063735727030.777146855
577644.062936747727073.121250649577162.982210844727097.269389725
576903.193551844727073.087312849576553.608518798727001.642797369
#Sta/Elev= 30
9138.015288.54469179.346273.60539300.107210.69119410.454160.48339450.513145.2676
9480.547141.13299490.547137.07159610.559129.66579660.608118.28869690.708114.7877
9750.968113.12959771.173  116.119943.427120.68439953.502119.4638 9973.51108.0734
10003.51103.234310043.51120.029710059.01120.921710113.85121.177810144.04 124.305
10284.64126.727110364.71 125.59310434.71129.348910716.22133.4346 10756.8136.9142
10777.09143.304410817.67162.6901 10839.6166.386610878.89179.273911054.71255.3732
#Mann= 3 , 0 , 0
9138.015  0.0626       09138.015  0.0626       011054.71  0.0626       0
#XS Ineff= 2 , 0
       0                10078.05       0
Bank Sta=9138.015,11054.71
Exp/Cntr=0.3,0.1

Type RM Length L Ch R = 1 ,21576.07,245.134700,245.134700,245.134700
XS GIS Cut Line= 6
 578506.15916226726925.534563945578295.587613877726893.735045307
578032.413390655726866.119341807577243.015138941726808.402059655
576943.642711242726766.687469883576631.858401228726702.134626671
#Sta/Elev= 30
9050.288327.25619081.912306.88919111.953 293.8229183.081276.93449253.767235.8343
9314.196196.75039394.706155.10679454.982127.89539465.028121.28339475.074118.9488
9665.788111.54049806.269117.34759936.618119.38759956.647109.69689996.654100.7839
10006.66102.998810026.66123.1246 10227.2126.002610307.59132.781310408.32136.3746
10428.48 139.37110559.85140.882810580.08145.610410661.22 193.23410722.23222.5645
10762.97238.699810793.67 244.11910844.82247.705210895.98  249.1610940.39245.6173
#Mann= 3 , 0 , 0
9050.288  0.0552       09050.288  0.0552       010940.39  0.0552       0
#XS Ineff= 2 , 0
       09527.247        10057.27       0
Bank Sta=9050.288,10940.39
Exp/Cntr=0.3,0.1

Type RM Length L Ch R = 1 ,21330.94,245.134800,245.134800,245.134800
XS GIS Cut Line= 6
578576.612869096726810.068766648577899.496823086726687.601633523
 577786.50785467726655.523108022577501.064694099726551.386883211
 577393.79094432726518.735362529 576719.31681043726367.380025911
#Sta/Elev= 30
9041.058 313.6299073.409 296.6739114.119280.86169175.184265.31399215.894247.8474
9256.493240.2144  9286.9 227.7389317.308222.98249398.395 168.9829459.211136.5658
9489.618115.49449693.011110.34149944.384113.48229997.43999.5772610007.84101.1415
10018.32107.428810028.91118.7764 10039.6 121.16210103.73  121.3410456.52141.1569
10476.95144.706810548.45144.605310558.67146.746710589.31167.508710609.74170.7911
10630.17180.6638 10650.6194.522110855.61264.029510917.26275.811110954.17286.4033
#Mann= 3 , 0 , 0
9041.058   0.049       09041.058   0.049       010954.17   0.049       0
#XS Ineff= 2 , 0
       09568.683         10078.5       0
Bank Sta=9041.058,10954.17
Exp/Cntr=0.3,0.1

Type RM Length L Ch R = 1 , 21085.8,245.134700,245.134700,245.134700
XS GIS Cut Line= 6
578697.905663663 726589.38715946578569.149957948726552.162620523
578306.283463946726488.161854084577595.207703219726347.472021017
577024.871728031726248.101183151576766.807720649726185.604472994
#Sta/Elev= 30
9011.393340.81349045.804311.08819097.822278.17889160.038 261.649 9170.36251.9595
9180.683234.22339201.328208.60439211.651190.36619232.296172.4935 9417.31166.8717
9509.218152.44539519.421147.01559539.766125.20799631.318123.11519712.697108.0938
9977.692111.55229987.909107.44839998.12696.9554810069.62120.260610120.68119.9177
10141.11 126.82910242.45127.350110414.73 137.69210566.96138.031510577.15   140.1
10617.89168.141610638.26169.769310658.63178.162810771.02201.773210985.43273.7227
#Mann= 3 , 0 , 0
9011.393  0.0707       09011.393  0.0707       010985.43  0.0707       0
#XS Ineff= 2 , 0
       0                10109.09       0
Bank Sta=9011.393,10985.43
Exp/Cntr=0.3,0.1

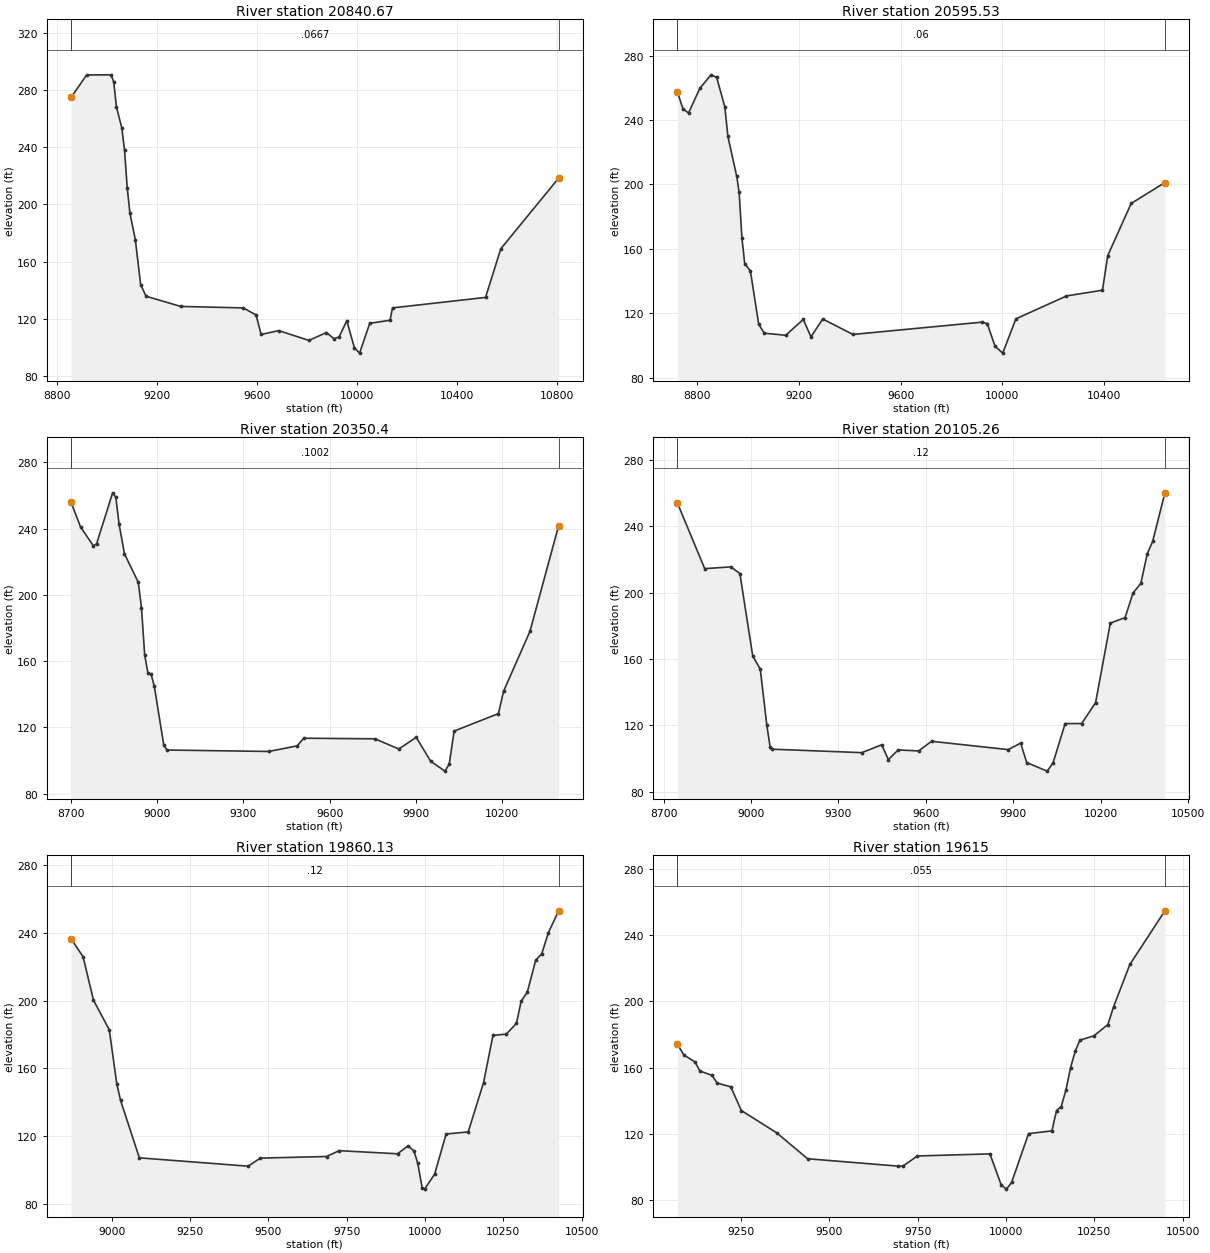
Type RM Length L Ch R = 1 ,20840.67,245.134800,245.134800,245.134800
XS GIS Cut Line= 6
578822.541002599726360.114802426578418.371372203726201.247988655
578085.941621349726113.648115483577928.361661392726104.547727877
577460.542243069726161.188025723576929.438823329726078.869798052
#Sta/Elev= 30
 8857.58274.70968919.858290.44729017.241290.5278 9027.97285.67679038.882268.1299
9060.503253.33869071.244237.76449081.985211.67259092.726193.91729114.208175.4954
 9135.69144.00579157.056 135.9129295.467128.77789545.575 127.7389596.499122.8226
9616.815109.18499687.436111.88539807.601105.04329877.873110.51439908.232106.1683
9928.471107.56339958.986118.78159989.59399.7277310009.99 96.158810050.72116.9873
10131.59119.139210141.66127.759410513.23135.056310574.11169.052710804.94218.3421
#Mann= 3 , 0 , 0
 8857.58  0.0667       0 8857.58  0.0667       010804.94  0.0667       0
#XS Ineff= 2 , 0
       09841.372        10093.19       0
Bank Sta=8857.58,10804.94
Exp/Cntr=0.3,0.1

Type RM Length L Ch R = 1 ,20595.53,245.134800,245.134800,245.134800
XS GIS Cut Line= 6
578864.831844207726284.641915866578337.504807903726043.424715163
577964.641358288725906.260096039577794.074105969725882.312971242
577398.274560107725898.288476023577037.343797188725816.814861556
#Sta/Elev= 30
8721.665257.4859 8743.59246.98558765.701244.32848809.922259.58218854.144 268.039
8876.255266.44398908.444248.11518920.476229.81178955.349204.92718964.698195.0237
8975.753166.73588986.809150.68449008.884146.48059041.817113.13699063.773107.6616
9147.637106.36069217.102116.15779247.426105.36179293.418116.47969412.504106.8783
9920.972114.53059941.076113.5735 9971.3399.6035210001.7295.2818510053.71116.5663
10252.59130.770810394.32134.351410414.83155.770410507.11188.181910639.87201.1678
#Mann= 3 , 0 , 0
8721.665    0.06       08721.665    0.06       010639.87    0.06       0
#XS Ineff= 2 , 0
       09898.194        10088.97       0
Bank Sta=8721.665,10639.87
Exp/Cntr=0.3,0.1

Type RM Length L Ch R = 1 , 20350.4,245.134700,245.134700,245.134700
XS GIS Cut Line= 6
578874.697715478726267.035130213578099.090512792725897.529516176
577951.541332304725820.797365418 577828.25332404725743.703106662
 577642.90245771725600.320389784577401.030769412725441.925728137
#Sta/Elev= 30
8700.893255.93428733.993241.06278778.575229.6105 8789.72230.92778845.448 261.664
8856.594258.95848867.739242.86648886.665224.77768934.601207.66518945.679192.2493
8956.758 163.9568967.837152.99428978.915152.32488989.994145.0765 9023.23109.3651
9034.309106.3728    9388105.50499487.318108.91599509.389113.50319757.326 113.138
 9839.87106.99789900.584114.02839950.78899.5864110000.5193.6289910015.3197.86996
10032.31117.813910186.41  128.38 10204.1141.835210295.88 178.03310395.39241.7503
#Mann= 3 , 0 , 0
8700.893  0.1002       08700.893  0.1002       010395.39  0.1002       0
#XS Ineff= 2 , 0
       09879.558        10055.73       0
Bank Sta=8700.893,10395.39
Exp/Cntr=0.3,0.1

Type RM Length L Ch R = 1 ,20105.26,245.134800,245.134800,245.134800
XS GIS Cut Line= 6
578888.553234418726242.308357952578205.391851856725889.812383942
578053.827209758725787.487071545577932.487417153 725625.91791384
577894.387901331725421.402616077  577702.9087583725184.772623038
#Sta/Elev= 30
8747.441254.21328841.195214.54188930.963215.59978961.952211.58429006.041161.8644
9031.951 153.9369054.393120.05629065.614107.11279072.175105.68859380.124103.6101
9448.398108.32829471.156  99.4249505.293105.24349575.203104.63369619.473110.4485
9882.591105.43079925.194109.34529945.86497.6285710016.0392.46144 10036.197.33791
10077.74121.132610134.36121.121810182.18133.754710232.74 181.69910283.36185.0264
10310.85199.958410337.47205.594610359.16223.306110377.91230.9127   10420260.2504
#Mann= 3 , 0 , 0
8747.441    0.12       08747.441    0.12       0   10420    0.12       0
#XS Ineff= 2 , 0
       09881.701        10104.96       0
Bank Sta=8747.441,10420
Exp/Cntr=0.3,0.1

Type RM Length L Ch R = 1 ,19860.13,245.134700,245.134700,245.134700
XS GIS Cut Line= 6
578977.144303751726084.207372683 578820.06113345725981.438465942
578628.816300817725846.668255269578452.716066389725708.167123523
 578043.05883668725350.286077808577794.621651491 725081.19100248
#Sta/Elev= 30
8870.454236.37258908.866225.72318942.068200.20848992.516182.72679016.416150.9707
9028.366141.30249088.535107.42939435.907102.52969474.584107.28049685.983108.2135
9726.361111.65899912.711109.82349945.906 114.4999964.937111.47019977.012104.3212
 9991.0589.89615    999989.0251410030.8797.8597410067.67121.478310138.07 122.663
10187.07151.695310217.06179.470710259.59180.233610292.04186.573610307.04199.5896
10326.68 204.91910353.52 223.77210372.62227.400110394.11 239.98410426.56252.7661
#Mann= 3 , 0 , 0
8870.454    0.12       08870.454    0.12       010426.56    0.12       0
#XS Ineff= 2 , 0
       09902.816        10099.81       0
Bank Sta=8870.454,10426.56
Exp/Cntr=0.3,0.1

Type RM Length L Ch R = 1 ,   19615,245.134800,245.134800,245.134800
XS GIS Cut Line= 6
578934.278404932725866.867661788578817.459383404725770.933004936
578716.219652889725681.628126255578515.301074584725486.683261044
578224.680936205725177.712360649577970.251749366724882.832303677
#Sta/Elev= 30
9069.979174.15099088.678167.59319120.192 163.3399133.744157.95579167.463155.3825
9183.219150.60339221.141148.4256 9251.09134.12279351.044120.67589438.536105.0524
9694.359100.5942 9708.81 100.702 9749.27106.69949954.496107.98059986.64689.20268
10001.2686.7145610015.9190.7275210063.88120.197510129.92121.850710143.13134.1272
10156.34136.532310169.55146.312410182.75159.966210195.96169.890510209.17176.5726
10248.79179.156310288.42185.960910304.74196.862710350.66222.240310449.77254.5661
#Mann= 3 , 0 , 0
9069.979   0.055       09069.979   0.055       010449.77   0.055       0
#XS Ineff= 2 , 0
       09909.678        10097.12       0
Bank Sta=9069.979,10449.77
Exp/Cntr=0.3,0.1

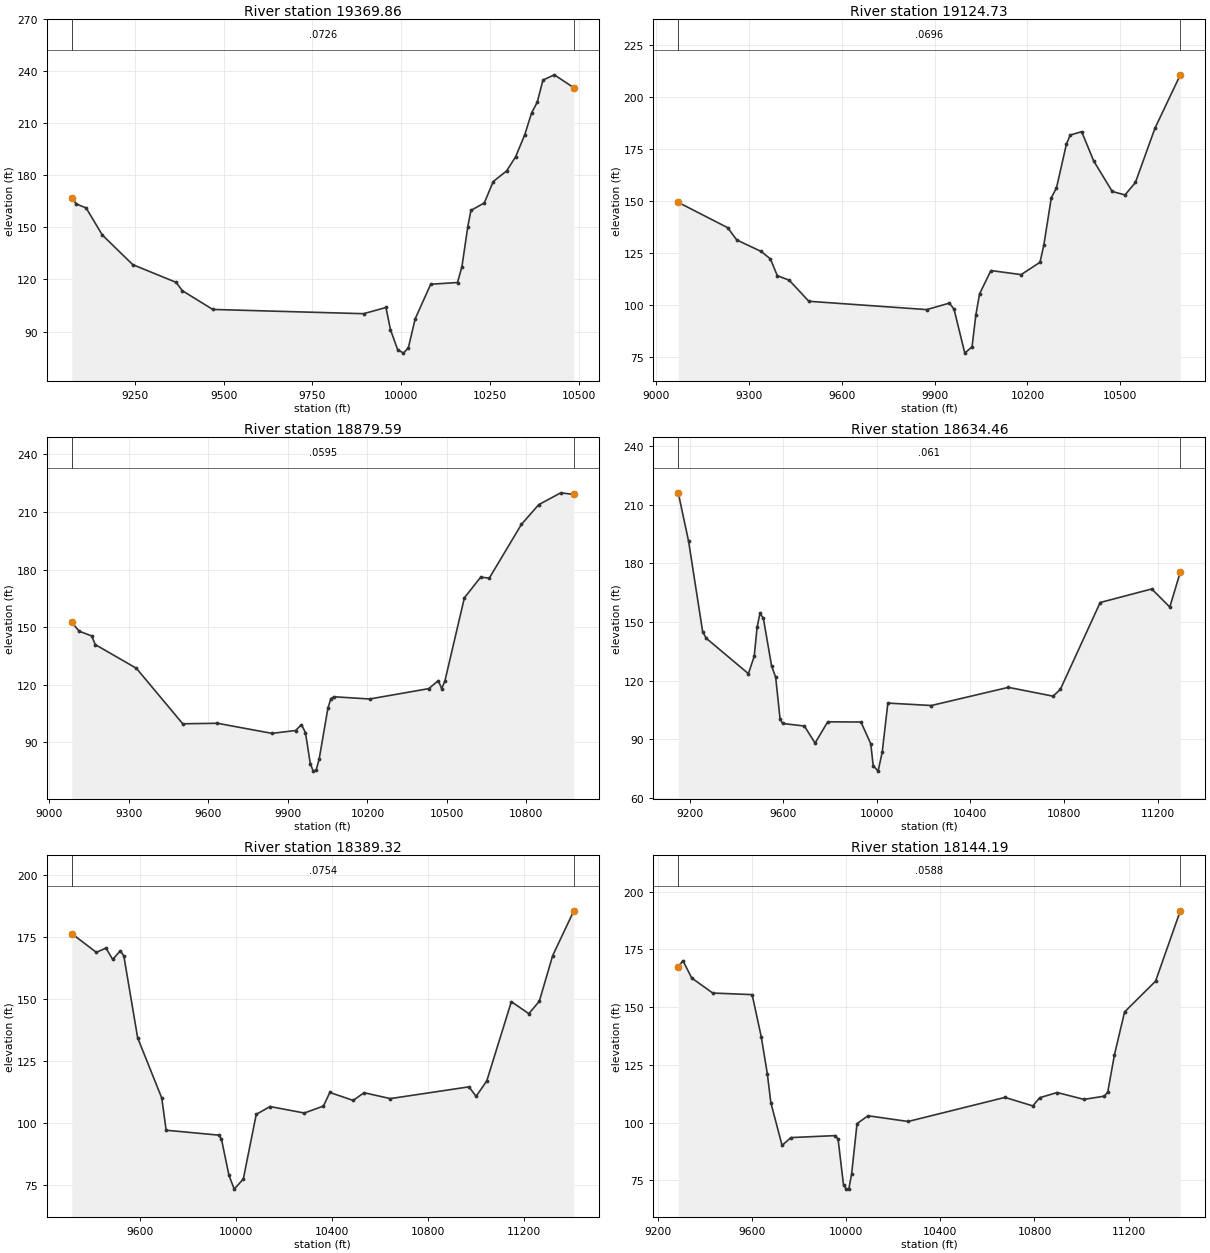
Type RM Length L Ch R = 1 ,19369.86,245.134700,245.134700,245.134700
XS GIS Cut Line= 6
579074.803129668725763.413876713578915.941909214725611.294399346
578734.548235594725413.975908646578562.881163832725205.858005808
578267.374597383724820.402795065578160.690656078724686.845672863
#Sta/Elev= 30
9071.884167.2467 9084.33163.5221 9112.33161.24369157.799 145.6759243.636128.5693
9365.736118.35899383.391113.54899469.128102.74289893.947100.29259957.095103.8671
9969.72491.06752 9989.9779.5823410006.4377.5655610020.1580.6860410039.3697.35551
10083.08117.258510158.59118.257610171.11127.456310187.58150.441510196.35159.8047
10234.11164.143610259.28176.451910297.04182.583910322.33190.744710347.92203.3374
10367.29215.991410383.31222.230310399.33234.912510431.38237.946210486.35230.5135
#Mann= 3 , 0 , 0
9071.884  0.0726       09071.884  0.0726       010486.35  0.0726       0
#XS Ineff= 2 , 0
       09844.495        10118.63       0
Bank Sta=9071.884,10486.35
Exp/Cntr=0.3,0.1

Type RM Length L Ch R = 1 ,19124.73,245.134800,245.134800,245.134800
XS GIS Cut Line= 6
579225.114700904725652.755051269579074.296153293725491.096138387
  578933.2640325725316.910304877578469.110653134724658.583847042
578329.148694408724467.448148136578245.218375399724360.762084653
#Sta/Elev= 30
9070.719149.30049230.552137.12189259.881131.22369338.875125.68989368.764 122.104
9390.985114.05459429.657111.84829493.063101.71639874.30997.708189947.538100.8451
9962.44197.944469997.32776.7709410020.7879.8238110032.9895.0607310045.19105.3325
 10081.8116.505210179.44 114.54310240.47120.460310252.68128.589310277.09151.5598
10293.82 156.28410325.95177.349810338.28181.690710375.27183.307610414.02169.2548
10474.04154.552710515.33152.880510549.01158.867110612.45185.060710694.19210.6582
#Mann= 3 , 0 , 0
9070.719  0.0696       09070.719  0.0696       010694.19  0.0696       0
#XS Ineff= 2 , 0
       09772.067        10121.11       0
Bank Sta=9070.719,10694.19
Exp/Cntr=0.3,0.1

Type RM Length L Ch R = 1 ,18879.59,245.134800,245.134800,245.134800
XS GIS Cut Line= 6
579364.187190506725550.370396355579187.176785674725343.794070157
579028.973361606725113.187034754578757.512102574724589.390238238
578645.029614751724407.680074258 578312.27715623723984.096912039
#Sta/Elev= 30
9084.218152.4645 9112.38147.91069159.457145.44489172.776140.96349328.115128.6066
9503.04799.719429633.99599.987379839.593 94.73759928.89596.216679951.09999.26974
9966.23395.102169984.40678.950329995.50875.07734 10006.6  75.73510017.6981.21889
10050.94107.846210062.04112.795610073.24113.791210208.58112.629910431.35118.0216
 10467.9122.186610480.16117.954210492.43122.014310566.04165.336910627.43176.0313
10659.98175.559210781.12203.507910846.31213.761210929.66219.946610979.05219.1098
#Mann= 3 , 0 , 0
9084.218  0.0595       09084.218  0.0595       010979.05  0.0595       0
#XS Ineff= 2 , 0
       09722.105        10080.07       0
Bank Sta=9084.218,10979.05
Exp/Cntr=0.3,0.1

Type RM Length L Ch R = 1 ,18634.46,245.134700,245.134700,245.134700
XS GIS Cut Line= 6
579534.122037965 725425.26498719579204.919256341724984.741774841
579032.914132289724550.522887443578934.547286475724384.172686247
578656.026821043724030.491644106578331.561931542723672.537030425
#Sta/Elev= 30
9151.044215.99759195.025191.42529255.502144.99299270.621141.69829451.016123.5802
9475.892132.46569488.075147.27259500.258154.36989514.895151.92859549.908127.6656
9567.606121.66979586.252100.5597 9596.8198.13862 9690.3696.831129735.918 88.1046
9789.99998.985879932.09198.88308 9973.9887.780929984.45376.5797210005.3773.78492
10022.9483.4880910047.12108.556710233.11107.317310562.39116.5964 10753.2112.0912
10784.42115.565710954.68159.950511175.21166.869811252.35157.611611297.22175.5881
#Mann= 3 , 0 , 0
9151.044   0.061       09151.044   0.061       011297.22   0.061       0
#XS Ineff= 2 , 0
       09699.587        10088.22       0
Bank Sta=9151.044,11297.22
Exp/Cntr=0.3,0.1

Type RM Length L Ch R = 1 ,18389.32,245.134800,245.134800,245.134800
XS GIS Cut Line= 6
579797.242139422725086.567731455579411.714459406724694.670433594
579273.214892699724579.254083642579229.495951948724537.404878558
578599.879865242 723829.04859901578355.167224165723571.678052829
#Sta/Elev= 30
9315.371176.29389417.802168.74259458.155170.46129486.025165.86549518.312169.4048
9532.671167.18069590.105  134.249690.615109.94879708.98796.942449928.13794.96279
9939.16293.52892 9970.7578.804799992.72773.1684610030.6677.2450710084.62103.3453
10142.23106.4955 10285.2103.889410364.86 106.70110391.41112.186210488.73108.9776
10534.34112.084910643.65109.707510971.51114.450511001.39110.629511045.84116.8269
11148.43148.832111221.31143.992911265.04149.020811320.56167.376411409.01185.4933
#Mann= 3 , 0 , 0
9315.371  0.0754       09315.371  0.0754       011409.01  0.0754       0
#XS Ineff= 2 , 0
       0                10149.57       0
Bank Sta=9315.371,11409.01
Exp/Cntr=0.3,0.1

Type RM Length L Ch R = 1 ,18144.19,245.134700,245.134700,245.134700
XS GIS Cut Line= 6
579989.556930347724823.475957807 579695.25381669724566.438455471
579546.740832574724461.940225227579304.158165668724319.857790709
579153.089043727724204.883080153 578388.08837613723431.014948943
#Sta/Elev= 30
9287.225167.36929306.888 170.173 9344.46162.63069433.713156.1074 9601.04155.4206
9639.719137.17779665.506121.16549680.491108.5949 9728.1390.077189765.43793.47048
9954.63494.333969966.09992.693029989.02973.01483 10000.571.1405610011.9971.40252
10023.4877.6487610046.4599.5246110093.12102.931510263.53100.453510674.74110.8902
10792.98107.195210821.93  110.7410896.29113.0063 11010.1110.025311096.83111.4322
11111.13113.200411139.72129.436611182.62147.930611314.15 161.24511419.27191.7305
#Mann= 3 , 0 , 0
9287.225  0.0588       09287.225  0.0588       011419.27  0.0588       0
#XS Ineff= 2 , 0
       0                10119.12       0
Bank Sta=9287.225,11419.27
Exp/Cntr=0.3,0.1