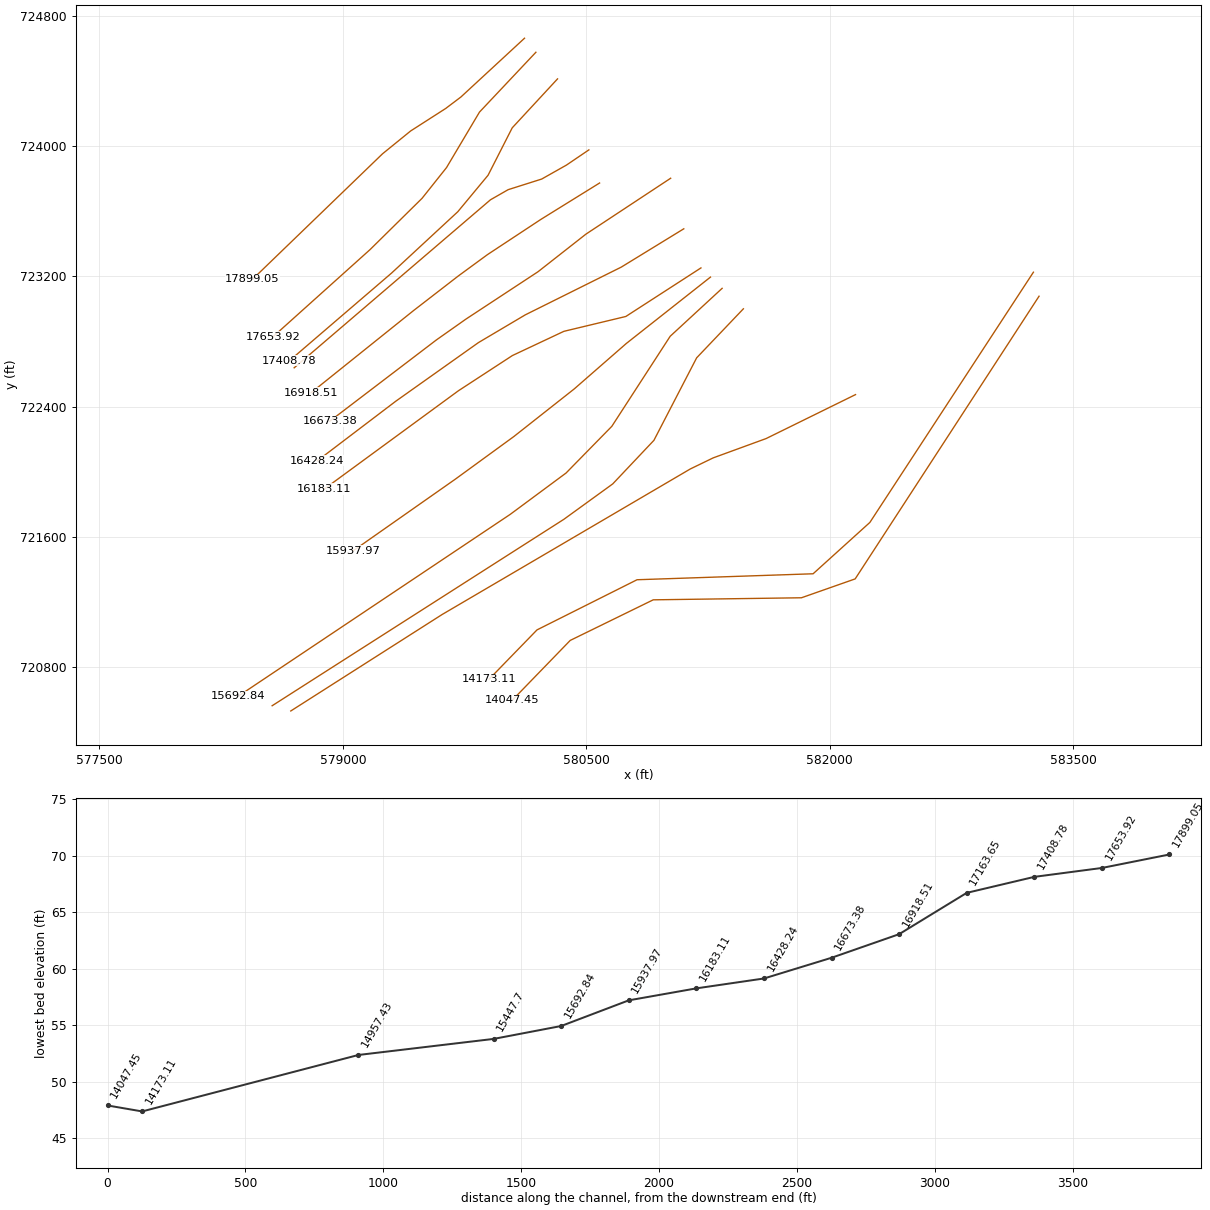
HEC-RAS study 2300_ras.prj: 2300

--- 2300_ras.g01 (geometry) --- (continued)

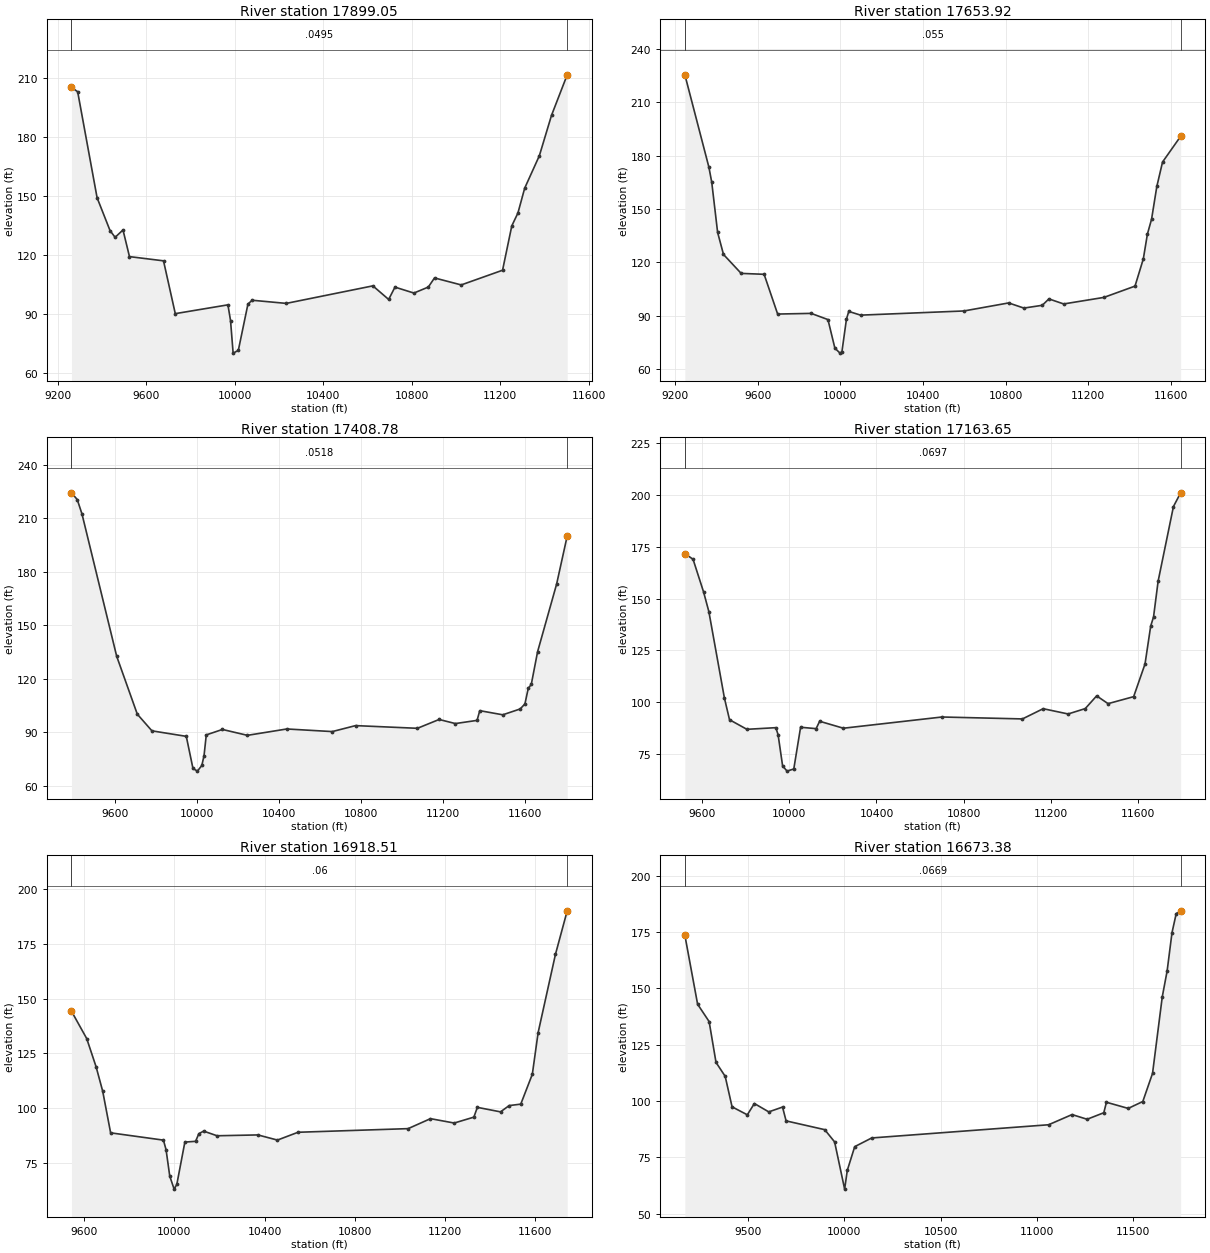
Type RM Length L Ch R = 1 ,17899.05,245.134800,245.134800,245.134800
XS GIS Cut Line= 6
580119.229384642724664.132687703579727.195866336724302.935795544
579632.955263194724232.057744185579417.492945264724094.199539886
579243.887891258723953.558768972578443.364730179723182.905203485
#Sta/Elev= 30
9261.079205.31039289.198203.0445 9377.03149.12849435.584132.43329458.476129.0137
9494.139 132.7499523.416119.19449677.349  117.059730.57690.188629968.61394.66633
9980.38886.693249992.16370.10581 10015.671.4782310059.0795.0329710077.8797.00536
10232.4495.40353   10624104.318110695.4197.4091410723.94103.676910809.53100.6637
10874.71103.710710902.75108.351911023.52104.795211210.42112.266311252.17134.8205
11279.99141.401611310.48154.003911376.79170.502311431.78191.041211502.76211.6569
#Mann= 3 , 0 , 0
9261.079  0.0495       09261.079  0.0495       011502.76  0.0495       0
#XS Ineff= 2 , 0
       0                10101.52       0
Bank Sta=9261.079,11502.76
Exp/Cntr=0.3,0.1

Type RM Length L Ch R = 1 ,17653.92,245.134700,245.134700,245.134700
XS GIS Cut Line= 6
580189.343263834724577.975802255579841.714829467724210.241102219
579638.504319523  723869.0561071579487.962970598 723680.43531907
 579167.48699906723365.249477521578569.092742694722829.296800166
#Sta/Elev= 30
9248.198225.39519364.423173.47549378.205165.0033 9406.63136.79659435.054124.3977
9520.579113.74629631.654113.23329697.08390.886779859.11891.25683 9940.5287.77526
9974.09971.69532    999968.9116610007.6969.3558410030.0388.01293 10041.292.36311
10098.4190.26921 10598.792.6215110814.97 97.135110888.5594.2448610977.4695.79809
11009.6899.39572 11081.296.5644311275.94100.246811426.33106.589611466.53121.8836
11486.35135.852311506.46144.224911531.96 162.66411559.57 176.36311647.06190.8051
#Mann= 3 , 0 , 0
9248.198   0.055       09248.198   0.055       011647.06   0.055       0
#XS Ineff= 2 , 0
       0                10086.66       0
Bank Sta=9248.198,11647.06
Exp/Cntr=0.3,0.1

Type RM Length L Ch R = 1 ,17408.78,245.134800,245.134800,245.134800
XS GIS Cut Line= 6
580322.611556704724414.213916952580043.433384784724113.418617744
579894.592227177723822.153100695579707.934888294723597.730370599
579299.745508722723220.687881632578670.176441485722681.769239761
#Sta/Elev= 30
  9389.2224.25029417.437220.48159440.528212.37839609.582132.57199710.048100.0857
9781.35190.722329948.80387.631829981.36669.6184410003.04 68.123410024.5971.29529
10035.3676.8420810046.2388.4436910124.9191.5019810246.5988.1999510438.7191.77233
10660.1190.3075810773.8693.6605611075.1792.1486511180.8797.1019411260.1594.80846
11365.8696.5922611378.99102.043611491.0799.7222511575.92102.9965 11599.1105.8329
 11615.3114.553711629.97116.726511660.84135.135411753.44173.017211805.14200.0405
#Mann= 3 , 0 , 0
  9389.2  0.0518       0  9389.2  0.0518       011805.14  0.0518       0
#XS Ineff= 2 , 0
       0                10138.53       0
Bank Sta=9389.2,11805.14
Exp/Cntr=0.3,0.1

Type RM Length L Ch R = 1 ,17163.65,245.134800,245.134800,245.134800
XS GIS Cut Line= 6
580515.822050115 723977.97231455 580377.44381184723884.395896519
 580225.00509926723798.658091502580018.225623818723733.390359018
579909.238628222723671.097843442578699.716299484722638.657014571
#Sta/Elev= 30
9520.588171.74249558.203168.94639606.686153.10339630.656143.71389702.175101.9275
9725.51991.520469805.24786.888259938.01887.683849948.45184.305349969.23769.20336
9989.79366.7076710020.5667.7641910051.7287.8835710123.0787.2132210139.1890.77464
10248.2487.4164910700.7292.8324911070.1191.90664 11165.296.8383911279.7394.29679
11358.3496.8903511410.75103.032711463.0999.2754111580.52102.653111632.71118.4217
 11658.8  136.7311671.85141.133811692.88158.395511763.18194.412111796.17201.0388
#Mann= 3 , 0 , 0
9520.588  0.0697       09520.588  0.0697       011796.17  0.0697       0
#XS Ineff= 2 , 0
       09852.173        10142.52       0
Bank Sta=9520.588,11796.17
Exp/Cntr=0.3,0.1

Type RM Length L Ch R = 1 ,16918.51,245.134700,245.134700,245.134700
XS GIS Cut Line= 6
580581.775397799723774.377197705580220.645025637723551.132975715
579890.385005825723333.909727653579711.508548685723203.211706667
579434.328217328722989.556196235578804.453060992722485.797957227
#Sta/Elev= 30
9543.957144.30799611.652131.7862 9653.32118.87579682.513107.7441 9717.6388.75132
9951.74885.423499963.45481.03381 9979.7768.993439999.18163.0507210011.0965.20052
10046.7784.5267910094.3484.8770410108.8688.3775910130.0289.5363210189.4887.41634
10370.5587.7981310457.2485.4450610548.48 89.012611036.6590.6707511135.7895.22484
11240.96 93.228511328.0895.9215711343.58100.3877 11446.298.3305311484.68101.2008
11535.99101.8533 11587.3115.498911612.95134.495511689.92170.298811741.93  190.12
#Mann= 3 , 0 , 0
9543.957    0.06       09543.957    0.06       011741.93    0.06       0
#XS Ineff= 2 , 0
       09903.045        10113.91       0
Bank Sta=9543.957,11741.93
Exp/Cntr=0.3,0.1

Type RM Length L Ch R = 1 ,16673.38,245.134800,245.134800,245.134800
XS GIS Cut Line= 6
581019.743463594723803.653914254580497.463768381723459.999113323
580202.436720599723229.065812953579757.462617384722937.420652958
579575.844105547722809.736470443578919.550929463722310.882868961
#Sta/Elev= 30
9170.209173.58429236.453142.99539296.368135.30049332.162117.19079379.886111.0055
 9415.6897.471919495.002 93.93439531.66998.943619606.57895.235559678.16497.37013
9696.67191.238159897.64587.341969949.02581.9115910001.1960.9626910014.9969.28846
10053.58  79.80610142.0383.6646811061.9189.5173711183.9394.0387511262.3591.95745
11349.1594.8530111362.8499.5039611476.1196.7724611552.0399.8368511602.65112.3172
11653.27146.285111678.57157.772611703.88174.7429 11725.7183.173711748.74184.4322
#Mann= 3 , 0 , 0
9170.209  0.0669       09170.209  0.0669       011748.74  0.0669       0
#XS Ineff= 2 , 0
       09881.866        10139.17       0
Bank Sta=9170.209,11748.74
Exp/Cntr=0.3,0.1

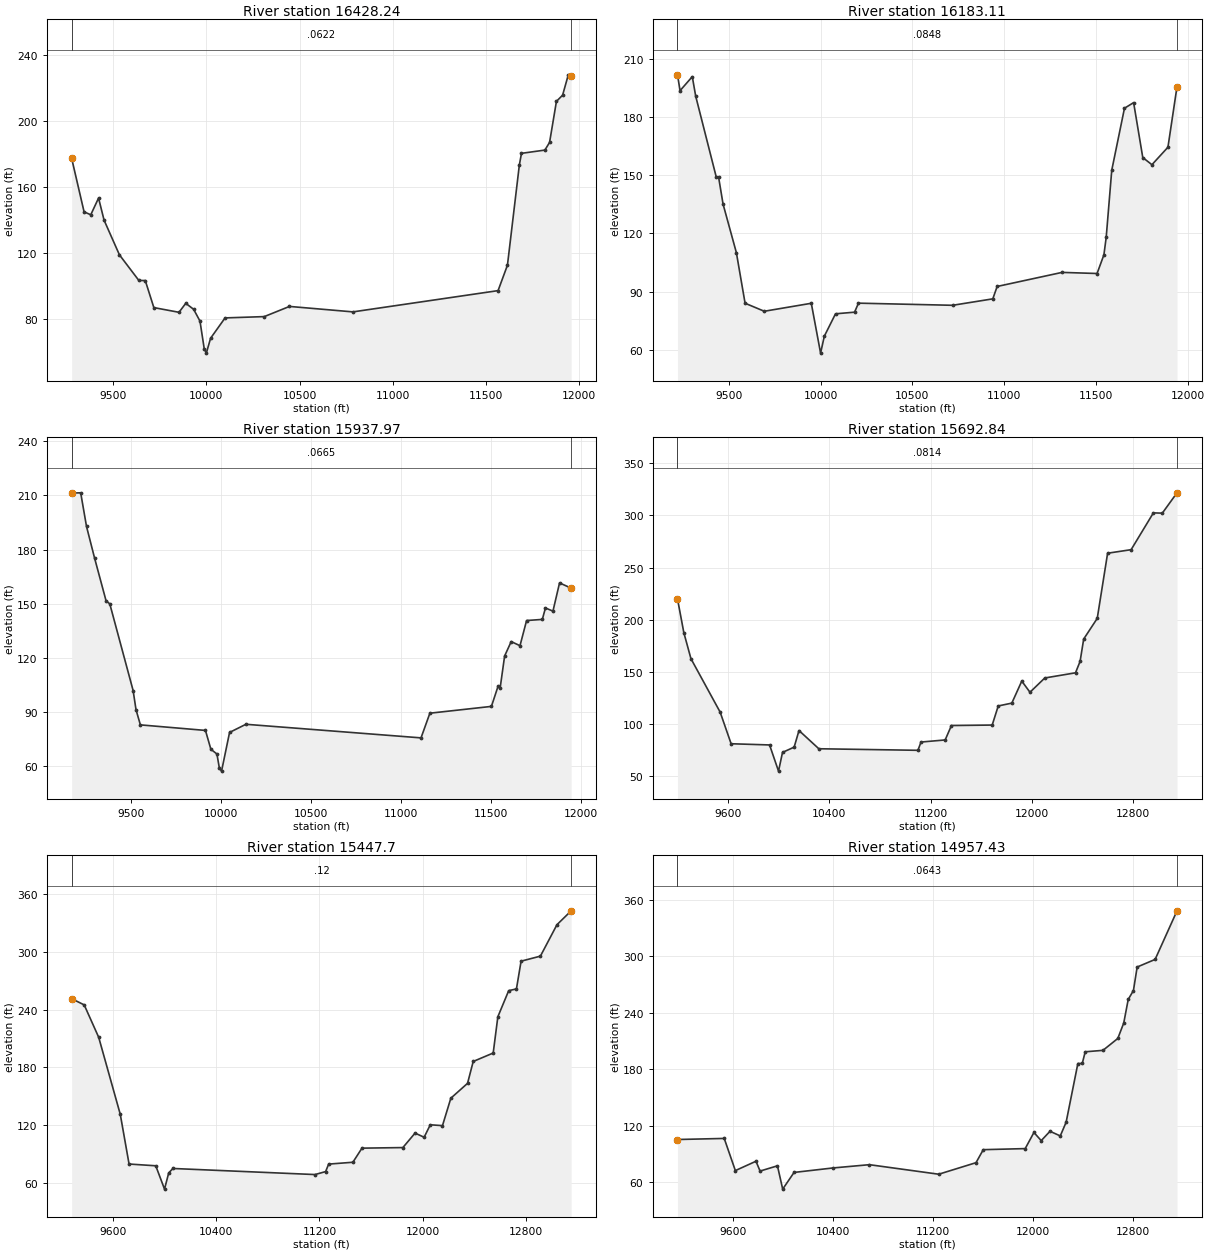
Type RM Length L Ch R = 1 ,16428.24,245.134700,245.134700,245.134700
XS GIS Cut Line= 6
581100.638933086723492.873765239580715.410726059723257.458605453
580124.331769847722964.290020127 579835.37665434722793.638087684
579325.345055794722432.939840789 578842.76862923722067.341357178
#Sta/Elev= 30
9278.547177.18029345.152144.73339381.066142.93119422.795153.06129452.361139.6893
 9534.68118.67349638.781103.15489673.237103.09179719.17886.712339854.02283.86099
9890.23189.306999932.52985.665349966.44478.530379989.16261.8418410000.55 59.1292
10023.2768.1411910100.9680.4633510310.9881.2552610446.2887.4187310786.3184.11521
11564.3196.9913111614.49112.387911678.39173.170211689.77180.160311815.23182.1357
11840.32 186.78811877.11211.654911910.23215.406211940.68 227.72111956.03226.8531
#Mann= 3 , 0 , 0
9278.547  0.0622       09278.547  0.0622       011956.03  0.0622       0
#XS Ineff= 2 , 0
       0 9932.23        10162.62       0
Bank Sta=9278.547,11956.03
Exp/Cntr=0.3,0.1

Type RM Length L Ch R = 1 ,16183.11,245.134800,245.134800,245.134800
XS GIS Cut Line= 6
581206.370595719723252.462286989580743.580743377 722954.10506792
 580361.68813129722862.745802751580044.659154653722714.035834166
579711.735495476722497.487112156578885.389156124721893.814926203
#Sta/Elev= 30
9222.041 201.7369236.114193.59019302.585 200.7959321.174  190.719433.189148.9434
 9445.46149.07589470.004135.06769542.348110.07019589.71283.979739694.12679.84133
9949.868 83.955510000.4358.2549710020.6466.9646710081.5878.5253710185.2579.36961
10206.4784.0173910718.6382.9155910937.1486.2384910960.7892.6227811313.9399.87834
11504.25  99.30711541.48 108.94111553.89117.904811584.12152.550511653.29184.5103
11703.07187.411911752.85159.099711802.63155.397211889.74164.409111939.04195.6121
#Mann= 3 , 0 , 0
9222.041  0.0848       09222.041  0.0848       011939.04  0.0848       0
#XS Ineff= 2 , 0
       09919.605        10136.22       0
Bank Sta=9222.041,11939.04
Exp/Cntr=0.3,0.1

Type RM Length L Ch R = 1 ,15937.97,245.134800,245.134800,245.134800
XS GIS Cut Line= 6
581265.078352952723196.071941226580747.025682166 722788.59020574
 580425.24329506722508.571475467580053.249649148722216.085980086
579693.356203418721954.654839298579062.124035758721513.201207467
#Sta/Elev= 30
9170.618211.31619220.877211.42579253.227192.77249297.945175.27639361.559151.6736
9382.628 149.8329512.029101.85989528.20491.20143  9552.482.827419913.80179.75218
9943.817 69.33439977.47266.680699991.00758.8837110003.1557.1950310047.6578.63549
10138.4183.1544111110.95 75.620511160.1389.3013611501.92 93.067711538.53104.1673
11550.73103.532311575.17120.982511611.75128.993711660.56126.699411697.17  140.65
11784.55141.2763   11802147.6142 11843.6145.857111880.21 161.49511944.73 158.601
#Mann= 3 , 0 , 0
9170.618  0.0665       09170.618  0.0665       011944.73  0.0665       0
#XS Ineff= 2 , 0
       09850.996        10120.29       0
Bank Sta=9170.618,11944.73
Exp/Cntr=0.3,0.1

Type RM Length L Ch R = 1 ,15692.84,245.134700,245.134700,245.134700
XS GIS Cut Line= 6
581336.969623808723127.018483693581016.833180785722832.398613151
580657.287884532 722279.11017731580375.204695811721992.039558872
580031.667474663721738.328772909578353.109288143720619.042274109
#Sta/Elev= 30
9201.016220.04429251.331187.61329307.277 162.7429537.961111.49599624.58781.16916
9928.31880.02042    999954.9236110030.5172.8733510122.4377.9296410160.7193.84152
10317.35 76.374311099.9874.8793111124.3982.8132511315.0984.81251 11364.698.63339
11686.5599.0909211734.25117.402811841.57120.130511920.16141.243911984.82130.5478
12101.98144.220912344.48149.1793 12380.7160.111312409.08181.545612516.16201.3624
12598.02263.832912783.67 267.22312959.63302.518513030.02302.238413146.08321.7275
#Mann= 3 , 0 , 0
9201.016  0.0814       09201.016  0.0814       013146.08  0.0814       0
#XS Ineff= 2 , 0
       09851.587        10110.64       0
Bank Sta=9201.016,13146.08
Exp/Cntr=0.3,0.1

Type RM Length L Ch R = 1 , 15447.7,490.269500,490.269500,490.269500
XS GIS Cut Line= 6
  581467.9248181723001.232573386581179.970577846722699.980238624
580916.651466196722192.936827327580662.883721574721925.185047333
580361.765301724721707.637166489578563.949305986720561.839919307
#Sta/Elev= 30
9283.009251.2188 9380.17244.78479492.201211.23679659.333131.29419727.24279.80336
9933.73777.9790410001.5553.7809710033.8770.55943 10066.375.1864411165.4368.88832
11247.9271.9627211271.3579.7256211458.8181.6456311529.1196.2656611845.4896.85994
11939.77111.8686   12010107.564312057.64120.484412151.94119.611912216.64148.0501
12345.88163.470612389.72186.139912544.37194.891212580.28232.467712664.19259.5455
12724.12261.362412760.08290.113612909.57295.340813037.59327.933113147.46342.3132
#Mann= 3 , 0 , 0
9283.009    0.12       09283.009    0.12       013147.46    0.12       0
#XS Ineff= 2 , 0
       09872.653        10135.37       0
Bank Sta=9283.009,13147.46
Exp/Cntr=0.3,0.1

Type RM Length L Ch R = 1 ,14957.43,784.320900,784.320900,784.320900
XS GIS Cut Line= 6
582158.932515153722473.934751233 581608.36973849722203.926102721
581282.066782044722085.161500356581140.764555922 722016.94164155
579611.027923078721122.251610879578678.838491915720529.647524745
#Sta/Elev= 30
9155.872105.10459529.718106.25079618.68972.058569783.67382.013749816.24471.55673
9955.28477.136499997.26652.3599910088.0670.1124110400.1374.8729810690.6578.34543
11245.0868.2066311543.32 80.481511601.3394.3048911936.66 95.441912006.44112.5799
12064.74103.920412135.08113.863812217.15108.916712264.04123.522512357.83185.8867
   12393185.960112416.63198.3607 12558.5199.894312677.22 212.53512724.78228.9774
12760.44253.974912802.24263.517212831.99288.467312975.66 296.56313150.66348.2204
#Mann= 3 , 0 , 0
9155.872  0.0643       09155.872  0.0643       013150.66  0.0643       0
#XS Ineff= 2 , 0
       09887.309        10236.18       0
Bank Sta=9155.872,13150.66
Exp/Cntr=0.3,0.1

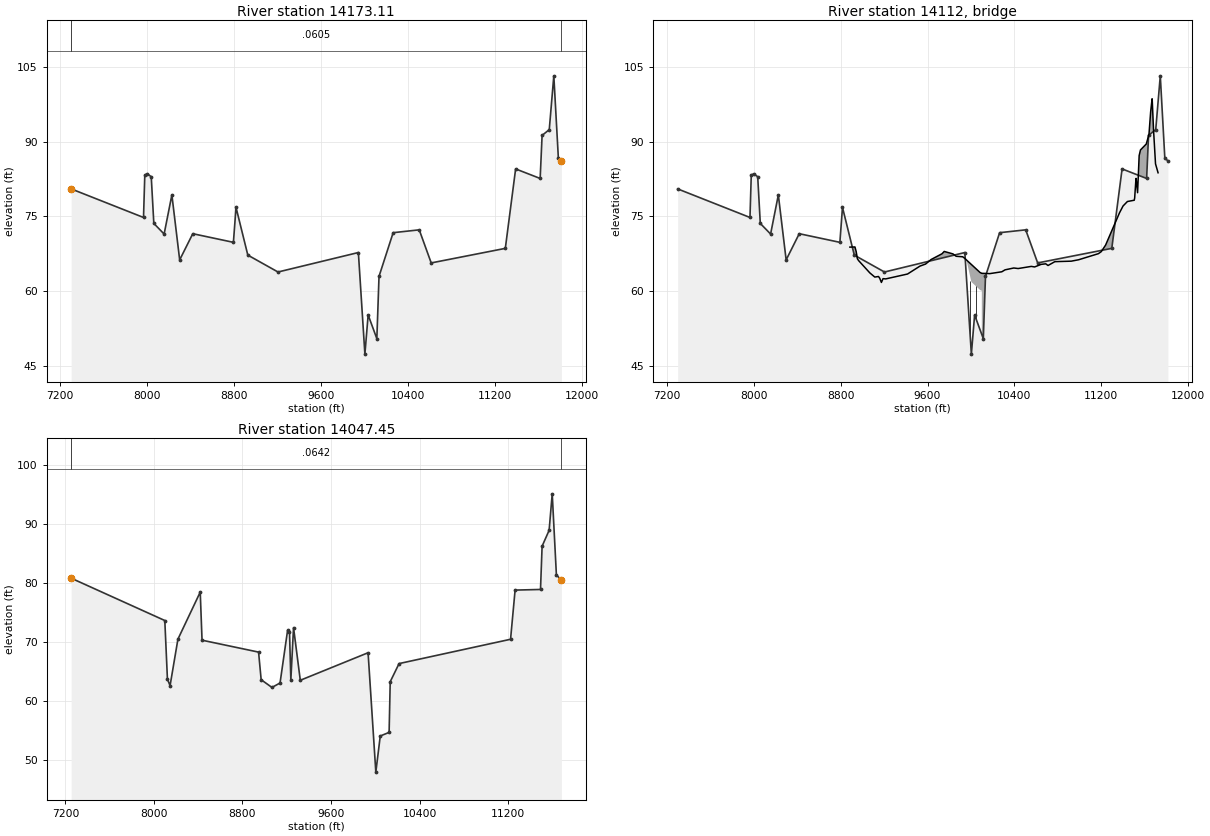
Type RM Length L Ch R = 1 ,14173.11,125.658800,125.658800,125.658800
XS GIS Cut Line= 6
583255.231056035723226.204688862 582247.44863078721688.396213412
581897.570695102721372.819141492580812.587195843721336.155861169
580196.166579425 721027.94555296579900.906284243720724.915249929
#Sta/Elev= 30
 7300.3180.522987966.05674.788067977.91983.305848001.64583.556078037.23382.95695
8060.959 73.59558155.82471.460498227.03879.319348298.87466.274818419.48771.53189
8793.38569.798738817.50876.805938926.05967.234359203.85863.843669943.52967.75333
10003.5347.3629810033.5355.2235410113.5350.4707810133.5462.9678410263.6271.73672
10503.7372.3060310613.7865.6667611295.97 68.587111390.8284.5329811616.6582.61627
11634.4291.2596111700.4392.4188511742.31103.2153 11784.286.6752711812.2486.16706
#Mann= 3 , 0 , 0
 7300.31  0.0605       0 7300.31  0.0605       011812.24  0.0605       0
#XS Ineff= 2 , 0
       09882.731        10224.33       0
Bank Sta=7300.31,11812.24
Exp/Cntr=0.3,0.1

Type RM Length L Ch R = 3 ,   14112,,,
BEGIN DESCRIPTION:
END DESCRIPTION:
Bridge Culvert--1,0,-1,-1, 0
Deck Dist Width WeirC Skew NumUp NumDn MinLoCord MaxHiCord MaxSubmerge Is_Ogee
34.329400,57.000000,2.6,0, 60, 60, , , 0.95, 0, 0,0,,
 8885.54 8932.09 8943.40 8954.71 8966.02 9068.92 9114.61 9149.00 9160.29 9175.52
 9190.75 9215.29 9416.08 9531.44 9582.14 9632.84 9733.73 9753.73 9833.74 9863.74
 9923.74 9939.77 9939.7710083.7510099.7710099.7710173.7610283.7610313.7610394.01
10434.3410555.3510585.6010646.1010688.0410709.0310771.9810922.9010990.3211172.15
11198.9011239.0211367.1211399.5211439.6411502.6511506.5211517.7111519.8911533.27
11547.8311560.0211613.5211638.1811653.6411667.0111668.3011680.3911698.4211721.86
   68.84   68.87   67.95   66.49   66.13   63.67   62.83   62.94   62.58   61.75
   62.51   62.46   63.44   65.04   65.44   66.35   67.51   67.97   67.48   67.00
   66.90   66.64   66.64   63.74   63.58   63.58   63.52   63.89   64.28   64.65
   64.54   64.97   64.86   65.38   65.49   65.15   65.92   66.02   66.30   67.52
   67.93   69.25   75.73   77.09   77.99   78.25   78.69   82.32   82.63   79.76
   87.21   88.34   89.54   91.46   96.01   98.61   98.28   92.30   85.55   83.76
 -931.16 -931.13 -932.05 -933.51 -933.87 -936.33 -937.17 -937.06 -937.42 -938.25
 -937.49 -937.54 -936.56 -934.96 -934.56 -933.65 -932.49 -932.03 -932.52 -933.00
 -933.10 -933.36   63.14   60.24   60.08 -936.42 -936.48 -936.11 -935.72 -935.35
 -935.46 -935.03 -935.14 -934.62 -934.51 -934.85 -934.08 -933.98 -933.70 -932.48
 -932.07 -930.75 -924.27 -922.91 -922.01 -921.75 -921.31 -917.68 -917.37 -920.24
 -912.79 -911.66 -910.46 -908.54 -903.99 -901.39 -901.72 -907.70 -914.45 -916.24
 8885.54 8932.09 8943.40 8954.71 8966.02 9068.92 9114.61 9149.00 9175.52 9190.75
 9215.29 9416.08 9531.44 9582.14 9632.84 9733.73 9753.73 9833.74 9863.74 9923.74
 9942.72 9942.7210003.7510043.7510083.7510102.7210102.7210153.7610283.7610313.76
10394.0110434.3410555.3510585.6010688.0410709.0310771.9810922.9010990.3211172.15
11198.9011239.0211367.1211399.5211439.6411502.6511506.5211517.7111519.8911533.27
11547.8311560.0211613.5211638.1811653.6411667.0111668.3011680.3911698.4211721.86
   68.84   68.87   67.95   66.49   66.13   63.67   62.83   62.94   61.75   62.51
   62.46   63.44   65.04   65.44   66.35   67.51   67.97   67.48   67.00   66.90
   66.57   66.57   65.29   64.72   63.74   63.57   63.57   63.47   63.89   64.28
   64.65   64.54   64.97   64.86   65.49   65.15   65.92   66.02   66.30   67.52
   67.93   69.25   75.73   77.09   77.99   78.25   78.69   82.32   82.63   79.76
   87.21   88.34   89.54   91.46   96.01   98.61   98.28   92.30   85.55   83.76
 -931.16 -931.13 -932.05 -933.51 -933.87 -936.33 -937.17 -937.06 -938.25 -937.49
 -937.54 -936.56 -934.96 -934.56 -933.65 -932.49 -932.03 -932.52 -933.00 -933.10
 -933.43   63.07   61.79   61.22   60.24   60.07 -936.43 -936.53 -936.11 -935.72
 -935.35 -935.46 -935.03 -935.14 -934.51 -934.85 -934.08 -933.98 -933.70 -932.48
 -932.07 -930.75 -924.27 -922.91 -922.01 -921.75 -921.31 -917.68 -917.37 -920.24
 -912.79 -911.66 -910.46 -908.54 -903.99 -901.39 -901.72 -907.70 -914.45 -916.24
Pier Skew, UpSta & Num, DnSta & Num=  ,9992.44, 2 ,9995.38, 2 , 0 , 0 , 0 ,,
    4.00    4.00
 -934.47   65.53
    4.00    4.00
 -934.53   65.47
Pier Skew, UpSta & Num, DnSta & Num=  ,10047.11, 2 ,10050.05, 2 , 0 , 0 , 0 ,,
    4.00    4.00
 -935.39   64.61
    4.00    4.00
 -935.48   64.52
BR Coef=-1 , 0 , 0 ,, 0 ,,,0.8,0,1,0,
WSPro=,,,, 1 ,,,, 0 ,,,, 0 ,,,,-1 ,-1 ,-1 , 0 , 0 , 0 , 0 , 0
BC Design=,, 0 ,, 0 ,,,,,,

Type RM Length L Ch R = 1 ,14047.45,567.149500,567.149500,567.149500
XS GIS Cut Line= 6
583289.953278244723078.635244429582156.798540145721341.335866347
581825.771978855  721225.3366189580912.309264898721212.727879509
580400.776784033720963.195488185580043.356426626720595.415120423
#Sta/Elev= 30
7252.37280.817828098.33673.630818122.04563.687838145.75362.563278216.87970.46647
8418.40278.45777 8434.7670.290358945.56768.267988968.84563.580879066.39162.26853
 9139.5563.024779207.72171.963999224.90371.758929237.09663.542969261.48372.42215
9322.449 63.48489934.96168.1618710004.9747.8904310044.98 54.0233   1012554.64018
   1013563.2419710215.0266.32059 11222.270.4467411263.3278.7949611492.8978.90501
11507.2486.2509411570.8188.95008 11598.795.1420311636.3881.3869211681.7880.45628
#Mann= 3 , 0 , 0
7252.372  0.0642       07252.372  0.0642       011681.78  0.0642       0
#XS Ineff= 2 , 0
       09885.768        10225.04       0
Bank Sta=7252.372,11681.78
Exp/Cntr=0.3,0.1