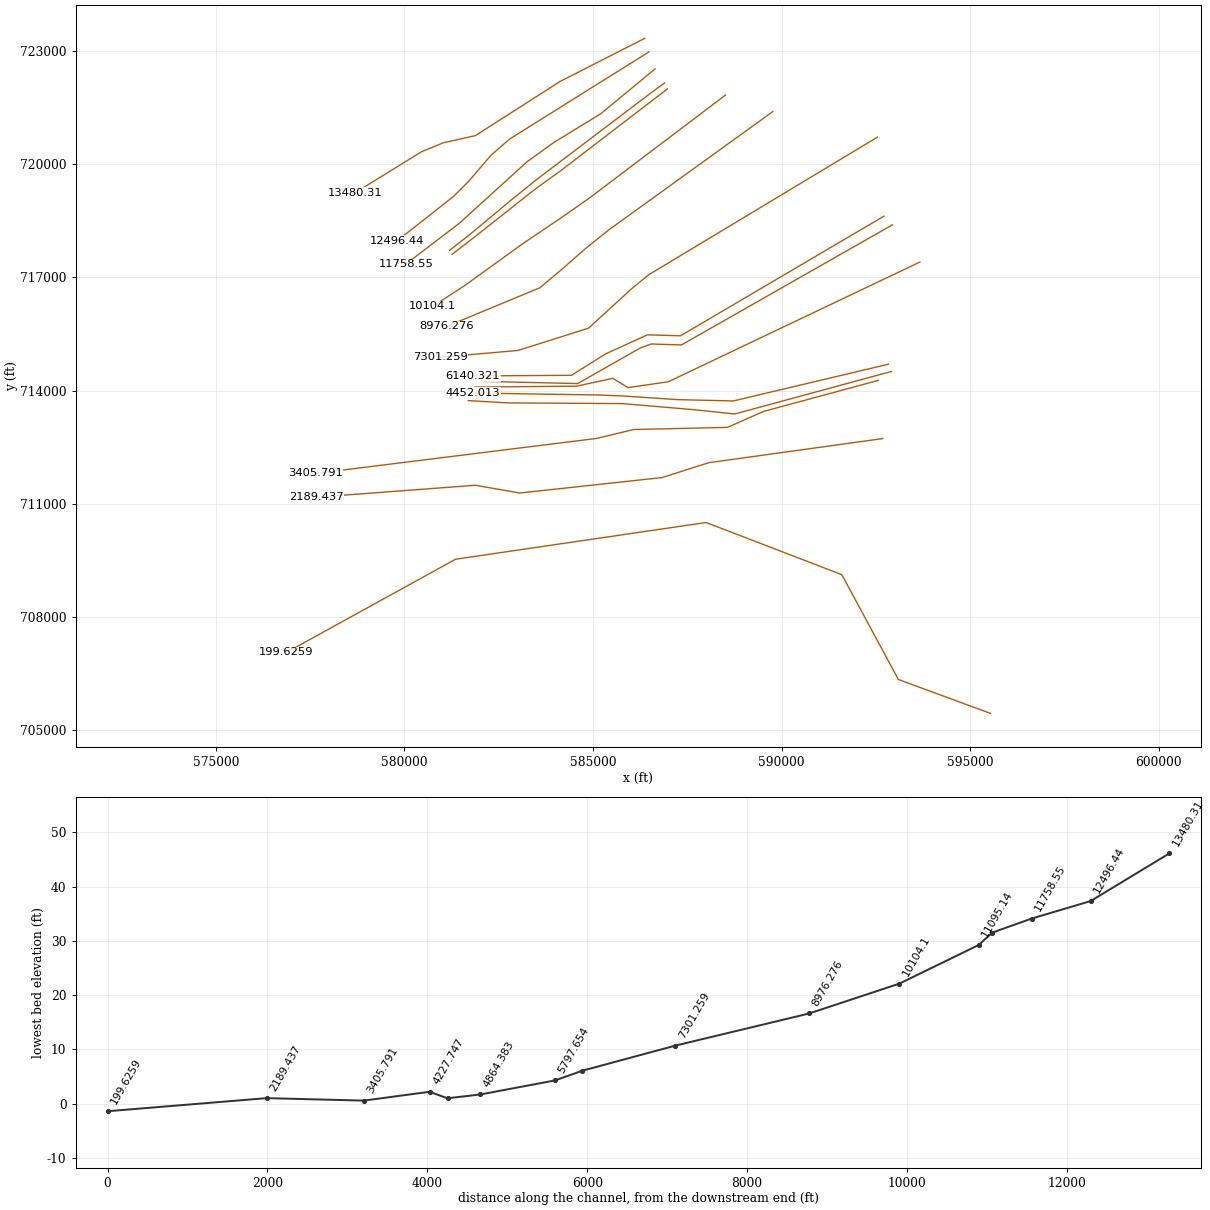
HEC-RAS study 2300_ras.prj: 2300

--- 2300_ras.g01 (geometry) --- (continued)

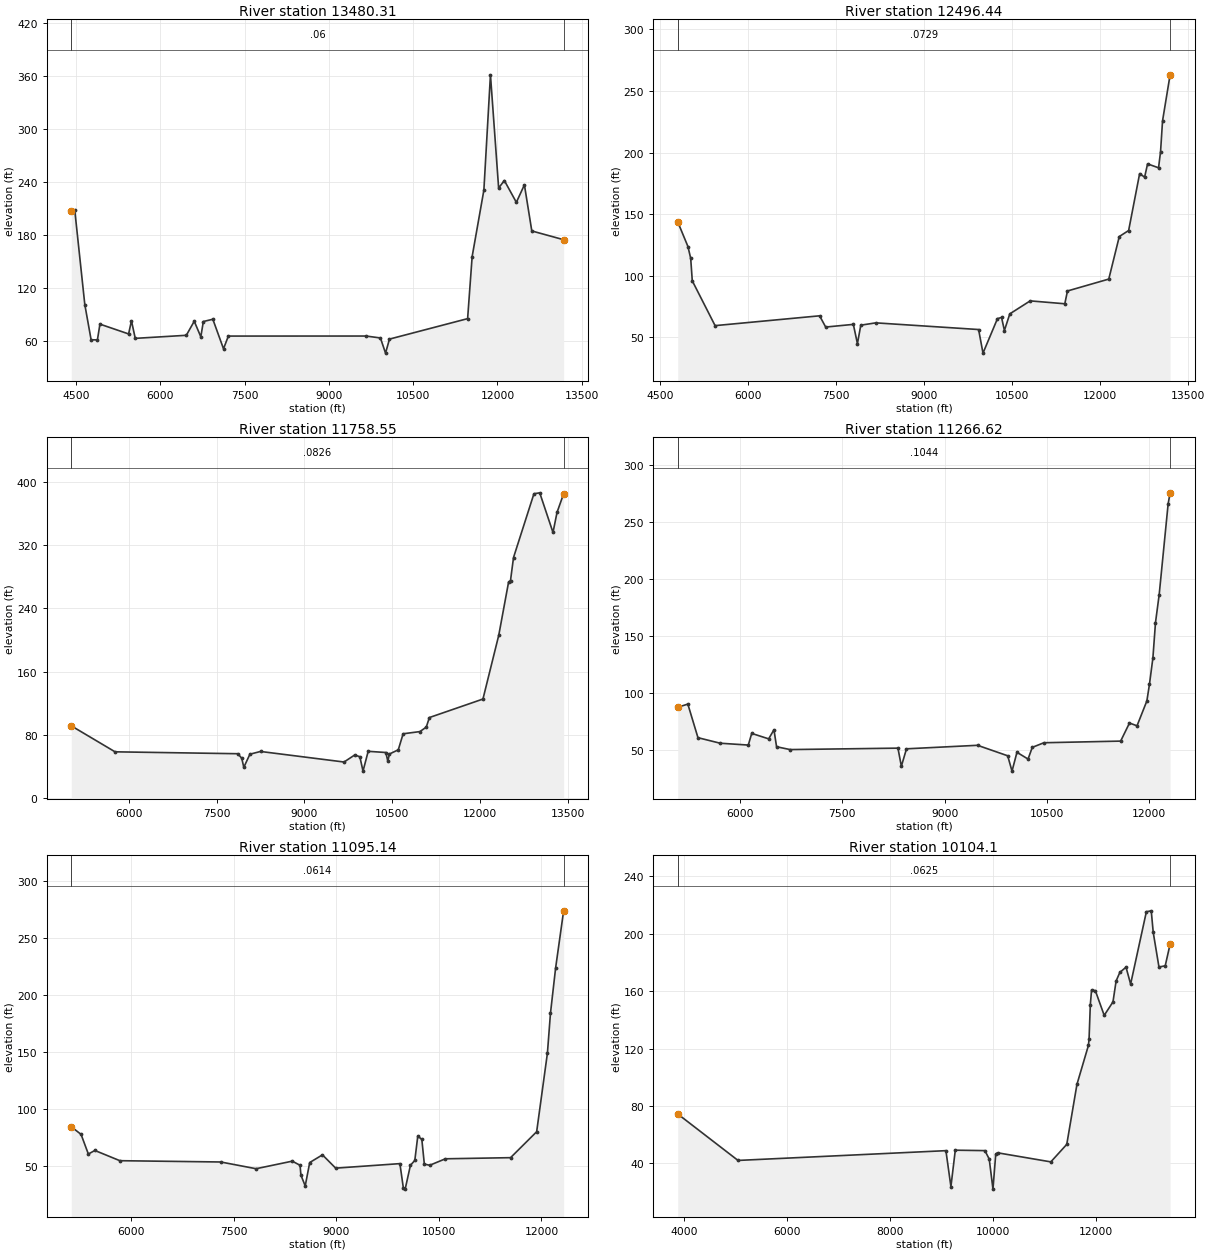
Type RM Length L Ch R = 1 ,13480.31,983.861300,983.861300,983.861300
XS GIS Cut Line= 6
586369.472502291 723337.72592473584134.173663884722199.829567268
581879.608480483720758.061921313581034.313850224720570.229964539
580456.743662119720334.442993075578683.738317251719241.104643777
#Sta/Elev= 30
4415.481207.39874476.605208.25344656.143101.05274768.35561.191194880.56661.07761
4925.45178.902935435.46667.824135486.508 82.70385553.83562.806226462.74766.27234
6603.74282.182226720.83364.557946765.71881.85748 6934.6384.440697124.54851.01485
7211.12965.394089661.16665.438359917.39163.2562210008.0446.0977610078.5361.97979
11468.9185.1226511549.54155.341311758.23230.494511875.34360.989612020.83232.9024
12122.64241.401912336.34216.7037 12479.6 236.51612611.17184.3346 13177.6174.4293
#Mann= 3 , 0 , 0
4415.481    0.06       04415.481    0.06       0 13177.6    0.06       0
#XS Ineff= 2 , 0
       09824.057        10170.44       0
Bank Sta=4415.481,13177.6
Exp/Cntr=0.3,0.1

Type RM Length L Ch R = 1 ,12496.44,737.895900,737.895900,737.895900
XS GIS Cut Line= 6
586480.893579721722978.702453032582788.368989944720669.032536417
582289.743126452720235.030058682581706.725534379 719553.42631039
581297.941048801719145.187257454579805.421491742717969.611906007
#Sta/Elev= 30
 4796.36143.77464969.923123.80975017.203114.18025044.01495.975725433.00659.62706
7215.01967.592097318.61358.474157790.51760.643487859.82745.006677917.58660.00097
8173.65261.876479926.07156.46236   1000137.3239810247.7565.2966710317.4966.26491
10366.0255.67664   1045869.1642110805.6679.7080911395.7677.3561111441.3187.73661
12145.5697.3831612324.76131.8911 12484.2136.772912671.85182.9534 12756.7180.0398
 12807.1190.817112994.23187.648613028.22200.572813062.37225.7175 13191.1263.0544
#Mann= 3 , 0 , 0
 4796.36  0.0729       0 4796.36  0.0729       0 13191.1  0.0729       0
#XS Ineff= 2 , 0
       09668.686        10273.03       0
Bank Sta=4796.36,13191.1
Exp/Cntr=0.3,0.1

Type RM Length L Ch R = 1 ,11758.55,491.930600,491.930600,491.930600
XS GIS Cut Line= 6
586641.835135996722526.828083441585199.896169364721336.069011986
 583952.03783989720572.116439894583243.210553795 720061.13630335
581462.267632812718442.032484725580032.441348433717349.820098549
#Sta/Elev= 30
5014.63991.326645762.73758.497427860.97556.098457928.20850.35564 7963.54  38.902
8067.51555.480328249.13458.948429676.53845.611229859.88754.537469946.99252.23866
   1000134.0971910089.3359.1413810390.9657.6406910424.8446.72175 10452.655.74239
10603.9661.0523510686.5281.3003210973.8684.0781111081.9289.7190411135.67101.8332
12050.82125.202712321.16205.866112488.91273.032512521.77274.931812573.45304.1004
12922.36384.679813021.44385.8453 13248.1335.747413317.23361.150513429.87384.6751
#Mann= 3 , 0 , 0
5014.639  0.0826       05014.639  0.0826       013429.87  0.0826       0
#XS Ineff= 2 , 0
       0 9523.82        10165.23       0
Bank Sta=5014.639,13429.87
Exp/Cntr=0.3,0.1

Type RM Length L Ch R = 1 ,11266.62,171.476100,171.476100,171.476100
XS GIS Cut Line= 6
586894.469723046722155.082305074586549.626871854721902.978424445
583480.606326789719577.493390277582853.238457501719071.854953051
581714.733094424718123.283853278581194.879189521717717.523606241
#Sta/Elev= 30
5084.508 87.41865232.49990.230115381.14760.80509 5706.9855.963416119.79754.33855
 6169.9964.547386418.80859.783146496.24467.754726534.68752.870996733.33750.38904
8315.73851.653898365.93135.78395 8441.2251.063649483.90654.136959926.19844.95832
9989.67331.5196510062.2347.9991410225.1742.0894510287.1952.3311610457.74 56.3779
11583.9357.8157311713.43 73.637411824.1871.2091811968.73 93.007112006.75 107.612
12057.17130.668812094.99161.517512149.32 186.09712280.73265.578512309.43275.2368
#Mann= 3 , 0 , 0
5084.508  0.1044       05084.508  0.1044       012309.43  0.1044       0
#XS Ineff= 2 , 0
       09828.482        10188.73       0
Bank Sta=5084.508,12309.43
Exp/Cntr=0.3,0.1

Type RM Length L Ch R = 1 ,11095.14,991.042900,991.042900,991.042900
XS GIS Cut Line= 6
586968.557961196721996.839217156584140.890422523719827.352562666
583568.792514056719415.989993721583328.079772741719233.463888273
581888.332883596 718094.61770618581261.307596862717611.842049122
#Sta/Elev= 30
5126.18284.132175269.31277.367035375.62460.111265470.97963.24399  5836.554.24134
7311.18753.106147827.95847.178658357.33353.844618470.77150.186278483.37541.51984
8546.23432.048958611.94652.62467 8798.1959.378748991.41547.685239930.41451.66302
9981.73329.9128410007.3929.2254910084.33 50.176710148.4354.4833810191.7875.84112
10250.9972.9964910287.6751.2496310366.3850.2277810595.5455.9124411548.3156.90689
11929.8279.7217712087.06148.887312131.39183.786612206.98223.812512324.07274.0771
#Mann= 3 , 0 , 0
5126.182  0.0614       05126.182  0.0614       012324.07  0.0614       0
#XS Ineff= 2 , 0
       09838.611        10189.22       0
Bank Sta=5126.182,12324.07
Exp/Cntr=0.3,0.1

Type RM Length L Ch R = 1 , 10104.1,1127.822200,1127.822200,1127.822200
XS GIS Cut Line= 6
588510.115362138 721834.67318584584919.110815209719117.429658678
 584194.70082048718608.276423636583142.647387632717899.382244842
581604.615875129716789.283564865580744.353320056716230.987331941
#Sta/Elev= 30
3871.35774.44221 5044.0142.101229089.06948.903889186.53123.86152  9271.749.23424
9847.82648.932129931.972 43.045510004.6622.1170810058.4946.3786210093.8947.41834
11130.6841.0924811440.8153.2969411639.29 95.148111862.18122.190511874.46  126.61
11899.01150.541511923.57160.866611997.25160.262812169.17143.122412339.87152.4985
12400.72167.054112473.38 173.03212593.62 176.68212683.04164.900812989.57215.2964
13084.53215.917913123.02200.900813234.52176.794813356.35  177.6313451.19192.6864
#Mann= 3 , 0 , 0
3871.357  0.0625       03871.357  0.0625       013451.19  0.0625       0
#XS Ineff= 2 , 0
       09760.863        10099.94       0
Bank Sta=3871.357,13451.19
Exp/Cntr=0.3,0.1

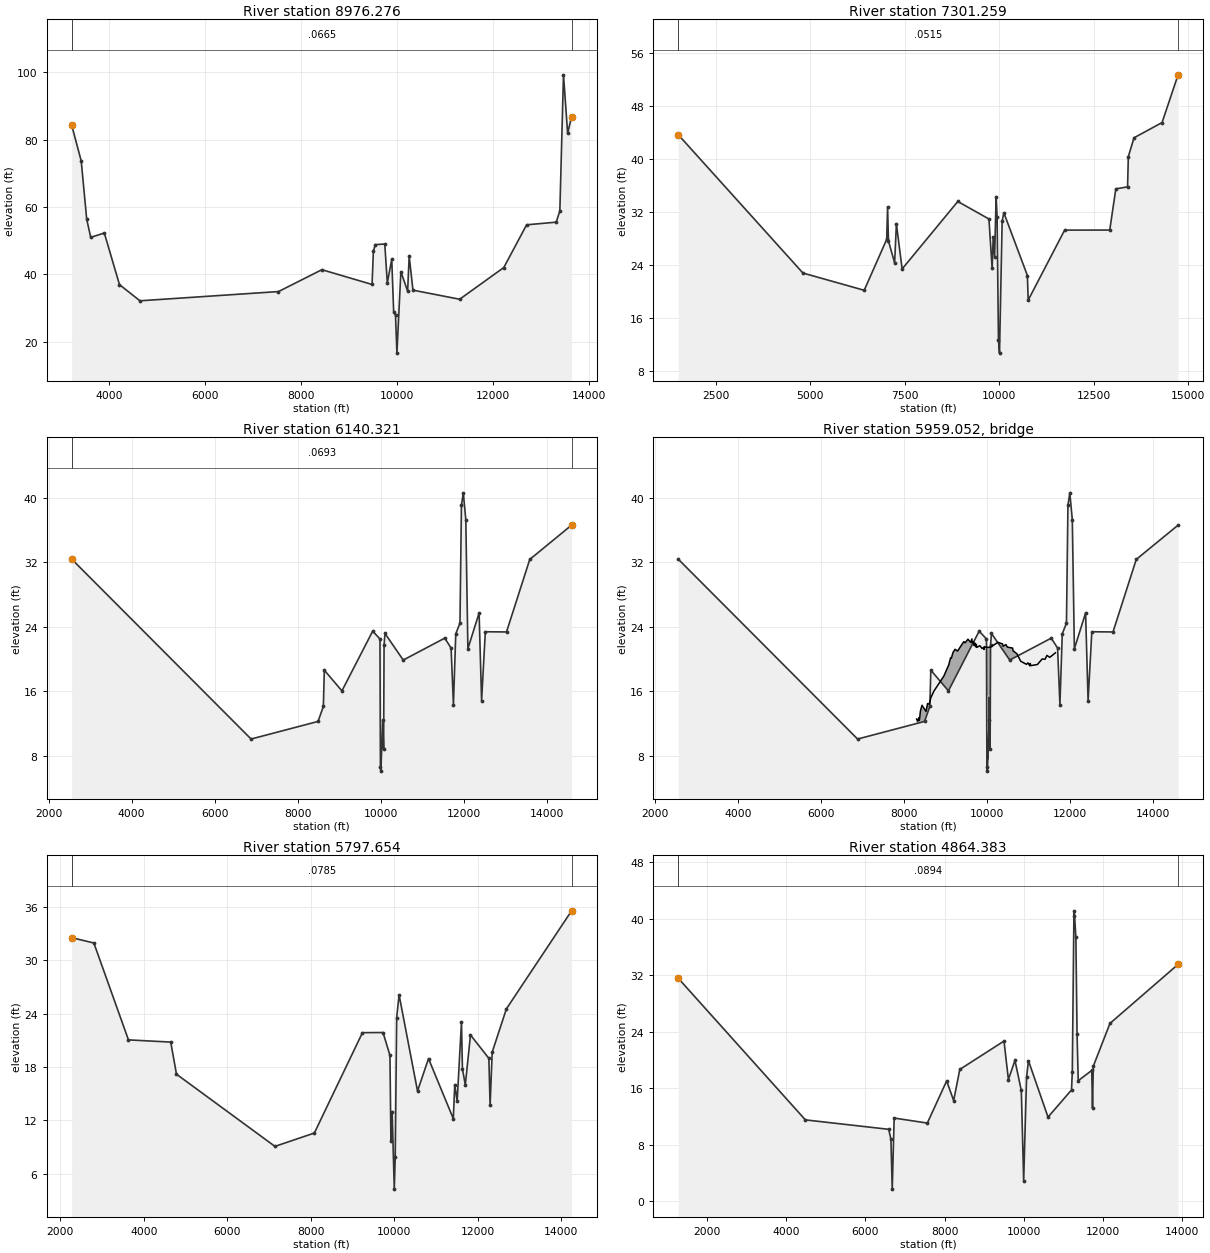
Type RM Length L Ch R = 1 ,8976.276,1675.017500,1675.017500,1675.017500
XS GIS Cut Line= 6
589767.205613729721398.171016756 585417.14614014718259.922003164
584833.176935394717794.522756421584152.029209513717198.537627522
583588.116302497 716725.03562638581119.202141461715701.556433413
#Sta/Elev= 30
3219.30684.345843419.31673.629323532.38356.442023616.60750.987923900.21352.28566
4216.06636.969794643.36832.157827531.92934.900178437.80941.393579483.76537.00199
9511.32346.894049550.70648.827769748.87549.02042 9801.7237.431339894.19844.47747
9934.31328.935119972.66527.8555810002.0216.6228810084.5540.8036510225.4435.00068
10257.6745.4159810336.7435.3193211310.5832.6205412230.7242.0328912707.0354.72061
13324.0655.5047413399.8458.8391713475.6199.2463313562.2281.9019813644.2786.86629
#Mann= 3 , 0 , 0
3219.306  0.0665       03219.306  0.0665       013644.27  0.0665       0
#XS Ineff= 2 , 0
       09783.893        10176.16       0
Bank Sta=3219.306,13644.27
Exp/Cntr=0.3,0.1

Type RM Length L Ch R = 1 ,7301.259,1160.938100,1160.938100,1160.938100
XS GIS Cut Line= 6
592535.723001003720717.051658064586485.851669967717077.362108767
586054.423754692716729.893944368584879.112924218715654.123427317
583007.776266038715062.979890719580953.378117889714883.399633005
#Sta/Elev= 30
1498.13943.672534801.655 22.78176423.81520.179417018.99627.866867042.33732.76115
7065.67727.61387 7229.0624.321177275.74130.203747427.45423.397198901.31333.58255
9725.684 30.93969810.40323.501399839.00128.19216 9876.36 25.23579916.06434.31764
9942.40631.251419977.51612.6685110005.5810.6970910075.3630.5992110120.7431.87572
 10743.922.4069510764.8718.6927611729.6929.2594112924.3529.2698713084.9635.48822
13396.14 35.785613416.2240.3605813566.7943.1916814309.6145.4953714732.8452.69444
#Mann= 3 , 0 , 0
1498.139  0.0515       01498.139  0.0515       014732.84  0.0515       0
#XS Ineff= 2 , 0
       09403.403        10987.98       0
Bank Sta=1498.139,14732.84
Exp/Cntr=0.3,0.1

Type RM Length L Ch R = 1 ,6140.321,342.666700,342.666700,342.666700
XS GIS Cut Line= 6
592709.334112138718622.867630288587317.714799106715451.651126087
586440.999167681715477.655403271 585326.59692511714969.983270556
584426.820299625714404.527317837581808.180144578714387.758121759
#Sta/Elev= 30
2556.24732.388926877.03610.067468489.646 12.25068617.26214.106358640.46518.60825
9064.16416.042819804.74723.449349980.30722.483429991.2796.56836810002.256.085551
10046.1412.4324310068.098.77149210079.06 21.7371   1010123.16706 10540.7 19.8627
11540.8922.5840811692.9521.3504411749.3314.3414511805.7123.1143111907.0324.44775
11942.4639.0538111987.5640.6081612047.5637.2703312097.5621.2700812367.5725.70828
12427.5714.8377612517.57 23.375413027.5823.3488413587.5932.3478114594.4336.59801
#Mann= 3 , 0 , 0
2556.247  0.0693       02556.247  0.0693       014594.43  0.0693       0
#XS Ineff= 2 , 0
       08928.016        11769.51       0
Bank Sta=2556.247,14594.43
Exp/Cntr=0.3,0.1

Type RM Length L Ch R = 3 ,5959.052,,,
BEGIN DESCRIPTION:
END DESCRIPTION:
Bridge Culvert--1,0,-1,-1, 0
Deck Dist Width WeirC Skew NumUp NumDn MinLoCord MaxHiCord MaxSubmerge Is_Ogee
113.833350,115.000000,2.6,0, 60, 60, , , 0.95, 0, 0,0,,
 8297.46 8325.38 8348.73 8360.41 8369.74 8389.11 8427.85 8523.87 8563.45 8602.19
 8640.63 8714.48 8954.52 9074.54 9114.55 9134.56 9174.57 9224.58 9284.59 9434.62
 9464.63 9534.65 9600.52 9629.48 9640.11 9672.02 9682.65 9703.92 9718.01 9735.83
 9747.39 9821.14 9875.66 9910.59 9920.38 9932.95 9980.53 9980.5310078.5310078.53
10255.7910367.6010380.1610448.8510483.3210609.7110621.1910713.1110805.0210942.90
10977.3711023.3211034.8111046.3011207.1511322.0511390.9811436.9411505.8811640.65
   12.54   12.28   12.70   12.39   12.57   13.51   14.26   13.49   14.47   14.38
   15.19   16.01   17.88   19.30   20.13   20.09   20.80   21.20   20.98   22.15
   22.00   22.45   22.05   22.49   21.97   22.13   21.67   21.96   21.51   21.81
   21.43   21.64   21.30   21.44   21.18   21.53   21.43   21.43   21.47   21.47
   22.06   21.87   21.58   21.78   21.47   21.35   21.01   20.65   19.72   19.33
   19.52   19.16   19.44   19.17   19.31   20.00   19.96   20.44   20.20   20.76
 -987.46 -987.72 -987.30 -987.61 -987.43 -986.49 -985.74 -986.51 -985.53 -985.62
 -984.81 -983.99 -982.12 -980.70 -979.87 -979.91 -979.20 -978.80 -979.02 -977.85
 -978.00 -977.55 -977.95 -977.51 -978.03 -977.87 -978.33 -978.04 -978.49 -978.19
 -978.57 -978.36 -978.70 -978.56 -978.82 -978.47 -978.57   15.43   15.47 -978.53
 -977.94 -978.13 -978.42 -978.22 -978.53 -978.65 -978.99 -979.35 -980.28 -980.67
 -980.48 -980.84 -980.56 -980.83 -980.69 -980.00 -980.04 -979.56 -979.80 -979.24
 8297.46 8325.38 8348.73 8360.41 8369.74 8389.11 8427.85 8505.34 8523.87 8563.45
 8602.19 8640.63 8684.48 8714.48 8954.52 9074.54 9114.55 9134.56 9174.57 9224.58
 9284.59 9434.62 9464.63 9534.65 9600.52 9629.48 9640.11 9672.02 9682.65 9703.92
 9718.01 9735.83 9747.39 9821.14 9925.79 9925.79 9932.9510023.7910023.7910121.63
10255.7910367.6010380.1610448.8510483.3210609.7110621.1910713.1110805.0210942.90
10977.3711023.3211034.8111046.3011207.1511322.0511390.9811436.9411505.8811640.65
   12.54   12.28   12.70   12.39   12.57   13.51   14.26   13.44   13.49   14.47
   14.38   15.19   15.47   16.01   17.88   19.30   20.13   20.09   20.80   21.20
   20.98   22.15   22.00   22.45   22.05   22.49   21.97   22.13   21.67   21.96
   21.51   21.81   21.43   21.64   21.31   21.31   21.53   21.45   21.45   21.46
   22.06   21.87   21.58   21.78   21.47   21.35   21.01   20.65   19.72   19.33
   19.52   19.16   19.44   19.17   19.31   20.00   19.96   20.44   20.20   20.76
 -987.46 -987.72 -987.30 -987.61 -987.43 -986.49 -985.74 -986.56 -986.51 -985.53
 -985.62 -984.81 -984.53 -983.99 -982.12 -980.70 -979.87 -979.91 -979.20 -978.80
 -979.02 -977.85 -978.00 -977.55 -977.95 -977.51 -978.03 -977.87 -978.33 -978.04
 -978.49 -978.19 -978.57 -978.36 -978.69   15.31   15.53   15.45 -978.55 -978.54
 -977.94 -978.13 -978.42 -978.22 -978.53 -978.65 -978.99 -979.35 -980.28 -980.67
 -980.48 -980.84 -980.56 -980.83 -980.69 -980.00 -980.04 -979.56 -979.80 -979.24
Pier Skew, UpSta & Num, DnSta & Num=  ,10012.70, 2 ,9957.95, 2 , 0 , 0 , 0 ,,
    3.00    3.00
 -978.56   21.44
    3.00    3.00
 -978.58   21.42
Pier Skew, UpSta & Num, DnSta & Num=  ,10046.37, 2 ,9991.62, 2 , 0 , 0 , 0 ,,
    3.00    3.00
 -978.55   21.45
    3.00    3.00
 -978.57   21.43
BR Coef=-1 , 0 , 0 ,, 0 ,,,0.8,0,1,0,
WSPro=,,,, 1 ,,,, 0 ,,,, 0 ,,,,-1 ,-1 ,-1 , 0 , 0 , 0 , 0 , 0
BC Design=,, 0 ,, 0 ,,,,,,

Type RM Length L Ch R = 1 ,5797.654,933.271200,933.271200,933.271200
XS GIS Cut Line= 6
592937.198695451718395.003046945587342.881626666715209.906893119
586544.660027534715234.946957231586257.129271299715132.257401407
584589.654607147714185.566601753582073.958925962714244.093915567
#Sta/Elev= 30
2271.74632.516162803.607 31.91353632.12421.040884644.75720.794684782.84317.19104
7141.816 9.090628085.40610.587689237.88821.851559730.95521.868639896.63619.29945
9919.6499.6626439949.61312.9978210000.194.29322510023.217.93501810057.7223.55158
10115.2426.0937210557.1115.3049510820.5118.9346911414.5212.1980911449.02 16.0169
11506.5114.1731111609.9923.0265211632.9817.7829811701.9715.9871311825.7921.59746
12265.9118.9706712295.9213.6968212345.9319.6642712686.0324.5213514247.4935.52463
#Mann= 3 , 0 , 0
2271.746  0.0785       02271.746  0.0785       014247.49  0.0785       0
#XS Ineff= 2 , 0
       08664.506        11818.99       0
Bank Sta=2271.746,14247.49
Exp/Cntr=0.3,0.1

Type RM Length L Ch R = 1 ,4864.383,412.370100,412.370100,412.370100
XS GIS Cut Line= 6
593664.195223272717407.589852527586994.063679218714233.528158516
585924.150531352714078.804930151585522.684226692714324.156298012
584560.372960746714117.220840022581865.645827025714093.246499106
#Sta/Elev= 30
1275.86631.597874486.578 11.51966590.73210.180986646.1058.7638476679.3281.708126
6727.65711.776847565.28811.067258052.56617.036948229.758 14.25378384.80118.66966
9500.38822.682589611.53217.233479776.40719.949529937.28315.68238  9996.72.921149
 10069.617.5471810116.8119.9062510611.1911.9131511204.3215.7602311224.3218.29384
11264.3340.3718911274.3341.1369711314.3337.3616911344.3323.6171111374.3317.07343
11714.3418.5233911734.3413.1820711754.3519.1260212174.3625.1834413893.7833.54795
#Mann= 3 , 0 , 0
1275.866  0.0894       01275.866  0.0894       013893.78  0.0894       0
#XS Ineff= 2 , 0
       08877.569        11279.21       0
Bank Sta=1275.866,13893.78
Exp/Cntr=0.3,0.1

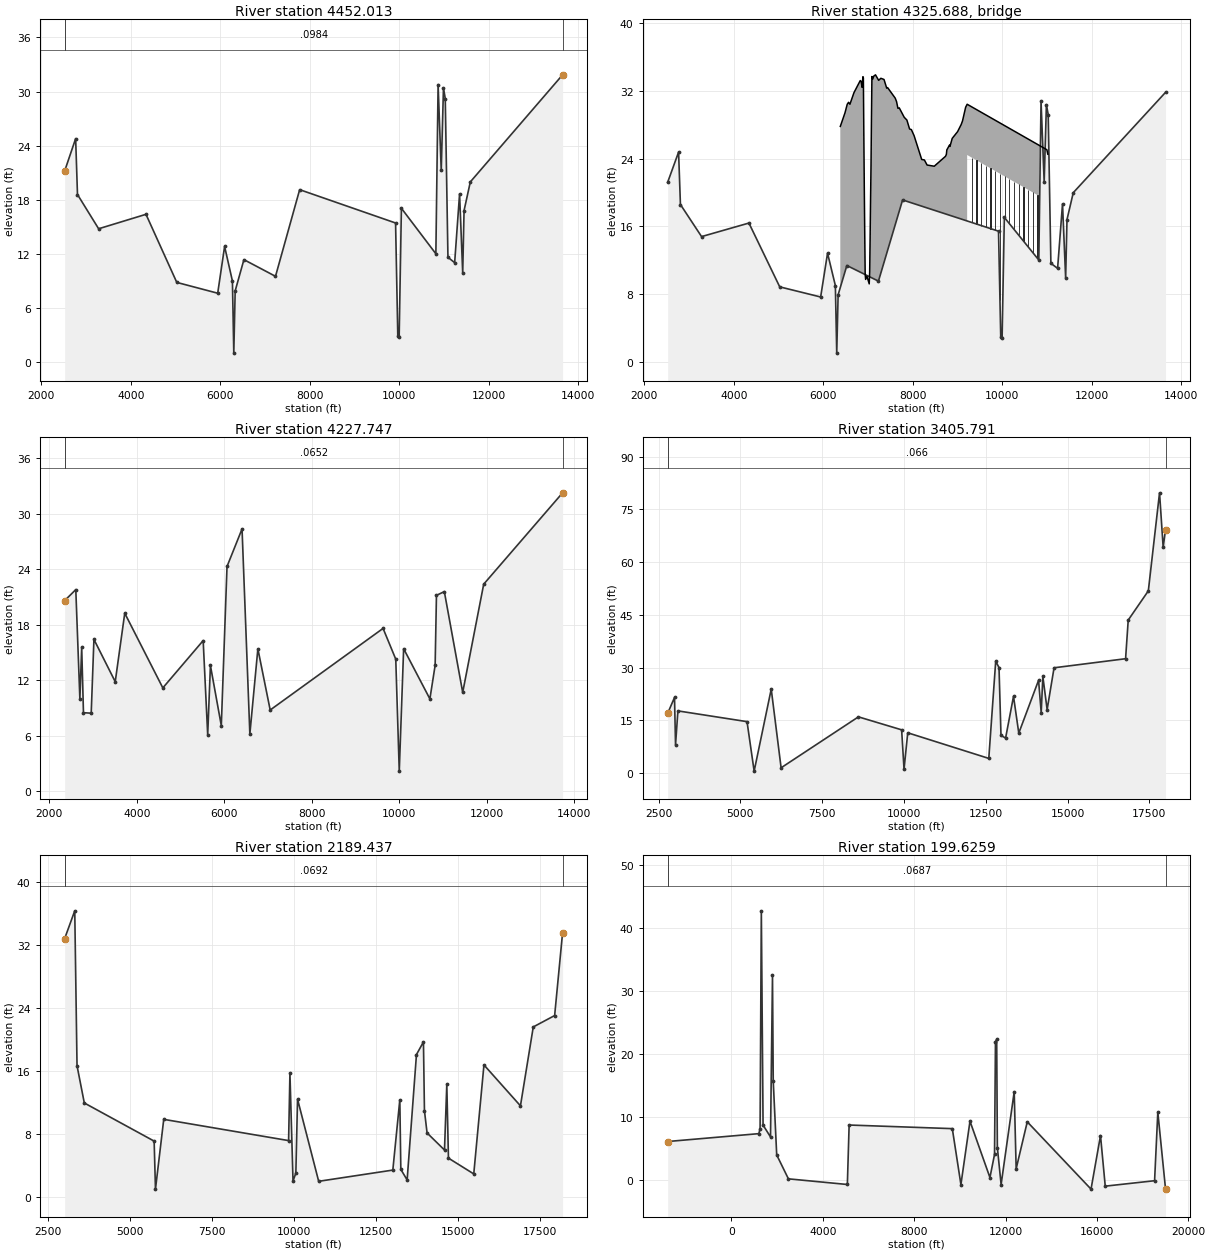
Type RM Length L Ch R = 1 ,4452.013,224.266400,224.266400,224.266400
XS GIS Cut Line= 6
592833.333015412714699.924254239588720.729855537713725.823027298
587250.549147934713759.112990946585787.238292187713857.299227342
585114.560103953713883.467486382581822.546565205713935.215872332
#Sta/Elev= 30
2521.15421.196272766.08124.779412807.18818.580973279.915 14.78534338.41316.38702
5026.9518.8392295941.5757.6415656095.72512.824956270.4298.9954536301.2591.001111
6332.089 7.897926527.34611.363727233.3999.5146237773.53719.119759917.44415.42486
9967.458 2.856899997.4662.74661610047.4817.0572310818.0412.0144210868.0530.76582
10938.0621.2469210988.0630.3933911028.0729.2139611088.0811.62519 11238.111.02707
11348.1118.6566911418.129.87376911448.1316.7953111588.1419.9782413650.8731.84815
#Mann= 3 , 0 , 0
2521.154  0.0984       02521.154  0.0984       013650.87  0.0984       0
#XS Ineff= 2 , 0
       09064.943        10953.01       0
Bank Sta=2521.154,13650.87
Exp/Cntr=0.3,0.1

Type RM Length L Ch R = 3 ,4325.688,,,
BEGIN DESCRIPTION:
END DESCRIPTION:
Bridge Culvert--1,0,-1,-1, 0
Deck Dist Width WeirC Skew NumUp NumDn MinLoCord MaxHiCord MaxSubmerge Is_Ogee
54.633200,115.000000,2.6,0, 60, 60, , , 0.95, 0, 0,0,,
 6381.14 6485.84 6535.86 6565.86 6595.90 6686.17 6826.60 6846.66 6866.72 6886.78
 6896.81 6906.84 6916.87 6926.90 6936.93 6946.96 6977.05 7027.21 7037.24 7047.27
 7057.30 7067.33 7077.36 7087.39 7107.45 7127.51 7167.63 7237.83 7287.96 7358.15
 7418.31 7438.37 7608.83 7638.91 7668.99 7699.07 7809.36 7869.52 7929.69 7969.79
 8029.95 8200.41 8260.57 8320.73 8481.17 8731.84 8751.89 8761.92 8822.08 8832.11
 8882.24 9002.56 9082.78 9112.83 9182.91 9216.50 9216.5010998.5010998.5011019.86
   27.82   29.43   30.44   30.67   30.44   31.81   33.24   33.15   32.45   33.70
   33.55   26.98   20.82   15.33   10.33    9.72   10.09    9.19   10.59   14.57
   19.10   23.21   28.72   33.72   33.43   33.76   33.92   33.27   33.51   33.37
   32.34   32.41   31.16   30.74   29.96   30.01   28.90   28.57   27.51   27.44
   26.73   23.91   23.85   23.25   23.11   24.28   24.51   25.04   25.61   25.45
   26.40   27.20   28.04   28.47   30.09   30.44   30.44   25.06   25.06   24.53
 -972.18 -970.57 -969.56 -969.33 -969.56 -968.19 -966.76 -966.85 -967.55 -966.30
 -966.45 -973.02 -979.18 -984.67 -989.67 -990.28 -989.91 -990.81 -989.41 -985.43
 -980.90 -976.79 -971.28 -966.28 -966.57 -966.24 -966.08 -966.73 -966.49 -966.63
 -967.66 -967.59 -968.84 -969.26 -970.04 -969.99 -971.10 -971.43 -972.49 -972.56
 -973.27 -976.09 -976.15 -976.75 -976.89 -975.72 -975.49 -974.96 -974.39 -974.55
 -973.60 -972.80 -971.96 -971.53 -969.91 -969.56   24.44   19.06 -974.94 -975.47
 6381.14 6535.86 6565.86 6595.90 6686.17 6826.60 6846.66 6866.72 6886.78 6896.81
 6906.84 6916.87 6926.90 6936.93 6946.96 6977.05 7027.21 7037.24 7047.27 7057.30
 7067.33 7077.36 7087.39 7107.45 7127.51 7167.63 7237.83 7287.96 7358.15 7418.31
 7438.37 7608.83 7638.91 7668.99 7699.07 7809.36 7869.52 7929.69 7969.79 8029.95
 8200.41 8260.57 8320.73 8481.17 8731.84 8751.89 8761.92 8822.08 8832.11 8882.24
 9002.56 9082.78 9112.83 9176.35 9176.35 9207.0210958.3510958.3510994.8911019.86
   27.82   30.44   30.67   30.44   31.81   33.24   33.15   32.45   33.70   33.55
   26.98   20.82   15.33   10.33    9.72   10.09    9.19   10.59   14.57   19.10
   23.21   28.72   33.72   33.43   33.76   33.92   33.27   33.51   33.37   32.34
   32.41   31.16   30.74   29.96   30.01   28.90   28.57   27.51   27.44   26.73
   23.91   23.85   23.25   23.11   24.28   24.51   25.04   25.61   25.45   26.40
   27.20   28.04   28.47   29.93   29.93   30.47   25.23   25.23   25.10   24.53
 -972.18 -969.56 -969.33 -969.56 -968.19 -966.76 -966.85 -967.55 -966.30 -966.45
 -973.02 -979.18 -984.67 -989.67 -990.28 -989.91 -990.81 -989.41 -985.43 -980.90
 -976.79 -971.28 -966.28 -966.57 -966.24 -966.08 -966.73 -966.49 -966.63 -967.66
 -967.59 -968.84 -969.26 -970.04 -969.99 -971.10 -971.43 -972.49 -972.56 -973.27
 -976.09 -976.15 -976.75 -976.89 -975.72 -975.49 -974.96 -974.39 -974.55 -973.60
 -972.80 -971.96 -971.53 -970.07   23.93   24.47   19.23 -974.77 -974.90 -975.47
Pier Skew, UpSta & Num, DnSta & Num=  ,9319.56, 2 ,9279.41, 2 , 0 , 0 , 0 ,,
    4.00    4.00
 -969.86   30.14
    4.00    4.00
 -969.74   30.26
Pier Skew, UpSta & Num, DnSta & Num=  ,9424.62, 2 ,9384.47, 2 , 0 , 0 , 0 ,,
    4.00    4.00
 -970.18   29.82
    4.00    4.00
 -970.06   29.94
Pier Skew, UpSta & Num, DnSta & Num=  ,9529.68, 2 ,9489.53, 2 , 0 , 0 , 0 ,,
    4.00    4.00
 -970.49   29.51
    4.00    4.00
 -970.37   29.63
Pier Skew, UpSta & Num, DnSta & Num=  ,9634.74, 2 ,9594.59, 2 , 0 , 0 , 0 ,,
    4.00    4.00
 -970.81   29.19
    4.00    4.00
 -970.69   29.31
Pier Skew, UpSta & Num, DnSta & Num=  ,9739.80, 2 ,9699.65, 2 , 0 , 0 , 0 ,,
    4.00    4.00
 -971.12   28.88
    4.00    4.00
 -971.00   29.00
Pier Skew, UpSta & Num, DnSta & Num=  ,9844.85, 2 ,9804.70, 2 , 0 , 0 , 0 ,,
    4.00    4.00
 -971.44   28.56
    4.00    4.00
 -971.32   28.68
Pier Skew, UpSta & Num, DnSta & Num=  ,9949.91, 2 ,9909.76, 2 , 0 , 0 , 0 ,,
    4.00    4.00
 -971.75   28.25
    4.00    4.00
 -971.63   28.37
Pier Skew, UpSta & Num, DnSta & Num=  ,10054.97, 2 ,10014.82, 2 , 0 , 0 , 0 ,,
    4.00    4.00
 -972.06   27.94
    4.00    4.00
 -971.94   28.06
Pier Skew, UpSta & Num, DnSta & Num=  ,10160.03, 2 ,10119.88, 2 , 0 , 0 , 0 ,,
    4.00    4.00
 -972.38   27.62
    4.00    4.00
 -972.26   27.74
Pier Skew, UpSta & Num, DnSta & Num=  ,10265.09, 2 ,10224.94, 2 , 0 , 0 , 0 ,,
    4.00    4.00
 -972.69   27.31
    4.00    4.00
 -972.57   27.43
Pier Skew, UpSta & Num, DnSta & Num=  ,10370.15, 2 ,10330.00, 2 , 0 , 0 , 0 ,,
    4.00    4.00
 -973.01   26.99
    4.00    4.00
 -972.89   27.11
Pier Skew, UpSta & Num, DnSta & Num=  ,10475.21, 2 ,10435.06, 2 , 0 , 0 , 0 ,,
    4.00    4.00
 -973.32   26.68
    4.00    4.00
 -973.20   26.80
Pier Skew, UpSta & Num, DnSta & Num=  ,10580.27, 2 ,10540.12, 2 , 0 , 0 , 0 ,,
    4.00    4.00
 -973.64   26.36
    4.00    4.00
 -973.52   26.48
Pier Skew, UpSta & Num, DnSta & Num=  ,10685.32, 2 ,10645.18, 2 , 0 , 0 , 0 ,,
    4.00    4.00
 -973.95   26.05
    4.00    4.00
 -973.83   26.17
Pier Skew, UpSta & Num, DnSta & Num=  ,10790.38, 2 ,10750.23, 2 , 0 , 0 , 0 ,,
    4.00    4.00
 -974.26   25.74
    4.00    4.00
 -974.14   25.86
Pier Skew, UpSta & Num, DnSta & Num=  ,10895.44, 2 ,10855.29, 2 , 0 , 0 , 0 ,,
    4.00    4.00
 -974.58   25.42
    4.00    4.00
 -974.46   25.54
BR Coef=-1 , 0 , 0 ,, 0 ,,,0.8,0,1,0,
WSPro=,,,, 1 ,,,, 0 ,,,, 0 ,,,,-1 ,-1 ,-1 , 0 , 0 , 0 , 0 , 0
BC Design=,, 0 ,, 0 ,,,,,,

Type RM Length L Ch R = 1 ,4227.747,821.955800,821.955800,821.955800
XS GIS Cut Line= 6
592910.094723046714507.512860641          588755 713379.17332828
587691.651532292 713491.69842428585771.382481247713654.946324304
582752.007075697 713672.97068882581693.248779625713734.085983709
#Sta/Elev= 30
2351.27220.626192605.24321.814892698.50210.009292739.95115.558082780.6048.509756
2957.5568.4592983019.72916.43314 3506.7511.860433724.35519.264554594.776 11.1917
5517.00816.30413 5620.636.1185595682.80313.612485931.4947.1160416062.23424.31213
 6405.6628.37055 6584.316.2071516767.45915.416297049.023 8.801429629.62517.62135
9919.71414.295169999.7152.19625210099.7215.42854 10699.910.0014810819.9413.63357
10849.9621.1946611030.0321.5995911450.0310.7037611930.03 22.400913733.5432.27378
#Mann= 3 , 0 , 0
2351.272  0.0652       02351.272  0.0652       013733.54  0.0652       0
#XS Ineff= 2 , 0
       09095.005        10942.41       0
Bank Sta=2351.272,13733.54
Exp/Cntr=0.3,0.1

Type RM Length L Ch R = 1 ,3405.791,1216.353800,1216.353800,1216.353800
XS GIS Cut Line= 6
592568.275084406714271.739158079589509.458789527713444.657418653
588563.784162313713024.357584313 586075.35767144712967.730295613
585088.519976169712730.705531657577633.028508663711802.937665045
#Sta/Elev= 30
2775.39916.964812985.97421.518113017.052 8.006333089.56617.695565202.82514.63782
5420.3660.5718695942.74923.878976244.407 1.518038608.136  15.9999929.11812.30909
10002.541.12273110115.9611.4679812593.65 4.1866712805.2731.8213412906.0430.00572
 12966.510.7266913107.589.97209713349.4321.8320613510.67 11.3733 14115.326.38787
14195.9117.21825 14246.327.47696 14377.318.0647214588.9229.9491516775.6632.52646
16856.2843.5134617470.9851.81692 17813.679.6859117924.4564.2275217996.9869.25079
#Mann= 3 , 0 , 0
2775.399   0.066       02775.399   0.066       017996.98   0.066       0
#XS Ineff= 2 , 0
       08816.422        11174.71       0
Bank Sta=2775.399,17996.98
Exp/Cntr=0.3,0.1

Type RM Length L Ch R = 1 ,2189.437,1989.811000,1989.811000,1989.811000
XS GIS Cut Line= 6
592677.888260394712727.125260472588069.993592352 712088.97410208
586828.700426072711693.970204011583053.859996438711284.291463196
          581880          711490577663.001680613711172.670488119
#Sta/Elev= 30
3010.57232.781513317.64836.290823387.01916.662893609.23311.942785739.2577.110541
5779.6391.0268046032.0259.8679239840.4557.1766179881.03815.717339975.0892.067121
10061.393.04422210112.9112.4255710757.972.01751813019.613.44053313232.8112.35049
13263.273.53199613456.172.18958613740.43 18.078313953.6319.68053 13983.910.96644
14064.138.14446414595.63 5.9812814665.8314.2897314715.974.95475915488.142.954463
15799.0216.7646516912.1611.5803417303.2621.57845 17955.1 23.020818197.7833.53691
#Mann= 3 , 0 , 0
3010.572  0.0692       03010.572  0.0692       018197.78  0.0692       0
#XS Ineff= 2 , 0
       0 8318.77        11308.48       0
Bank Sta=3010.572,18197.78
Exp/Cntr=0.3,0.1

Type RM Length L Ch R = 1 ,199.6259,0.000000,0.000000,0.000000
XS GIS Cut Line= 6
595534.710110992705442.596819639593092.012102753706341.180193096
591594.419526488709118.837932333587997.343561947710502.736399844
 581355.22980693709529.497416645576868.319451153707057.740587726
#Sta/Elev= 30
-2789.63 6.15549 1203.337.4026151257.6018.1915791311.87142.692681387.8498.756078
 1713.476.8811481800.30232.491521832.86415.75273 1984.824.0294362497.0760.244625
5077.369-0.650715154.8668.7677819671.2118.19600710047.93-0.6561710444.949.371887
11318.270.450218 11519.24.11231411559.4721.8431311613.3522.3346111642.885.204077
11807.29-0.6561712380.5814.0452512466.121.84679812951.919.27411615743.11-1.38468
16157.467.09833316365.15-0.9133318524.84-0.0529818666.3110.8018319004.29-1.36206
#Mann= 3 , 0 , 0
-2789.63  0.0687       0-2789.63  0.0687       019004.29  0.0687       0
#XS Ineff= 2 , 0
       06598.876        10262.14       0
Bank Sta=-2789.63,19004.29
Exp/Cntr=0.3,0.1